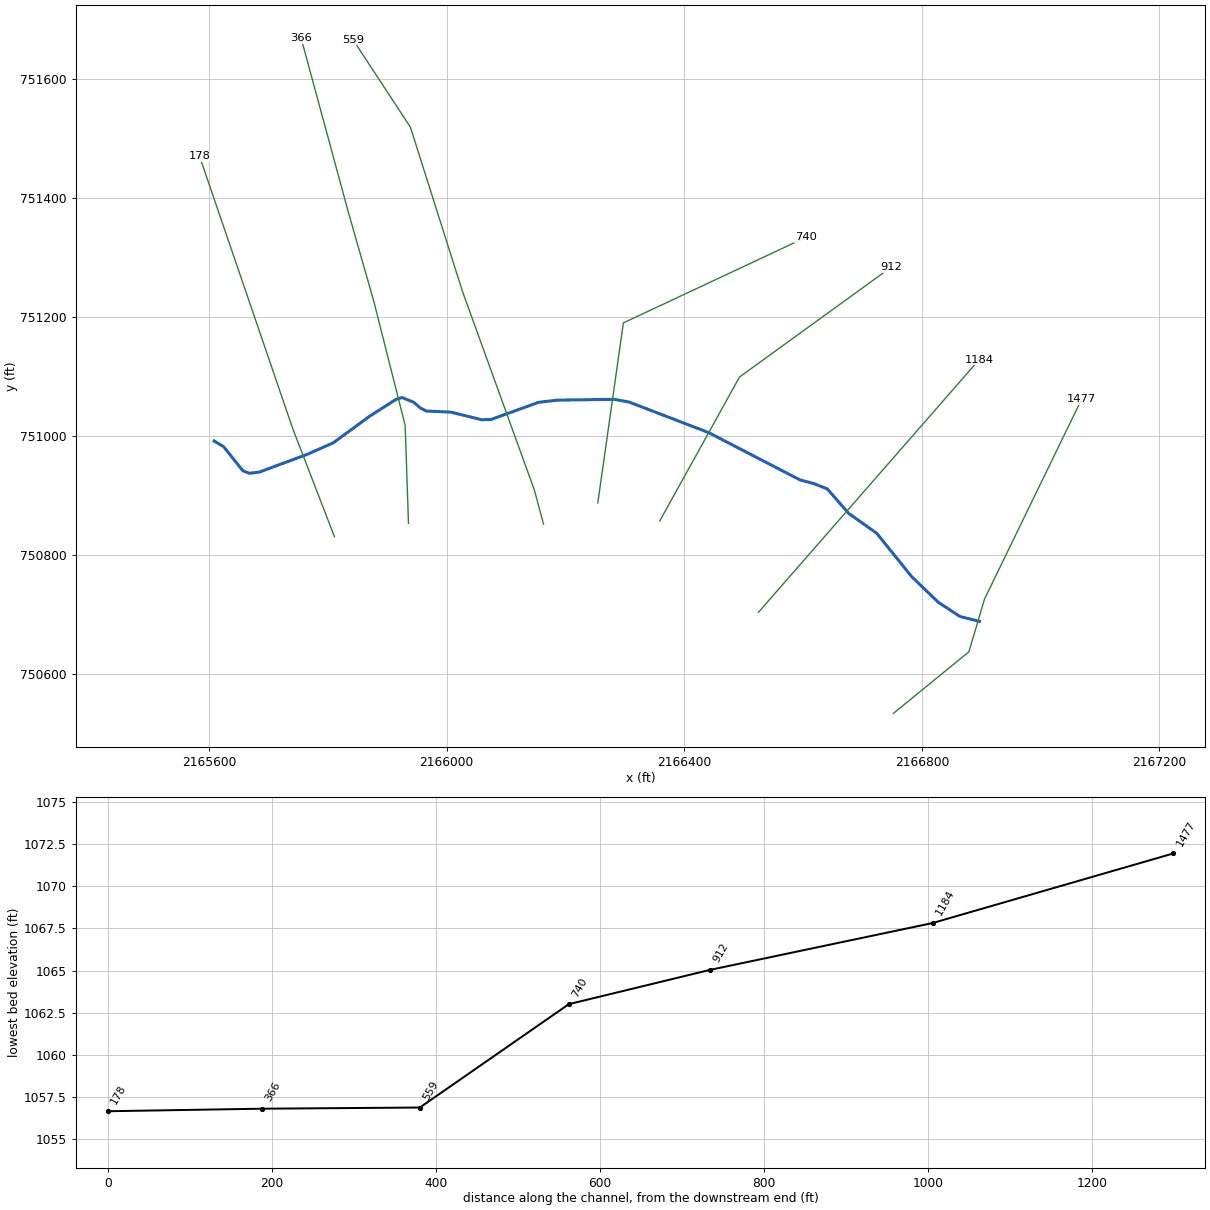
--- HACKCKT1.prj (project) ---

Proj Title=HACKCKT1
Current Plan=p01
Default Exp/Contr=0.3,0.1
English Units
Geom File=g01
Flow File=f01
Plan File=p01
Background Map Layer=IFA
Y Axis Title=Elevation
X Axis Title(PF)=Main Channel Distance
X Axis Title(XS)=Station
BEGIN DESCRIPTION:
--------- MODELED AS PART OF WVEMD CTP PROGRAM, 2023----------
Stream Name: Hackers Creek Tributary 1
Flood Zone:  AFH
Upshur County, WV
HEC-RAS Version: RAS 6.3
Vertical Datum: NAVD88
Projection: NAD 1983 StatePlane West Virginia S FIPS 4702 (US Feet)
Terrain: 1-meter LIDAR (FEMA Region III 3DEP collected 2016-2018)
Land Use: 2019 NLCD
Hydrologic Method:
WV SIR2010-5033 regression equations
Additional Model Notes:
None
END DESCRIPTION:
DSS Export Rating Curves= 0
DSS Export Rating Curve Sorted= 0
DSS Export Volume Flow Curves= 0
DXF OffsetX= 0
DXF OffsetY= 0
DXF ScaleX= 1
DXF ScaleY= 10

--- HACKCKT1.p01 (plan) ---

Plan Title=Floodplain
Program Version=6.30
Short Identifier=Floodplain
Geom File=g01
Flow File=f01
Subcritical Flow
K Sum by GR= 0
Std Step Tol= 0.01
Critical Tol= 0.01
Num of Std Step Trials= 20
Max Error Tol= 0.3
Flow Tol Ratio= 0.001
Split Flow NTrial= 30
Split Flow Tol= 0.02
Split Flow Ratio= 0.02
Log Output Level= 0
Friction Slope Method= 1
Unsteady Friction Slope Method= 2
Unsteady Bridges Friction Slope Method= 1
Parabolic Critical Depth
Global Vel Dist= 0 , 0 , 0
Global Log Level= 0
CheckData=True
Encroach Param=-1 ,0,0, 0
Computation Interval=1MIN
Output Interval=1HOUR
Instantaneous Interval=1HOUR
Mapping Interval=1HOUR
Computation Time Step Use Courant=        0
Computation Time Step Use Time Series=    0
Computation Time Step Count To Double=0
Computation Time Step Max Doubling=0
Computation Time Step Max Halving=0
Computation Time Step Residence Courant=0
Run HTab= 0
Run UNet= 0
Run Sediment= 0
Run PostProcess= 0
Run WQNet= 0
Run RASMapper= 0
UNET Theta= 1
UNET Theta Warmup= 1
UNET ZTol= 0.02
UNET ZSATol= 0.02
UNET MxIter= 20
UNET Max Iter WO Improvement= 0
UNET MaxInSteps= 0
UNET DtIC= 0
UNET DtMin= 0
UNET MaxCRTS= 20
UNET WFStab= 2
UNET SFStab= 1
UNET WFX= 1
UNET SFX= 1
UNET Gravity=32.17405
UNET 1D Methodology=Finite Difference
UNET DSS MLevel= 4
UNET Pardiso=0
UNET DZMax Abort= 100
UNET Use Existing IB Tables=-1
UNET Froude Reduction=False
UNET Froude Limit= 0.8
UNET Froude Power= 4
UNET D1 Cores= 0
UNET WindReference=Eulerian
UNET WindDragFormulation=Hsu (1988)
UNET D2 Coriolis=0
UNET D2 Cores= 0
UNET D2 Theta= 1
UNET D2 Theta Warmup= 1
UNET D2 Z Tol= 0.01
UNET D2 Volume Tol= 0.01
UNET D2 Max Iterations= 20
UNET D2 Equation= 0
UNET D2 RampUpFraction=0.1
UNET D2 TimeSlices= 1
UNET D2 Turbulence Formulation=None
UNET D2 Eddy Viscosity=0.3
UNET D2 Transverse Eddy Viscosity=0.1
UNET D2 Smagorinsky Mixing=0.05
UNET D2 BCVolumeCheck=0
UNET D2 Cores=0
UNET D2 SolverType=PARDISO (Direct)
UNET D2 Minimum Iterations= 3
UNET D2 Maximum Iterations= 30
UNET D2 Restart Number= 10
UNET D2 Relaxation Coeff=1.3
UNET D2 SOR Precondition Iterations= 10
UNET D2 ILUT Maximum Fill= 8
UNET D2 ILUT Tolerance=1E-08
UNET D2 Convergence Tolerance=0.00001
UNET D1D2 MaxIter= 0
UNET D1D2 ZTol=0.01
UNET D1D2 QTol=0.1
UNET D1D2 MinQTol=1
Write IC File= 0
Write IC File at Fixed DateTime=0
Write IC File at Sim End=0
Echo Input=False
Echo Parameters=False
Echo Output=False
Write Detailed= 0
HDF Write Warmup=0
HDF Write Time Slices=0
HDF Flush=0
HDF Compression= 1
HDF Chunk Size= 1
HDF Spatial Parts= 1
HDF Use Max Rows=0
HDF Fixed Rows= 1
Calibration Method= 0
Calibration Iterations= 20
Calibration Max Change=0.05
Calibration Tolerance=0.2
Calibration Maximum=1.5
Calibration Minimum=0.5
Calibration Optimization Method= 1
WQ AD Non Conservative
WQ ULTIMATE=-1
WQ Max Comp Step=1HOUR
WQ Output Interval=15MIN
WQ Output Selected Increments= 0
WQ Output face flow=0
WQ Output face velocity=0
WQ Output face area=0
WQ Output face dispersion=0
WQ Output cell volume=0
WQ Output cell surface area=0
WQ Output cell continuity=0
WQ Output cumulative cell continuity=0
WQ Output face conc=0
WQ Output face dconc_dx=0
WQ Output face courant=0
WQ Output face peclet=0
WQ Output face adv mass=0
WQ Output face disp mass=0
WQ Output cell mass=0
WQ Output cell source sink temp=0
WQ Output nsm pathways=0
WQ Output nsm derived pathways=0
WQ Create Restart=0
WQ Fixed Restart=0
WQ System Summary=0
WQ Write To DSS=0
Sorting and Armoring Iterations= 10
XS Update Threshold= 0.02
Bed Roughness Predictor= 0
Hydraulics Update Threshold= 0.02
Energy Slope Method= 1
Volume Change Method= 1
Sediment Retention Method= 0
Sediment TS Multiplier= 1
Warm Up Method= 0
XS Weighting Method= 0
Number of US Weighted Cross Sections= 1
Number of DS Weighted Cross Sections= 1
Upstream XS Weight=0
Main XS Weight=1
Downstream XS Weight=0
Number of DS XS's Weighted with US Boundary= 1
Upstream Boundary Weight= 1
Weight of XSs Associated with US Boundary= 0
Number of US XS's Weighted with DS Boundary= 1
Downstream Boundary Weight= 0.5
Weight of XSs Associated with DS Boundary= 0.5
Percentile Method= 0
Sediment Output Level= 3
Mass or Volume Output= 0
Output Increment Type= 1
Profile and TS Output Increment= 1
Transport Output Increment 1
XS Output Flag= 0
XS Output Increment= 10
Read HDF5 Sediment Hotstart= 0
Sediment Hotstart Type= 0
Write Gradation File= 0
Read Gradation Hotstart= 0
Write HDF5 File= 1
Write Binary Output= 1
Write DSS Sediment File= 0
DSS Sediment Output Type= 1
SV Curve= 0
Specific Gage Flag= 0
Subcell Erosion Methods= 0
Subcell Deposition Methods= 0
Advection Scheme= 1
Matrix Solver= 0
Implicit Weighting Factor= 1
Maximum Outer Loop Convergence Iterations= 5
Convergence Maximum Absolute= 0.001
Convergence RMSE= 0.0001
Grain Fractions Max Abs Error= 0.001
Max Subgrid Regions= 1
Max Subgrid Length Scale= 3.402823E+38
Initial Layer Thickness= 3.402823E+38
Min Layer Thickness= 3.402823E+38
Max Layer Thickness= 3.402823E+38
Number of Layers= 5

--- HACKCKT1.f01 (steady flow) ---

Flow Title=Flow
Program Version=6.30
Number of Profiles= 1
Profile Names=01Pct
River Rch & RM=River,Reach 1         ,1477
     566
Boundary for River Rch & Prof#=River,Reach 1         , 1
Up Type= 0
Dn Type= 3
Dn Slope=0.00961
DSS Import GetInterval= 0
DSS Import GetPeak= 0
DSS Import FillOption= 0

--- HACKCKT1.g01 (geometry) ---

Geom Title=Geometry
Program Version=6.30

River Reach=River           ,Reach 1
Reach XY= 30
2166897.12797882750687.7228396682166864.24508528750696.034391448
2166827.69124445750719.8654811832166782.71618256750763.245682716
2166724.02532166750835.9713146982166676.81745531 750869.46338205
2166640.98625943750910.469013736 2166617.8579229750919.651741624
2166595.05023837750925.6537638752166440.86814472 751005.38781409
2166307.22963244751056.6682233362166282.07581136751061.246954337
 2166186.4113045751059.8732694242166154.84739126751056.210219026
2166074.75011054751027.3651323472166059.18288445751026.907128006
2166007.01533787751039.727312356 2165965.8077431751041.558673501
2165955.27692428751047.0530851042165944.77464865751056.210219026
2165924.93258882 751064.264919372165915.29085767751061.350486174
 2165871.0874601751033.3172201812165809.24736071750988.103399843
2165766.17953344750969.0447109342165684.73743908750938.883025855
2165667.76798487750936.8515338452165656.92220604750941.229805917
2165624.90217774750981.3678904322165608.69938187750991.268609628

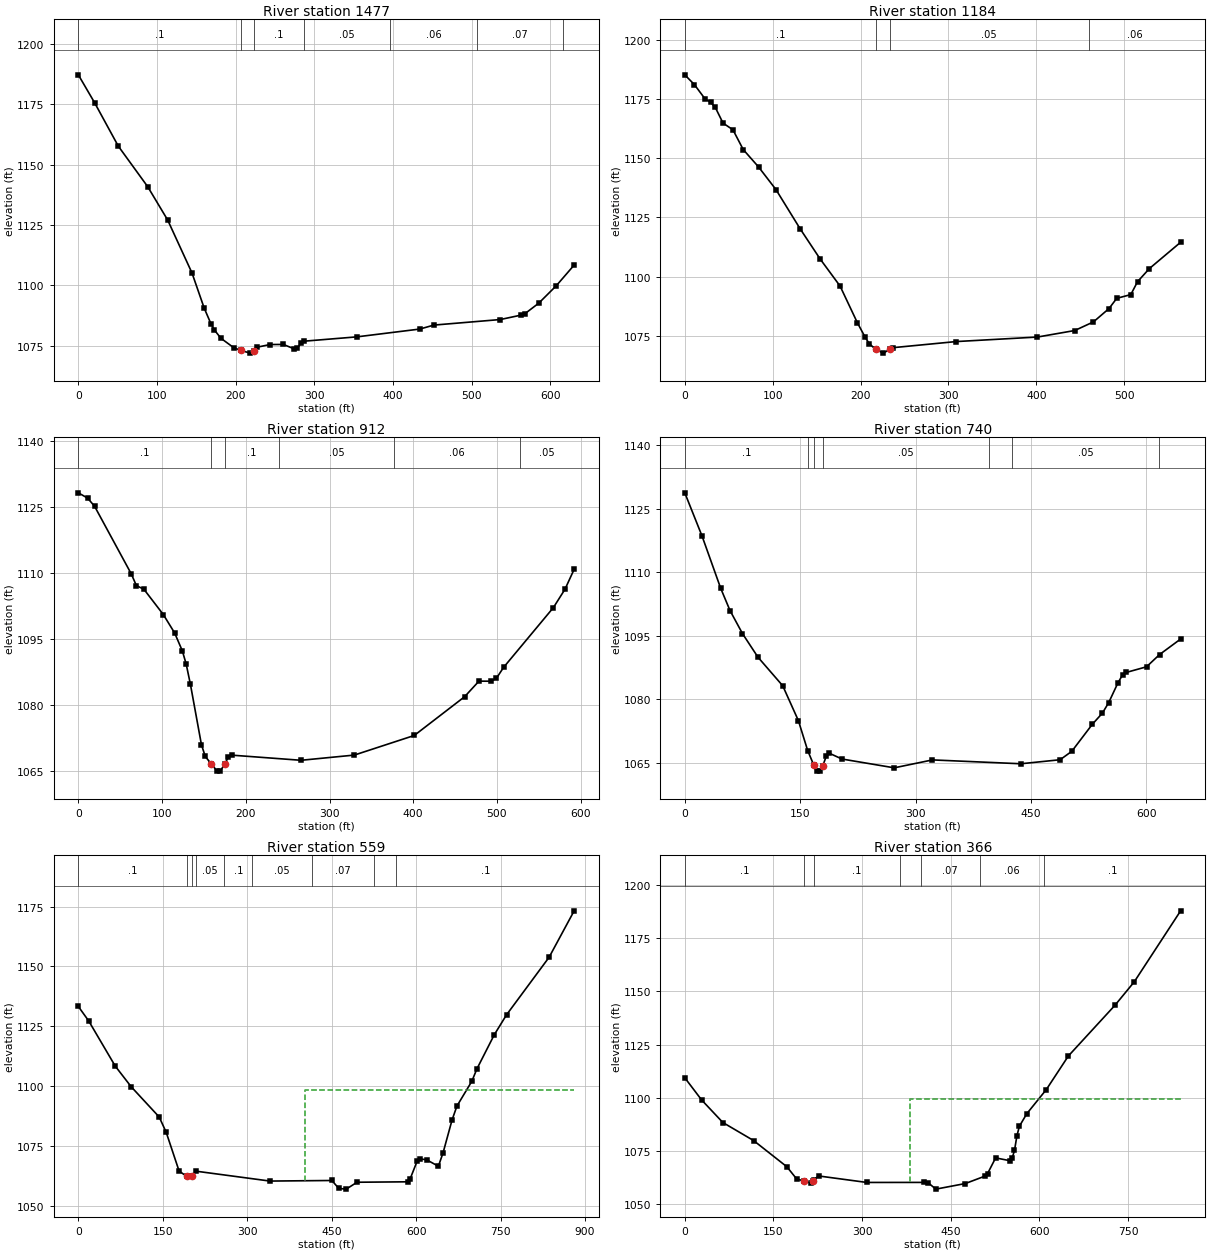
Type RM Length L Ch R = 1 ,1477    ,298.5,293.7,291.1
XS GIS Cut Line= 4
 2166752.1323188750533.0795216452166879.14922262750636.589783085
 2166905.6084501750725.6172009642167069.06930336751061.616113785
#Sta/Elev= 30
       0 1187.29    20.7 1175.72    50.8 1157.74    88.2 1140.93   113.6 1127.11
   144.5 1105.18     160 1090.62   168.6 1084.12   172.8 1081.64   181.2 1078.13
   197.3 1074.27   206.2  1073.1   218.7 1071.95   223.6 1072.97   227.1  1074.4
   243.8 1075.51   260.7 1075.55     274 1073.77   278.5 1073.97   282.9 1076.07
   287.4 1076.91   354.1 1078.69   434.2 1081.93     452 1083.57   536.5 1085.87
   563.2 1087.73   567.6 1088.24   585.4 1092.66   607.7 1099.89   630.4 1108.45
#Mann= 7 ,-1,0
       0      .1       0   206.2    .045       0   223.6      .1       0
  286.73     .05       0  396.73     .06       0  506.73     .07       0
  616.73     .05       0
Bank Sta=206.2,223.6
XS Rating Curve= 0 ,0
Exp/Cntr(USF)=0,0
Exp/Cntr=0.3,0.1

Type RM Length L Ch R = 1 ,1184    ,268.2,271.5,273.8
XS GIS Cut Line= 2
2166524.94915805750703.0913915632166896.42014782751127.905558543
#Sta/Elev= 30
       0 1185.13      11 1180.97    23.1 1174.96    29.3 1173.58    34.7  1171.4
    43.5 1164.79    54.8 1161.96    66.5 1153.63    83.9 1146.32   103.7 1136.79
   131.3 1120.21     154 1107.52   176.7  1096.1   196.5 1080.56   205.4 1074.43
     210 1071.76   217.4 1069.38   225.9 1067.82   233.11069.366   236.6 1070.11
   308.7 1072.69   401.3  1074.6   443.8 1077.35   465.1 1080.99   482.8 1086.61
   491.6 1090.92   507.6 1092.49   515.3 1097.96   528.8 1103.48   564.3 1114.55
#Mann= 4 ,-1,0
       0      .1       0   217.4    .045       0   233.1     .05       0
     460     .06       0
Bank Sta=217.4,233.1
XS Rating Curve= 0 ,0
Exp/Cntr(USF)=0,0
Exp/Cntr=0.3,0.1

Type RM Length L Ch R = 1 ,912     ,166.5,171.9,175.2
XS GIS Cut Line= 3
 2166358.7715553750856.5722390482166493.04304641751098.762872553
2166748.47956949751283.585635791
#Sta/Elev= 30
       0 1128.19    11.1 1126.99    19.4 1125.14    63.3 1109.77    69.3 1107.15
    78.4 1106.29   101.5 1100.57     115  1096.4   124.2 1092.34   128.8 1089.35
   133.9 1084.71     147 1071.07   151.6 1068.37   158.61066.719   165.3 1065.16
   169.2 1065.04   175.41066.702   179.1 1068.32   183.6 1068.66     266  1067.5
   329.6 1068.68   401.2 1073.13   461.4 1081.93   478.5 1085.46   492.9 1085.44
   499.4 1086.12   507.9 1088.58   567.4 1102.15   581.3 1106.33   592.2 1110.85
#Mann= 6 ,-1,0
       0      .1       0   158.6    .045       0   175.4      .1       0
     240     .05       0  376.92     .06       0  526.92     .05       0
Bank Sta=158.6,175.4
XS Rating Curve= 0 ,0
Exp/Cntr(USF)=0,0
Exp/Cntr=0.3,0.1

Type RM Length L Ch R = 1 ,740     ,176.2,181.6,186.3
XS GIS Cut Line= 3
2166254.51232312 750886.940666182166297.57927999751189.814657494
2166604.32619635751333.427986517
#Sta/Elev= 30
       0 1128.76    22.5 1118.51    46.7 1106.19    58.8 1100.94      75  1095.5
    95.2 1089.91   127.3 1083.18   147.7 1074.93   159.8 1067.85   167.9 1064.34
     172 1063.12     176 1063.01  179.54 1064.32   184.1 1066.65   188.1 1067.22
   204.3 1065.87   272.3 1063.79     322 1065.66   436.9 1064.75   487.9  1065.7
   503.1 1067.69     530 1074.12   542.9 1076.71   551.1  1079.2   563.1 1083.86
   569.1 1085.74   573.8 1086.32   600.3 1087.66   617.2 1090.55   644.6 1094.22
#Mann= 7 ,-1,0
       0      .1       0     160     .05       0   167.9    .045       0
  179.54     .05       0  395.92     .06       0  425.92     .05       0
  615.92     .06       0
Bank Sta=167.9,179.54
XS Rating Curve= 0 ,0
Exp/Cntr(USF)=0,0
Exp/Cntr=0.3,0.1

Type RM Length L Ch R = 1 ,559     ,190.3,192.7,190.8
XS GIS Cut Line= 5
2166163.11190805750851.3821874432166147.77456223750908.548658218
 2166026.5496443751243.2202309172165939.12238599751518.907888454
2165842.28917881 751666.38376385
#Sta/Elev= 30
       0 1133.24    18.4  1127.2    65.6  1108.3    93.9 1099.68   143.7 1087.02
   156.2 1080.56     179 1064.44  192.53 1062.21  202.04 1062.21   208.8 1064.39
   340.4 1060.25   450.4 1060.49   462.7 1057.17   475.9 1056.88   495.1 1059.76
     585 1059.94   589.2 1061.03   601.8 1068.54   606.6 1069.55   618.6 1069.16
   639.6 1066.45     648 1072.12   663.9  1085.8   672.6 1091.63     699 1101.96
   708.1 1107.17   738.9 1121.42   760.7 1129.76   836.3 1153.82   880.8 1173.22
#Mann= 9 ,-1,0
       0      .1       0  192.53    .045       0  202.04      .1       0
  209.19     .05       0  259.19      .1       0  309.19     .05       0
  415.14     .07       0  525.14     .06       0  565.14      .1       0
#XS Ineff= 2 , 0
                          401.87         1098.41
Permanent Ineff=
       F       F
Bank Sta=192.53,202.04
XS Rating Curve= 0 ,0
Exp/Cntr(USF)=0,0
Exp/Cntr=0.3,0.1

Type RM Length L Ch R = 1 ,366     ,185.5,187.8,189.3
XS GIS Cut Line= 5
2165935.84032911750852.7764916082165930.26311245751017.304383108
2165877.78227004751224.9631248822165834.16461057 751377.62493302
     2165755.191      751668.386
#Sta/Elev= 30
       0 1109.31    28.4 1098.88    64.4 1088.22   116.5 1079.69   172.6 1067.38
   189.2 1061.63   201.6 1060.63     214 1059.75   216.8 1060.57   218.9 1061.32
   226.4 1063.02   307.9 1059.96     404 1059.98   412.3 1059.68   424.8 1056.81
   474.7 1059.45     508 1062.96   512.2 1064.09   525.9 1071.54   549.6 1070.24
   553.7 1071.27   557.8 1075.05     562 1082.04   566.1 1086.46   578.6 1092.36
   611.7 1103.77     649  1119.6   727.8 1143.49   760.5 1154.58   838.9 1188.03
#Mann= 7 ,-1,0
       0      .1       0   201.6    .045       0   218.9      .1       0
  364.62     .05       0  398.81     .07       0  498.81     .06       0
  607.58      .1       0
#XS Ineff= 2 , 0
                          381.02         1099.31
Permanent Ineff=
       F       F
Bank Sta=201.6,216.8
XS Rating Curve= 0 ,0
Exp/Cntr(USF)=0,0
Exp/Cntr=0.3,0.1

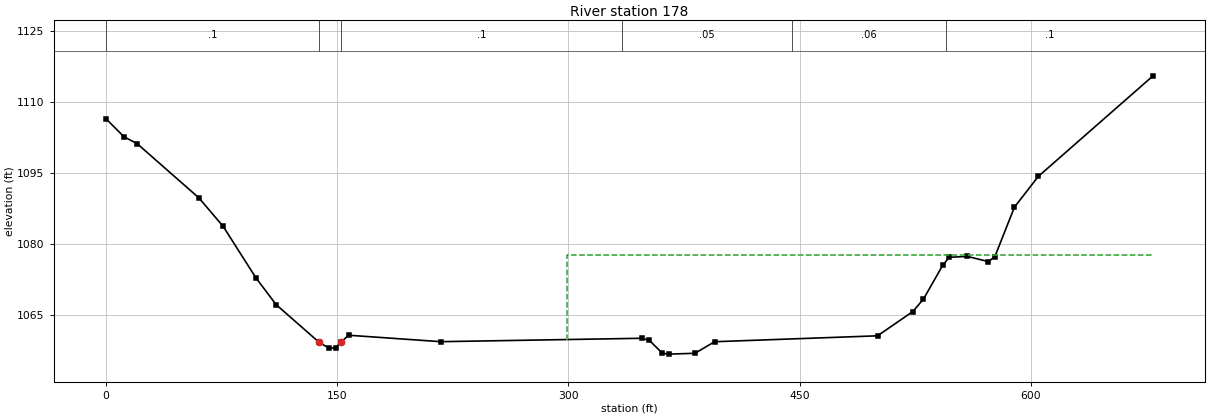
Type RM Length L Ch R = 1 ,178     ,,,
XS GIS Cut Line= 3
2165811.21007385750830.2313478232165740.93714392751012.188041392
2165584.07792532751470.216959686
#Sta/Elev= 30
       0 1106.39    11.7 1102.58    20.3 1101.11    60.3 1089.67    76.1 1083.63
    97.2 1072.82   110.4 1067.12   138.41059.126   144.7 1057.94     149 1057.99
  152.18 1059.13   157.5 1060.65   217.2 1059.29   347.6 1060.01   352.5 1059.56
     361 1056.83   365.2 1056.66   382.1 1056.84   394.8 1059.28   500.5 1060.53
   523.4 1065.66   530.3  1068.3   542.8 1075.44     547 1077.11   558.6 1077.31
   572.4 1076.21   576.6 1077.27   589.3 1087.71   604.8 1094.21   679.2 1115.45
#Mann= 6 ,-1,0
       0      .1       0   138.4    .045       0  152.18      .1       0
  335.06     .05       0  445.06     .06       0  545.06      .1       0
#XS Ineff= 2 , 0
                          298.92         1077.64
Permanent Ineff=
       F       F
Bank Sta=138.4,152.18
XS Rating Curve= 0 ,0
Exp/Cntr(USF)=0,0
Exp/Cntr=0.3,0.1
LCMann Table=0

Chan Stop Cuts=-1
Use User Specified Reach Order=0
Composite Channel Slope=5