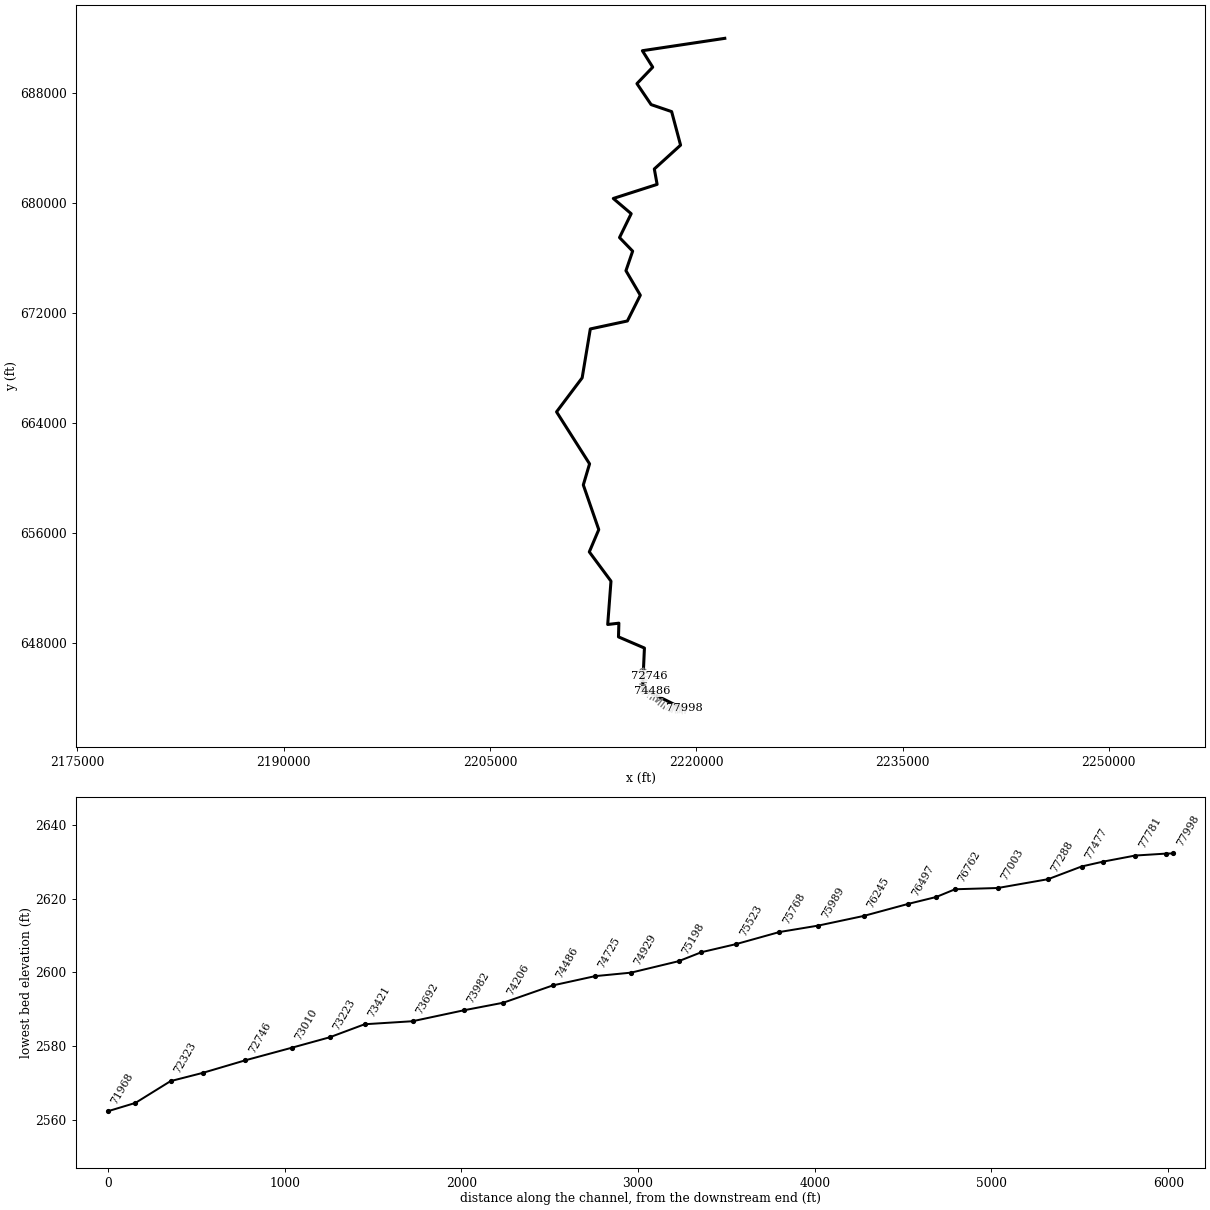
--- RFMIDDLERV.prj (project) ---

Proj Title=RFMIDDLERV
Current Plan=p01
Default Exp/Contr=0.3,0.1
English Units
Geom File=g01
Flow File=f01
Plan File=p01
Y Axis Title=Elevation
X Axis Title(PF)=Main Channel Distance
X Axis Title(XS)=Station
BEGIN DESCRIPTION:
END DESCRIPTION:
DSS Export Rating Curves= 0
DSS Export Rating Curve Sorted= 0
DSS Export Volume Flow Curves= 0
DXF OffsetX= 0
DXF OffsetY= 0
DXF ScaleX= 1
DXF ScaleY= 10

--- RFMIDDLERV.p01 (plan) ---

Plan Title=Floodplain
Program Version=6.30
Short Identifier=Floodplain
Geom File=g01
Flow File=f01
Subcritical Flow
K Sum by GR= 0
Std Step Tol= 0.01
Critical Tol= 0.01
Num of Std Step Trials= 20
Max Error Tol= 0.3
Flow Tol Ratio= 0.001
Split Flow NTrial= 30
Split Flow Tol= 0.02
Split Flow Ratio= 0.02
Log Output Level= 0
Friction Slope Method= 1
Unsteady Friction Slope Method= 2
Unsteady Bridges Friction Slope Method= 1
Parabolic Critical Depth
Global Vel Dist= 0 , 0 , 0
Global Log Level= 0
CheckData=True
Encroach Param=-1 ,0,0, 0
Computation Interval=1MIN
Output Interval=1HOUR
Instantaneous Interval=1HOUR
Mapping Interval=1HOUR
Computation Time Step Use Courant=        0
Computation Time Step Use Time Series=    0
Computation Time Step Count To Double=0
Computation Time Step Max Doubling=0
Computation Time Step Max Halving=0
Computation Time Step Residence Courant=0
Run HTab= 0
Run UNet= 0
Run Sediment= 0
Run PostProcess= 0
Run WQNet= 0
Run RASMapper= 0
UNET Theta= 1
UNET Theta Warmup= 1
UNET ZTol= 0.02
UNET ZSATol= 0.02
UNET MxIter= 20
UNET Max Iter WO Improvement= 0
UNET MaxInSteps= 0
UNET DtIC= 0
UNET DtMin= 0
UNET MaxCRTS= 20
UNET WFStab= 2
UNET SFStab= 1
UNET WFX= 1
UNET SFX= 1
UNET Gravity=32.17405
UNET 1D Methodology=Finite Difference
UNET DSS MLevel= 4
UNET Pardiso=0
UNET DZMax Abort= 100
UNET Use Existing IB Tables=-1
UNET Froude Reduction=False
UNET Froude Limit= 0.8
UNET Froude Power= 4
UNET D1 Cores= 0
UNET WindReference=Eulerian
UNET WindDragFormulation=Hsu (1988)
UNET D2 Coriolis=0
UNET D2 Cores= 0
UNET D2 Theta= 1
UNET D2 Theta Warmup= 1
UNET D2 Z Tol= 0.01
UNET D2 Volume Tol= 0.01
UNET D2 Max Iterations= 20
UNET D2 Equation= 0
UNET D2 RampUpFraction=0.1
UNET D2 TimeSlices= 1
UNET D2 Turbulence Formulation=None
UNET D2 Eddy Viscosity=0.3
UNET D2 Transverse Eddy Viscosity=0.1
UNET D2 Smagorinsky Mixing=0.05
UNET D2 BCVolumeCheck=0
UNET D2 Cores=0
UNET D2 SolverType=PARDISO (Direct)
UNET D2 Minimum Iterations= 3
UNET D2 Maximum Iterations= 30
UNET D2 Restart Number= 10
UNET D2 Relaxation Coeff=1.3
UNET D2 SOR Precondition Iterations= 10
UNET D2 ILUT Maximum Fill= 8
UNET D2 ILUT Tolerance=1E-08
UNET D2 Convergence Tolerance=0.00001
UNET D1D2 MaxIter= 0
UNET D1D2 ZTol=0.01
UNET D1D2 QTol=0.1
UNET D1D2 MinQTol=1
Write IC File= 0
Write IC File at Fixed DateTime=0
Write IC File at Sim End=0
Echo Input=False
Echo Parameters=False
Echo Output=False
Write Detailed= 0
HDF Write Warmup=0
HDF Write Time Slices=0
HDF Flush=0
HDF Compression= 1
HDF Chunk Size= 1
HDF Spatial Parts= 1
HDF Use Max Rows=0
HDF Fixed Rows= 1
Calibration Method= 0
Calibration Iterations= 20
Calibration Max Change=0.05
Calibration Tolerance=0.2
Calibration Maximum=1.5
Calibration Minimum=0.5
Calibration Optimization Method= 1
WQ AD Non Conservative
WQ ULTIMATE=-1
WQ Max Comp Step=1HOUR
WQ Output Interval=15MIN
WQ Output Selected Increments= 0
WQ Output face flow=0
WQ Output face velocity=0
WQ Output face area=0
WQ Output face dispersion=0
WQ Output cell volume=0
WQ Output cell surface area=0
WQ Output cell continuity=0
WQ Output cumulative cell continuity=0
WQ Output face conc=0
WQ Output face dconc_dx=0
WQ Output face courant=0
WQ Output face peclet=0
WQ Output face adv mass=0
WQ Output face disp mass=0
WQ Output cell mass=0
WQ Output cell source sink temp=0
WQ Output nsm pathways=0
WQ Output nsm derived pathways=0
WQ Create Restart=0
WQ Fixed Restart=0
WQ System Summary=0
WQ Write To DSS=0
Sorting and Armoring Iterations= 10
XS Update Threshold= 0.02
Bed Roughness Predictor= 0
Hydraulics Update Threshold= 0.02
Energy Slope Method= 1
Volume Change Method= 1
Sediment Retention Method= 0
Sediment TS Multiplier= 1
Warm Up Method= 0
XS Weighting Method= 0
Number of US Weighted Cross Sections= 1
Number of DS Weighted Cross Sections= 1
Upstream XS Weight=0
Main XS Weight=1
Downstream XS Weight=0
Number of DS XS's Weighted with US Boundary= 1
Upstream Boundary Weight= 1
Weight of XSs Associated with US Boundary= 0
Number of US XS's Weighted with DS Boundary= 1
Downstream Boundary Weight= 0.5
Weight of XSs Associated with DS Boundary= 0.5
Percentile Method= 0
Sediment Output Level= 3
Mass or Volume Output= 0
Output Increment Type= 1
Profile and TS Output Increment= 1
Transport Output Increment 1
XS Output Flag= 0
XS Output Increment= 10
Read HDF5 Sediment Hotstart= 0
Sediment Hotstart Type= 0
Write Gradation File= 0
Read Gradation Hotstart= 0
Write HDF5 File= 1
Write Binary Output= 1
Write DSS Sediment File= 0
DSS Sediment Output Type= 1
SV Curve= 0
Specific Gage Flag= 0
Subcell Erosion Methods= 0
Subcell Deposition Methods= 0
Advection Scheme= 1
Matrix Solver= 0
Implicit Weighting Factor= 1
Maximum Outer Loop Convergence Iterations= 5
Convergence Maximum Absolute= 0.001
Convergence RMSE= 0.0001
Grain Fractions Max Abs Error= 0.001
Max Subgrid Regions= 1
Max Subgrid Length Scale= 3.402823E+38
Initial Layer Thickness= 3.402823E+38
Min Layer Thickness= 3.402823E+38
Max Layer Thickness= 3.402823E+38
Number of Layers= 5

--- RFMIDDLERV.f01 (steady flow) ---

Flow Title=Flows
Program Version=6.30
Number of Profiles= 1
Profile Names=100Yr
River Rch & RM=River 1,Reach 1         ,77998
     429
River Rch & RM=River 1,Reach 1         ,73982
     680
River Rch & RM=River 1,Reach 1         ,70461
    1100
River Rch & RM=River 1,Reach 1         ,63781
    1280
River Rch & RM=River 1,Reach 1         ,60998
    1430
River Rch & RM=River 1,Reach 1         ,51486
    1590
River Rch & RM=River 1,Reach 1         ,46680
    1770
River Rch & RM=River 1,Reach 1         ,39504
    1970
River Rch & RM=River 1,Reach 1         ,37619
    2920
River Rch & RM=River 1,Reach 1         ,35386
    3580
River Rch & RM=River 1,Reach 1         ,20481
    3980
River Rch & RM=River 1,Reach 1         ,8186
    4550
Boundary for River Rch & Prof#=River 1,Reach 1         , 1
Up Type= 0
Dn Type= 3
Dn Slope=0.0025
DSS Import GetInterval= 0
DSS Import GetPeak= 0
DSS Import FillOption= 0

--- RFMIDDLERV.g01 (geometry) ---

Geom Title=Geometry
Program Version=6.30

River Reach=River 1         ,Reach 1
Reach XY= 30
2219177.73969478643113.7863898192216099.43057276644640.819703758
2216234.69998726647597.3790793422214347.73558535648408.939792171
2214376.66662984649405.9633886672213564.70532726649312.273287341
2213802.36430076652464.3969043342212226.40255767654592.254525259
2212914.94153492656214.4028557542211790.54647401659464.166041255
 2212245.7758785660998.2905976772209844.97523393664781.090774834
 2211706.6430985667256.808920503 2212299.6891565670814.140716583
2214995.32418518  671394.28096052215935.14382784673267.538368836
2214890.55963093675051.283489004 2215378.2975006676475.235037416
2214423.39717942677463.9597660012215271.90171601 679199.11476025
 2213970.6858145680307.7421361662217156.83462593681332.351963595
2216953.51515068 682454.658117922218862.08515242684188.267511591
2218212.06381467686628.1865162552216720.40603684687138.101835012
2215690.04425243688662.9832996732216836.78900617689861.294551343
2216086.03788301    691059.176672222076.56395967691959.104988262

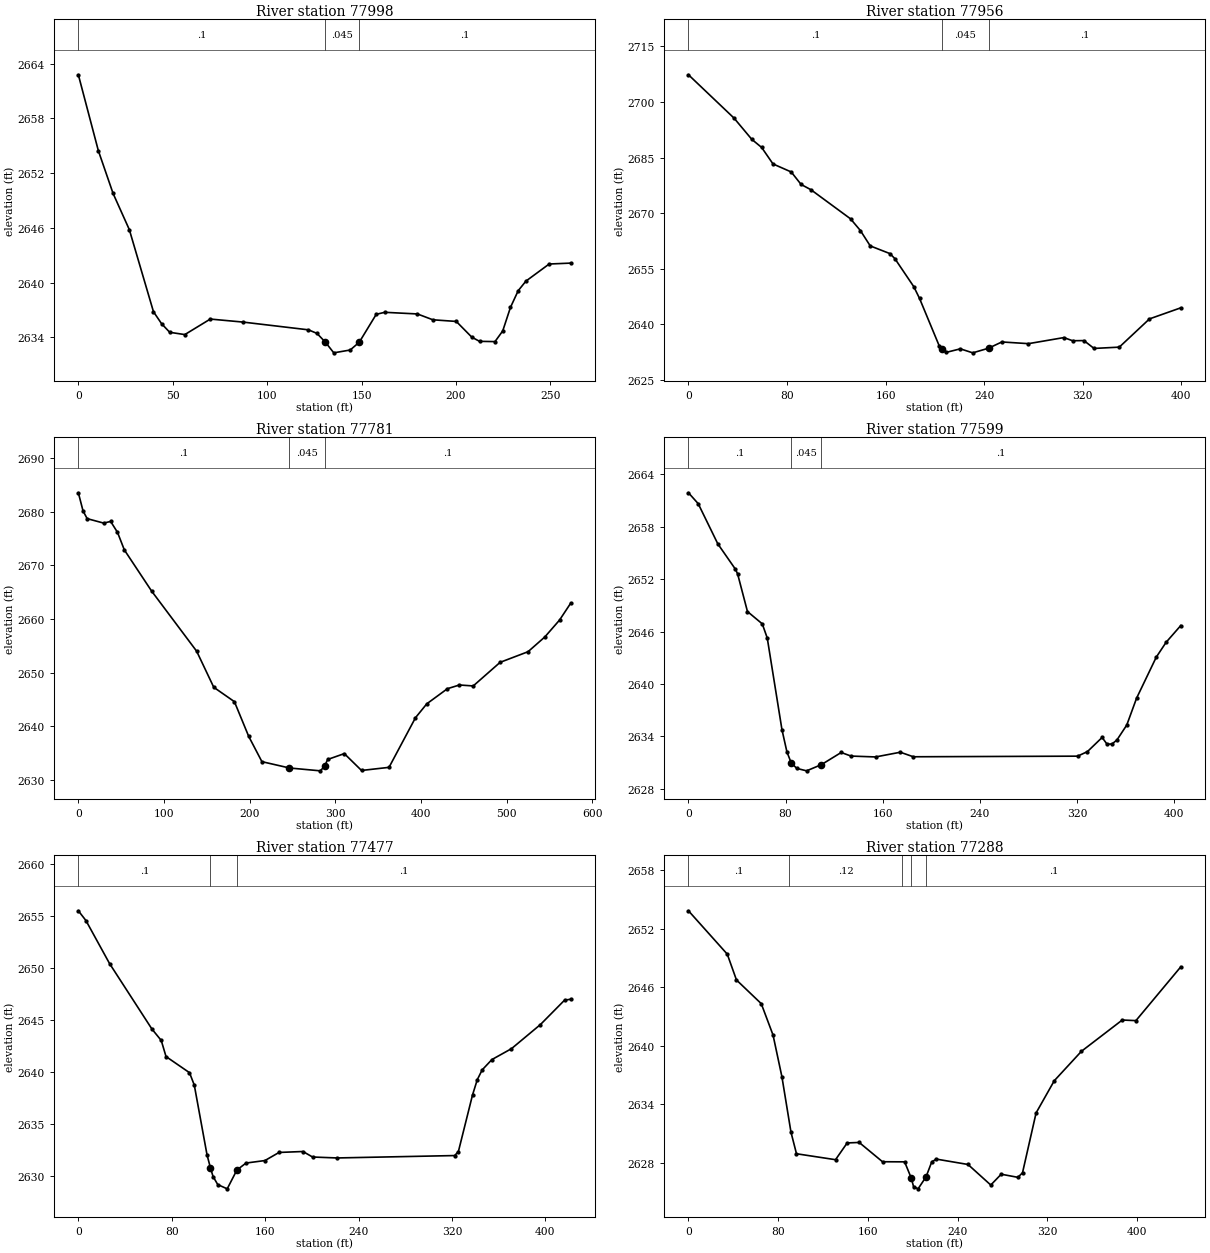
Type RM Length L Ch R = 1 ,77998   ,49.3,41.5,39.5
XS GIS Cut Line= 5
2219260.03424901643012.043316241  2219231.482832643085.423126293
2219201.86407231643098.2312385932219154.10048686643122.513284829
2219132.52245848643216.268517389
#Sta/Elev= 30
       0 2662.77    10.6 2654.45    18.4 2649.77      27 2645.81    39.8 2636.81
    44.1  2635.5    48.4 2634.56    56.4 2634.31    69.9 2636.01    87.2 2635.68
   121.9 2634.83   126.4 2634.44   130.9 2633.47   135.3 2632.31     144 2632.62
   148.8 2633.47   157.8 2636.53   162.3 2636.75   179.6 2636.57   187.8 2635.93
   200.2 2635.75   208.4 2634.03   212.5 2633.57   220.7 2633.54   224.8 2634.71
   228.9 2637.29     233 2639.12   237.1 2640.17   249.4 2642.04   260.8 2642.14
#Mann= 3 ,-1,0
       0      .1       0   130.9    .045       0   148.8      .1       0
Bank Sta=130.9,148.8
XS Rating Curve= 0 ,0
Exp/Cntr(USF)=0,0
Exp/Cntr=0.3,0.1

Type RM Length L Ch R = 1 ,77956   ,190.3,174.7,157.5
XS GIS Cut Line= 6
2219184.03773896642853.8072615142219175.97211892643057.815235375
2219167.80694733643066.460711177 2219157.7205589643074.145578556
2219134.66595676643090.9562259492219104.73287757643229.960042498
#Sta/Elev= 30
       0 2707.36      37 2695.65    51.4 2689.92    59.4 2687.73    68.6 2683.28
    83.4 2681.11    91.4 2677.74    99.4 2676.31   131.5 2668.46   139.5  2665.3
   147.5 2661.14   163.5 2659.06   167.5  2657.7   182.9  2650.1   187.5 2646.96
   203.5 2634.13   205.92633.286   209.2 2632.39   220.6 2633.34   230.7 2632.26
   243.5 2633.51   254.3  2635.2   275.9 2634.74   304.6 2636.38   311.7 2635.53
   320.9 2635.57   329.1 2633.45   349.6  2633.8   374.1 2641.43   399.5 2644.42
#Mann= 3 ,-1,0
       0      .1       0   205.9    .045       0   243.5      .1       0
Bank Sta=205.9,243.5
XS Rating Curve= 0 ,0
Exp/Cntr(USF)=0,0
Exp/Cntr=0.3,0.1

Type RM Length L Ch R = 1 ,77781   ,164.7,182.6,188.6
XS GIS Cut Line= 4
2218983.93199746642843.6610469892218995.72988584642971.325910486
2219018.76151076643287.1881951182218975.61712295643409.704932345
#Sta/Elev= 30
       0 2683.55     5.5 2680.16    10.3 2678.73    29.6  2677.9    37.7 2678.21
    45.7 2676.18    53.7  2672.9    85.5 2665.24   138.1 2654.03   158.1  2647.3
   182.2 2644.62   198.9 2638.15   214.3 2633.44   246.5 2632.26   282.5 2631.73
   287.4 2632.58   291.1 2633.85   310.5 2634.94   330.6  2631.8   362.7 2632.38
   393.6 2641.63   406.8 2644.22   430.9 2647.04   444.9 2647.73     461 2647.55
   492.4 2651.95     525 2653.93   544.6 2656.68   561.8 2659.83   574.8 2662.97
#Mann= 3 ,-1,0
       0      .1       0   246.5    .045       0   287.4      .1       0
Bank Sta=246.5,287.4
XS Rating Curve= 0 ,0
Exp/Cntr(USF)=0,0
Exp/Cntr=0.3,0.1

Type RM Length L Ch R = 1 ,77599   ,125.3,121.4,117.9
XS GIS Cut Line= 3
2218910.91990602 642921.321220422218880.24465835 643094.52640357
2218843.04364157643321.140312407
#Sta/Elev= 30
       0 2661.89       8 2660.65    24.2 2656.04    38.7 2653.14    40.5  2652.6
    48.6  2648.3    60.8 2646.89    64.9 2645.27      77 2634.79    81.1 2632.24
    84.6 2630.99    89.2 2630.35    97.3 2630.07   109.5 2630.78   125.8 2632.17
   133.9 2631.76   154.1 2631.66   174.5  2632.2   185.2 2631.68   320.5 2631.75
   328.6 2632.27   340.7 2633.89   344.8 2633.11   348.9 2633.15   352.9  2633.6
     361 2635.31   369.1 2638.39   385.3 2643.08   393.4 2644.78   405.5  2646.7
#Mann= 3 ,-1,0
       0      .1       0    84.6    .045       0   109.5      .1       0
Bank Sta=84.6,109.5
XS Rating Curve= 0 ,0
Exp/Cntr(USF)=0,0
Exp/Cntr=0.3,0.1

Type RM Length L Ch R = 1 ,77477   ,188.9,189,188.4
XS GIS Cut Line= 3
2218759.20896688 642902.735504122218782.69076029643084.607135907
2218718.67990964 643314.13404047
#Sta/Elev= 30
       0 2655.49     6.5 2654.55    26.7 2650.42      63 2644.12      71 2643.02
    75.1 2641.47    95.2 2639.92    99.3 2638.73   110.2 2632.03   113.12630.782
   115.4 2629.93   119.4 2629.16   127.5 2628.75   135.8 2630.56   143.6 2631.23
   159.8 2631.47   171.9 2632.25   192.4 2632.34   200.6 2631.81   221.6 2631.72
   322.3 2631.95   325.5 2632.33   337.6 2637.77   341.7 2639.25   345.9 2640.19
   354.2 2641.18     371 2642.23   395.8 2644.55   416.5  2646.9   421.7 2646.98
#Mann= 3 ,-1,0
       0      .1       0   113.1    .045       0   135.8      .1       0
Bank Sta=113.1,135.8
XS Rating Curve= 0 ,0
Exp/Cntr(USF)=0,0
Exp/Cntr=0.3,0.1

Type RM Length L Ch R = 1 ,77288   ,280.4,285,281.1
XS GIS Cut Line= 3
2218640.60013798642886.9925515132218614.49102147643045.655644193
 2218574.3231499643320.805564411
#Sta/Elev= 30
       0 2653.84    34.6 2649.39    42.8 2646.74    64.9 2644.31    75.4 2641.09
    83.3 2636.82    91.4 2631.12    96.3 2628.91   131.1  2628.3   141.5 2630.02
   152.2 2630.07     173 2628.09   192.7 2628.08   198.62626.418   200.7 2625.53
   204.7 2625.31   211.8 2626.54   216.9 2628.08     221 2628.36   249.2 2627.81
   269.5  2625.7   278.8 2626.81   293.7 2626.49   297.8 2626.96   309.9  2633.1
   326.1  2636.4   350.3 2639.42   386.7 2642.63   398.9 2642.57   438.9 2648.09
#Mann= 5 ,-1,0
       0      .1       0      90     .12       0   190.8      .1       0
   198.6    .045       0   211.8      .1       0
Bank Sta=198.6,211.8
XS Rating Curve= 0 ,0
Exp/Cntr(USF)=0,0
Exp/Cntr=0.3,0.1

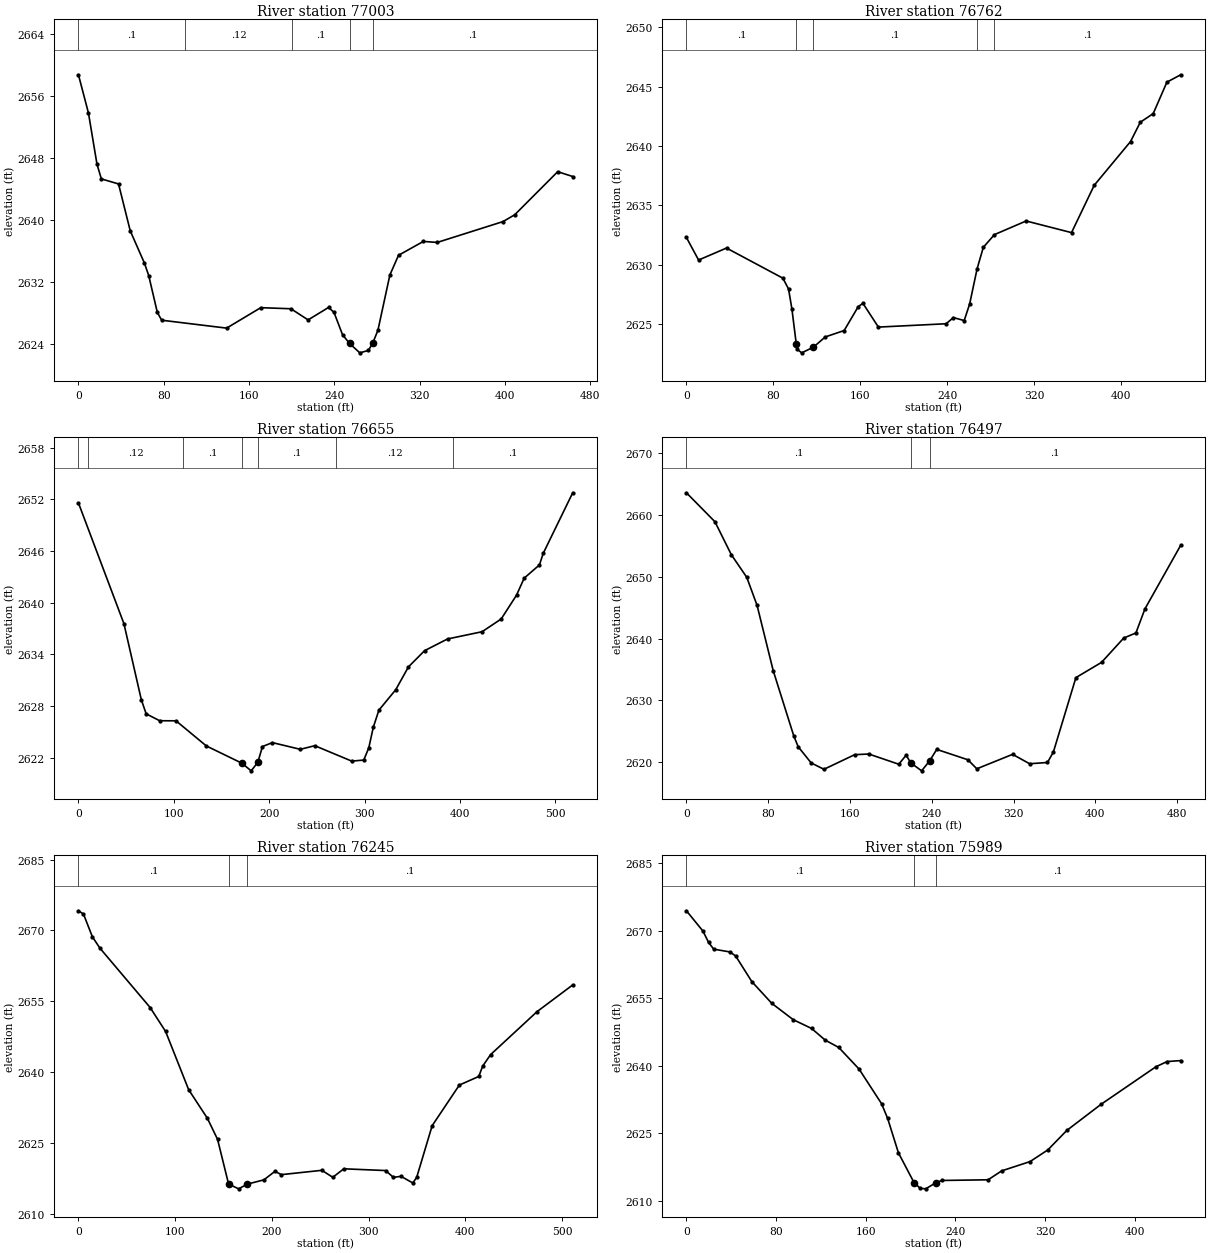
Type RM Length L Ch R = 1 ,77003   ,242.9,241.6,236.8
XS GIS Cut Line= 3
2218504.29660259642879.9148609672218477.14702662643068.260113916
2218440.54405366643339.122113844
#Sta/Elev= 30
       0  2658.8     9.4 2653.86    17.4 2647.25    21.5 2645.36    37.6 2644.71
    48.6 2638.65    61.9 2634.49    65.9 2632.89      74 2628.12    78.1 2627.12
     139  2626.1     171 2628.74   199.3  2628.6   215.4 2627.16   234.6 2628.77
   239.7 2628.13   247.7 2625.25   254.32624.117   263.9 2622.91   271.9 2623.22
   275.92624.118   280.9 2625.83   292.1 2632.96   300.2  2635.5   323.5 2637.29
   336.5 2637.16   398.2 2639.85   409.2 2640.73   449.5 2646.29   463.6 2645.67
#Mann= 5 ,-1,0
       0      .1       0     100     .12       0  200.29      .1       0
   254.3    .045       0   275.9      .1       0
Bank Sta=254.3,275.9
XS Rating Curve= 0 ,0
Exp/Cntr(USF)=0,0
Exp/Cntr=0.3,0.1

Type RM Length L Ch R = 1 ,76762   ,107.5,106.5,102.5
XS GIS Cut Line= 5
2218223.73675947642926.9990522342218251.48766945642995.308984497
2218287.77732097643081.7637425172218349.88846322643167.413586244
2218402.32881053643341.361894657
#Sta/Elev= 30
       0 2632.29    11.2 2630.39    36.9  2631.4    88.8 2628.86      94 2627.95
    97.1 2626.27   101.12623.329   101.8 2622.88   106.1 2622.57   116.8 2623.04
   127.8 2623.91   145.2 2624.45   158.2 2626.47   162.5 2626.74   176.7 2624.74
     239 2625.02   245.8 2625.54   255.7 2625.29   260.7 2626.68   267.6 2629.66
   273.3 2631.46   283.5 2632.53   312.7 2633.68   354.5  2632.7   375.4 2636.69
   408.8 2640.37   417.8    2642   429.7 2642.73   442.3 2645.38     455    2646
#Mann= 5 ,-1,0
       0      .1       0   101.1    .045       0   116.8      .1       0
   267.6     .12       0   283.5      .1       0
Bank Sta=101.1,116.8
XS Rating Curve= 0 ,0
Exp/Cntr(USF)=0,0
Exp/Cntr=0.3,0.1

Type RM Length L Ch R = 1 ,76655   ,154.4,158.3,156.5
XS GIS Cut Line= 3
 2218076.7069555642968.391156819 2218316.2078897  643241.3318441
2218328.27190164643395.895546245
#Sta/Elev= 30
       0 2651.59    47.7 2637.56    65.9 2628.74      71 2627.09    85.2 2626.29
   102.3 2626.28   134.1 2623.36   171.3 2621.36   181.1 2620.47   188.1 2621.47
   192.9 2623.29   203.3 2623.75   232.6 2622.97   247.8 2623.39   286.5  2621.6
   299.1 2621.72   304.4 2623.14   309.1 2625.52     315 2627.52   332.7  2629.9
     346 2632.55   362.9 2634.43     387 2635.79   423.2 2636.63   443.2 2638.11
   459.3 2640.88   467.3 2642.85   483.3 2644.39   487.3 2645.74   518.2 2652.77
#Mann= 7 ,-1,0
       0      .1       0      10     .12       0     110      .1       0
   171.3    .045       0   188.1      .1       0     270     .12       0
  393.12      .1       0
Bank Sta=171.3,188.1
XS Rating Curve= 0 ,0
Exp/Cntr(USF)=0,0
Exp/Cntr=0.3,0.1

Type RM Length L Ch R = 1 ,76497   ,247.2,252.3,246.4
XS GIS Cut Line= 4
2217968.00953253 643038.282912872217983.49531436643058.480750143
2218227.27111429643378.3907338422218251.02237675643428.789362294
#Sta/Elev= 30
       0 2663.61    27.9 2658.92    43.9 2653.59      59 2649.93    69.1 2645.38
    84.9  2634.8   104.9  2624.3   109.3  2622.5     122 2619.88   134.5 2618.85
   164.6 2621.22   178.4 2621.32   207.7 2619.67   214.9 2621.14   219.32619.903
     230  2618.6   237.8  2620.2   244.8 2622.07   275.3 2620.39     284 2618.93
     319 2621.27   335.6 2619.75   353.1 2619.95   358.9 2621.66   380.9 2633.69
     406 2636.16   427.7  2640.1   439.6 2640.92   448.4 2644.81   483.4 2655.11
#Mann= 3 ,-1,0
       0      .1       0   219.3    .045       0   237.8      .1       0
Bank Sta=219.3,237.8
XS Rating Curve= 0 ,0
Exp/Cntr(USF)=0,0
Exp/Cntr=0.3,0.1

Type RM Length L Ch R = 1 ,76245   ,253.5,255.9,255.7
XS GIS Cut Line= 5
2217803.51379331643122.5265245372217855.39059943643179.252596957
 2217967.3956967643303.7027050322218009.85514534643353.482748262
2218027.47200953643553.850969175
#Sta/Elev= 30
       0 2674.16     5.2 2673.47    14.4 2668.66    22.2 2666.25    74.1 2653.69
    90.1 2648.62   113.9 2636.31   133.3 2630.24   143.8 2625.79   155.2 2616.33
   165.6 2615.32   174.52616.321   191.7 2617.22   203.2 2619.04   209.6 2618.32
   251.6 2619.24   262.9 2617.76   274.3 2619.56   317.5 2619.19   325.5 2617.76
   333.5 2617.96   345.6 2616.56   349.6 2617.73   365.6 2628.68   393.7 2637.28
   413.8  2639.1   417.8 2641.28     426 2643.72   474.1 2652.83   510.9 2658.47
#Mann= 3 ,-1,0
       0      .1       0   155.2    .045       0   174.5      .1       0
Bank Sta=155.2,174.5
XS Rating Curve= 0 ,0
Exp/Cntr(USF)=0,0
Exp/Cntr=0.3,0.1

Type RM Length L Ch R = 1 ,75989   ,221.5,221.1,219.9
XS GIS Cut Line= 2
2217610.46488122643192.9460654362217859.00358652643557.168240848
#Sta/Elev= 30
       0 2674.46    14.8 2669.93    19.7 2667.46    24.3 2665.94    38.8 2665.32
    43.9 2664.42    58.4 2658.71    76.2 2653.89    95.3 2650.27   111.7 2648.32
   123.7 2645.75   135.9  2644.1     154 2639.31   174.1  2631.6   179.5 2628.34
   189.1 2620.71   203.1 2614.06   208.6 2612.82   213.4 2612.71   222.52614.056
   227.9 2614.57   269.1 2614.72   281.2  2616.7   306.5 2618.76   322.4 2621.36
   339.3 2625.68   369.8 2631.47   418.8 2639.82   428.8 2640.98   440.9 2641.19
#Mann= 3 ,-1,0
       0      .1       0   203.1    .045       0   222.5      .1       0
Bank Sta=203.1,222.5
XS Rating Curve= 0 ,0
Exp/Cntr(USF)=0,0
Exp/Cntr=0.3,0.1

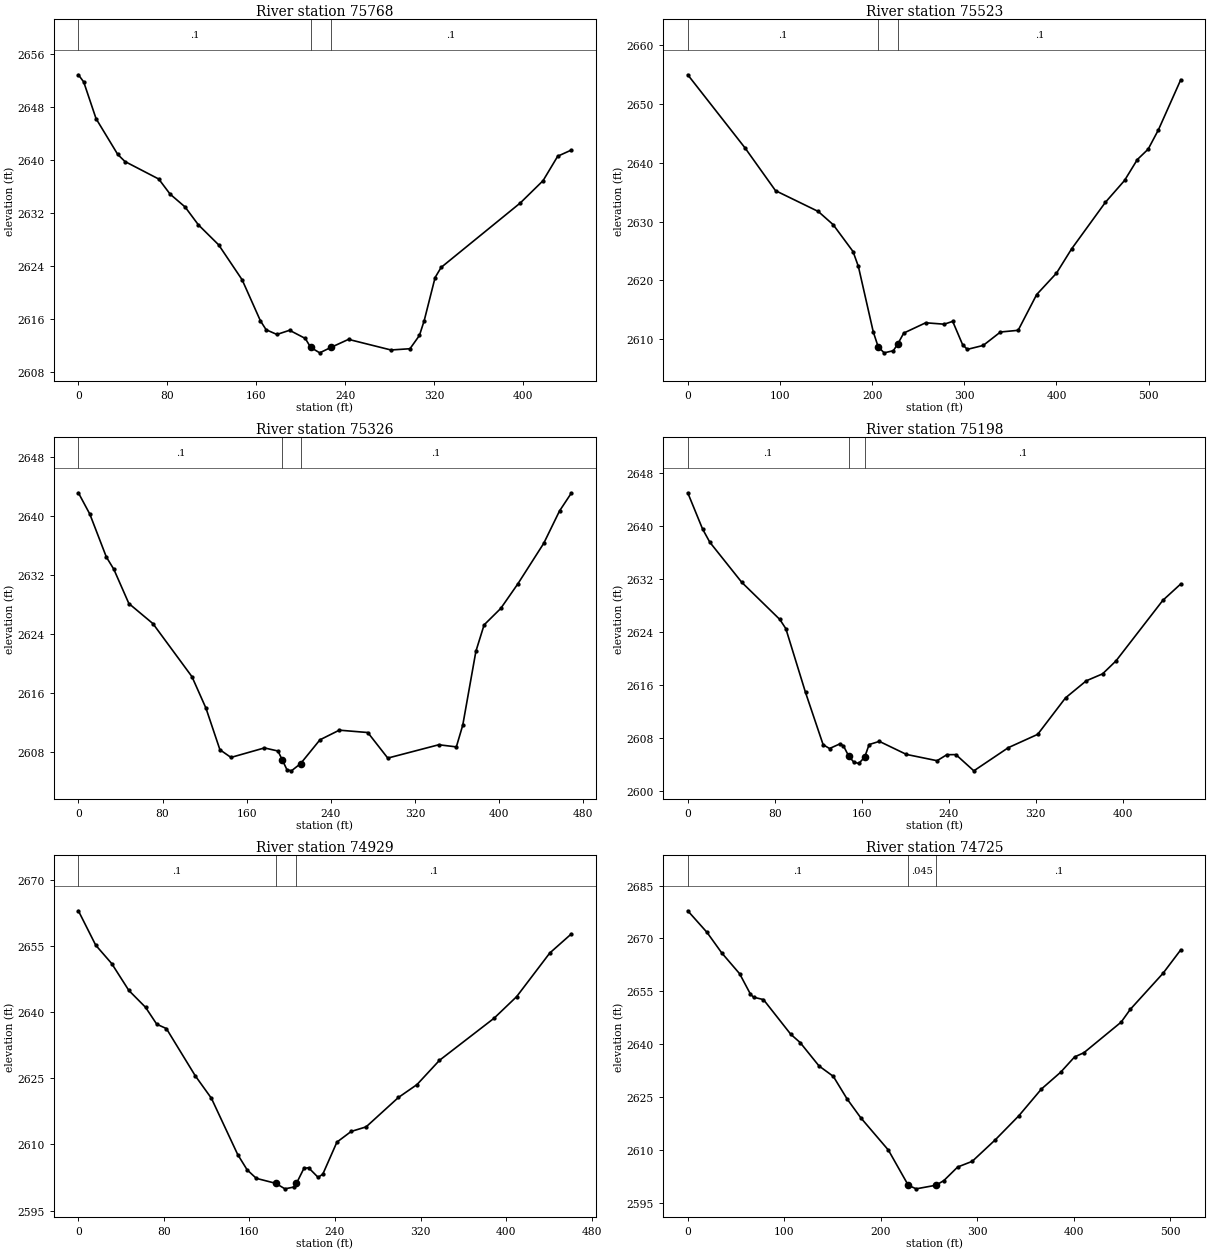
Type RM Length L Ch R = 1 ,75768   ,243,244.2,242
XS GIS Cut Line= 2
2217434.34902315643344.2334566752217707.77323118643693.425818744
#Sta/Elev= 30
       0 2652.85     4.8 2651.77    15.9 2646.24    35.4 2640.85    41.9 2639.78
    72.3 2637.14    82.5 2634.87      96 2632.93   107.9 2630.25   126.2 2627.22
   147.3 2621.96   163.8 2615.76   168.9 2614.43   178.6 2613.72     190 2614.35
   204.1 2613.12     2092611.767   217.1 2610.95   227.1 2611.76     243 2612.98
   281.2 2611.38   298.3 2611.57   306.8 2613.57   311.1 2615.81   320.9  2622.3
   326.3 2623.82   397.5 2633.53     418 2636.89   431.2 2640.58   443.5 2641.51
#Mann= 3 ,-1,0
       0      .1       0     209    .045       0   227.1      .1       0
Bank Sta=209,227.1
XS Rating Curve= 0 ,0
Exp/Cntr(USF)=0,0
Exp/Cntr=0.3,0.1

Type RM Length L Ch R = 1 ,75523   ,201.4,197,190.3
XS GIS Cut Line= 2
2217234.72977961643467.3848966972217557.51966701643893.782552013
#Sta/Elev= 30
       0 2654.95    62.3 2642.48    95.2 2635.25   141.6 2631.71   157.8 2629.46
   179.3  2624.9   185.1 2622.36   201.2 2611.27   206.52608.728     213 2607.68
     223 2608.04     228 2609.24   234.3 2611.04   258.1 2612.79   278.2 2612.55
   287.4 2613.03   298.2 2609.05   303.3 2608.27   320.5 2608.94   339.2 2611.22
   358.4 2611.51   378.5 2617.59     400 2621.23   416.3 2625.33     453 2633.26
   473.8 2636.98   487.7 2640.54   499.4  2642.3   510.6  2645.6   534.8 2654.11
#Mann= 3 ,-1,0
       0      .1       0   206.5    .045       0     228      .1       0
Bank Sta=206.5,228
XS Rating Curve= 0 ,0
Exp/Cntr(USF)=0,0
Exp/Cntr=0.3,0.1

Type RM Length L Ch R = 1 ,75326   ,122.6,128.9,134.8
XS GIS Cut Line= 4
2217097.92681203643680.1738772712217233.49337856643782.300690724
2217301.27666183 643808.510226922217506.43406584643904.310600602
#Sta/Elev= 30
       0 2643.21    10.9 2640.31    26.6 2634.49    33.7 2632.83      48 2628.18
    70.9 2625.45     108 2618.25   121.3 2613.98   134.6 2608.33   145.1 2607.29
   176.9 2608.58   189.8 2608.16     194 2606.92   198.3 2605.63   202.6 2605.47
   211.3 2606.45   229.7 2609.68   248.1 2610.99   275.2 2610.67   294.2  2607.2
   342.7 2609.01   359.4 2608.72   365.5 2611.67     378  2621.7   385.8 2625.28
   401.6 2627.51   417.8 2630.83   442.5 2636.35   457.5 2640.74   468.8 2643.18
#Mann= 3 ,-1,0
       0      .1       0     194    .045       0   211.3      .1       0
Bank Sta=194,211.3
XS Rating Curve= 0 ,0
Exp/Cntr(USF)=0,0
Exp/Cntr=0.3,0.1

Type RM Length L Ch R = 1 ,75198   ,264.9,269,268.4
XS GIS Cut Line= 5
2217046.24328176643723.310412701 2217132.6077868643803.850336588
2217163.82756054643854.0154430972217193.03247122643966.874694909
2217248.37303246644116.670362146
#Sta/Elev= 30
       0 2645.03    13.6 2639.57    20.3 2637.56    49.7  2631.5    84.7 2625.89
    90.2 2624.51   108.3 2614.87   124.5 2606.98   130.4  2606.4     140 2607.11
   143.2  2606.8   147.9  2605.3   152.6 2604.36   157.3 2604.14   162.7  2605.1
   166.8    2607   176.2 2607.48   201.1 2605.51   229.3 2604.56   238.3 2605.47
   246.6 2605.48   263.1 2603.03   294.9 2606.54   321.8 2608.54   347.4 2614.05
   366.5 2616.63   381.5 2617.68   393.8 2619.63   436.9 2628.78   453.4 2631.26
#Mann= 3 ,-1,0
       0      .1       0   147.9    .045       0   162.7      .1       0
Bank Sta=147.9,162.7
XS Rating Curve= 0 ,0
Exp/Cntr(USF)=0,0
Exp/Cntr=0.3,0.1

Type RM Length L Ch R = 1 ,74929   ,204.5,203.7,200.2
XS GIS Cut Line= 2
2216869.38798649643818.4476445772217066.11371325644235.498356342
#Sta/Elev= 30
       0 2663.02    16.2 2655.22    31.2 2651.03    47.2 2644.94    62.8 2641.12
    73.3 2637.28    82.3 2636.29   109.3 2625.58   124.4 2620.48     149 2607.71
   157.8 2604.24   166.4  2602.3   184.52601.176   193.2 2599.92     202 2600.35
     2042601.181   210.9 2604.55   215.3 2604.71   224.2 2602.53   228.6 2603.25
   241.8 2610.52   255.1 2612.94   269.1 2613.98   299.3 2620.65   316.7 2623.58
   337.7 2629.08   388.8 2638.64   409.9 2643.54   440.9 2653.44   461.1 2657.78
#Mann= 3 ,-1,0
       0      .1       0   184.5    .045       0     204      .1       0
Bank Sta=184.5,204
XS Rating Curve= 0 ,0
Exp/Cntr(USF)=0,0
Exp/Cntr=0.3,0.1

Type RM Length L Ch R = 1 ,74725   ,239,239.3,236.3
XS GIS Cut Line= 2
2216639.84817476643880.5859643882216925.44174158644304.457429073
#Sta/Elev= 30
       0 2677.86      20 2671.72    35.2 2665.92    53.8 2659.99      65 2654.21
    68.2 2653.34    78.5 2652.66   106.8 2642.82   116.5 2640.48   136.1 2633.83
   150.9 2630.88   165.2 2624.47   179.3 2619.15     208 2609.96   228.62599.989
   236.8 2598.97   257.32599.995   265.5 2601.31   279.8 2605.16   294.9 2606.77
     319 2612.93   343.2 2619.69   366.6 2627.28   386.6 2632.06     401 2636.39
   410.7 2637.59   449.3 2646.27   458.7 2649.87   492.7 2660.12   511.1 2666.78
#Mann= 3 ,-1,0
       0      .1       0   228.6    .045       0   257.3      .1       0
Bank Sta=228.6,257.3
XS Rating Curve= 0 ,0
Exp/Cntr(USF)=0,0
Exp/Cntr=0.3,0.1

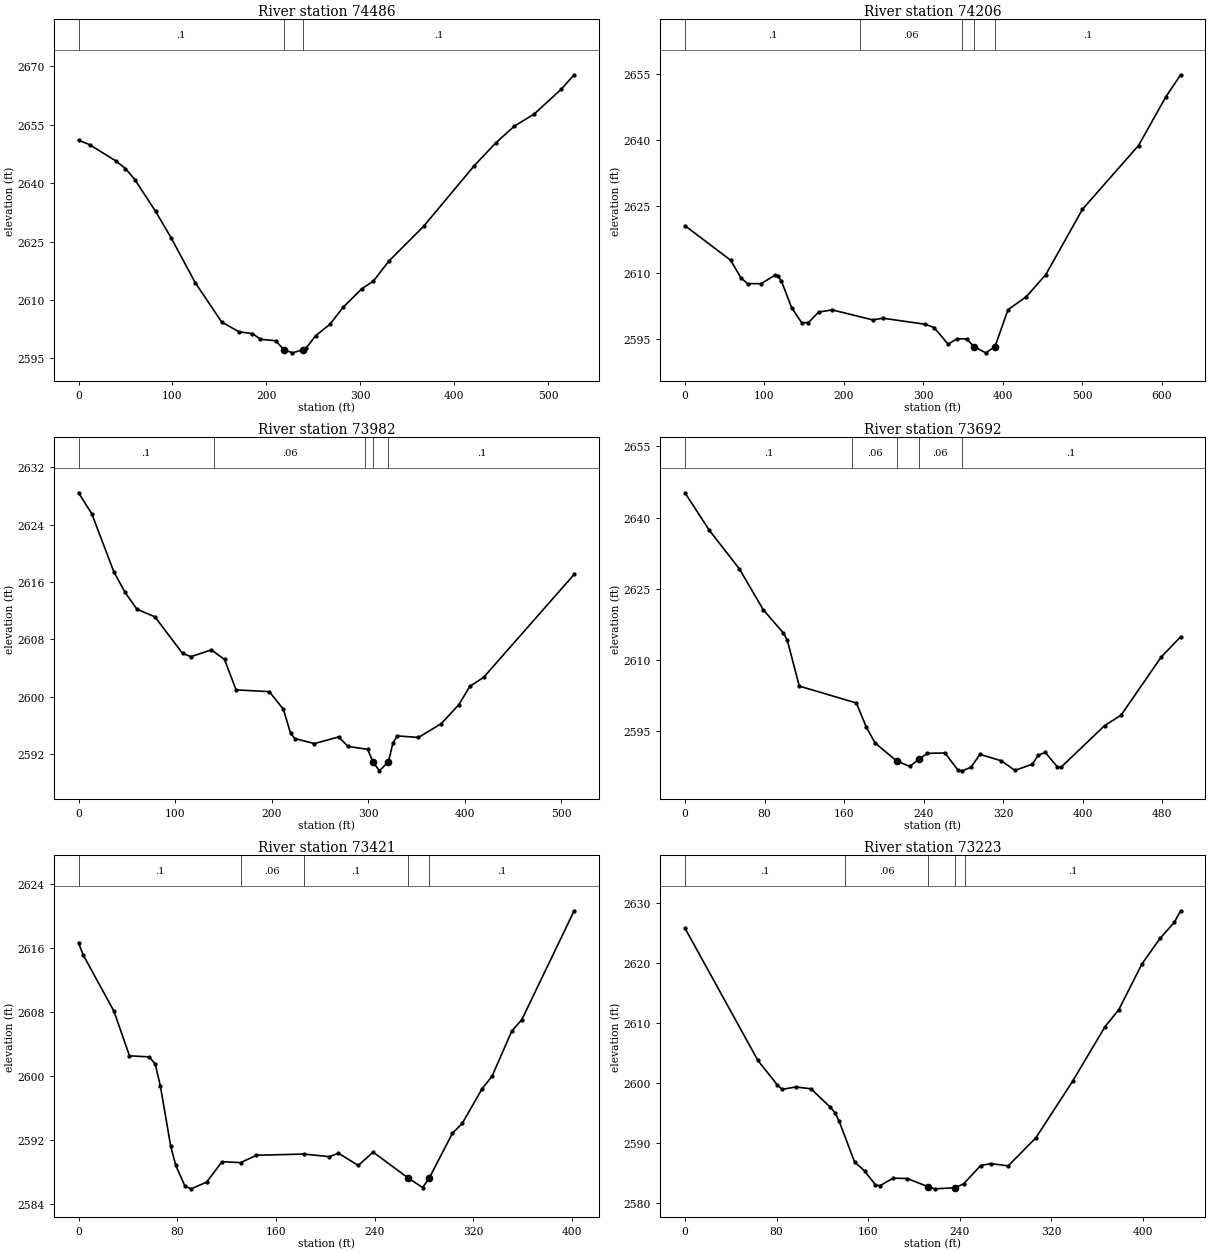
Type RM Length L Ch R = 1 ,74486   ,280.5,280,279.1
XS GIS Cut Line= 2
2216452.88904811644052.1883186582216782.79006926644464.017751488
#Sta/Elev= 30
       0    2651    11.7 2649.89      40 2645.65      50 2643.74      60 2640.89
      82 2632.77    98.6 2625.96   124.3 2614.44   152.4 2604.37   170.9 2601.84
   185.2 2601.39   193.7 2599.94     210 2599.55   218.62597.256   227.8 2596.45
   239.52597.252   242.2 2597.64   252.4 2600.82   267.6 2603.76   281.9 2608.19
   301.8 2612.93   313.9 2614.85   330.3 2619.96   367.3 2628.89   421.3 2644.47
   444.1 2650.29     464 2654.62   485.1 2657.71   513.8 2664.07   527.7  2667.8
#Mann= 3 ,-1,0
       0      .1       0   218.6    .045       0   239.5      .1       0
Bank Sta=218.6,239.5
XS Rating Curve= 0 ,0
Exp/Cntr(USF)=0,0
Exp/Cntr=0.3,0.1

Type RM Length L Ch R = 1 ,74206   ,221.6,223.7,226.2
XS GIS Cut Line= 3
2216078.10535354644249.0845879832216312.24434843644334.186296713
2216567.97208368644607.923000791
#Sta/Elev= 30
       0 2620.64    57.5 2612.78    70.3 2608.81    78.8 2607.46    95.8 2607.46
   112.9 2609.36   117.2 2609.11   121.4 2608.04   134.1 2602.04   146.9 2598.57
   155.4 2598.64   168.2    2601   185.2 2601.51   236.3 2599.23   249.1 2599.61
   302.1 2598.25   313.5  2597.5   331.1 2593.72   342.8 2594.97   354.5 2594.89
     3642593.106   378.5 2591.75     3902593.115   406.5 2601.55   429.5  2604.5
   454.1 2609.54   500.2 2624.38   570.7 2638.85     605 2649.87   623.7 2654.92
#Mann= 5 ,-1,0
       0      .1       0     220     .06       0  349.13      .1       0
     364    .045       0     390      .1       0
Bank Sta=364,390
XS Rating Curve= 0 ,0
Exp/Cntr(USF)=0,0
Exp/Cntr=0.3,0.1

Type RM Length L Ch R = 1 ,73982   ,294.3,290,283.1
XS GIS Cut Line= 6
 2215971.1209116644400.3976857612216165.60775178644472.804054181
2216203.16240204644531.4420168682216239.39934528644592.056540095
2216264.68047923644641.7888839782216342.83934687 644719.21526817
#Sta/Elev= 30
       0 2628.44    13.7 2625.53    36.6 2617.43    48.1 2614.59    60.5 2612.22
    79.2 2611.15   107.8 2606.06   116.5  2605.6   137.7 2606.55   151.3 2605.21
   163.3 2600.97   197.7 2600.73   212.3 2598.27   219.7 2594.93   224.1 2594.19
   244.4 2593.49   269.7 2594.42   279.2 2593.09   299.6 2592.69   305.12590.936
   311.8 2589.69   321.22590.973   325.8 2593.57   330.4 2594.56   352.2 2594.34
     376 2596.28   393.9 2598.88   405.6 2601.47   419.8 2602.72   513.6 2617.07
#Mann= 5 ,-1,0
       0      .1       0     140     .06       0  297.16      .1       0
   305.1    .045       0   321.2      .1       0
Bank Sta=305.1,321.2
XS Rating Curve= 0 ,0
Exp/Cntr(USF)=0,0
Exp/Cntr=0.3,0.1

Type RM Length L Ch R = 1 ,73692   ,272.5,271,258.2
XS GIS Cut Line= 4
2215821.82274198644749.5214703062215969.13841094644735.061036543
 2216160.7391583644822.7274162332216299.85883571644811.483019732
#Sta/Elev= 30
       0 2645.21    24.4 2637.34    54.6 2629.23    78.7 2620.61    98.8 2615.74
   102.8 2614.24   114.9 2604.55   172.3 2600.99   182.3 2595.92   191.1 2592.59
   212.9 2588.77   226.1 2587.66   234.9 2589.11   243.7  2590.4   261.3 2590.48
   274.5 2586.86   278.9 2586.72   287.7  2587.5   296.5 2590.19   317.9 2588.84
   331.7 2586.82   349.3 2588.12     355 2589.97   362.2  2590.6   374.2  2587.6
   378.2  2587.5   421.9 2596.24   438.4 2598.42   478.7 2610.64   498.3 2614.91
#Mann= 5 ,-1,0
       0      .1       0  168.02     .06       0   212.9    .045       0
   234.9     .06       0  278.02      .1       0
Bank Sta=212.9,234.9
XS Rating Curve= 0 ,0
Exp/Cntr(USF)=0,0
Exp/Cntr=0.3,0.1

Type RM Length L Ch R = 1 ,73421   ,198.2,198.3,197.1
XS GIS Cut Line= 3
2215916.58824168644976.5425422342216079.52317952644928.741614585
2216310.46930686644908.621555696
#Sta/Elev= 30
       0  2616.6     3.7 2615.12    28.7 2608.07    41.3  2602.5    57.2 2602.37
    62.1  2601.5    66.3 2598.76    74.6  2591.3    78.8 2588.83    86.2 2586.25
    91.3  2585.9   103.8 2586.74   116.3 2589.29   131.3 2589.17   144.2 2590.09
   182.5 2590.24   203.2 2589.92   210.6 2590.34   226.7 2588.82   238.7 2590.48
   267.32587.233   278.9 2586.06   284.12587.228   302.9 2592.81     311 2594.09
     327 2598.39   335.1 2599.96   351.1  2605.6   359.2 2607.02   401.6  2620.6
#Mann= 5 ,-1,0
       0      .1       0   131.3     .06       0   182.5      .1       0
   267.3    .045       0   284.1      .1       0
Bank Sta=267.3,284.1
XS Rating Curve= 0 ,0
Exp/Cntr(USF)=0,0
Exp/Cntr=0.3,0.1

Type RM Length L Ch R = 1 ,73223   ,217.9,212.5,207.5
XS GIS Cut Line= 4
2215951.81758616645175.3498514472216126.41376719 645116.71188876
2216209.42930987645110.1233536272216373.79202269645091.033773505
#Sta/Elev= 30
       0 2625.74    63.7 2603.72    80.5 2599.69    84.8 2598.91    96.8 2599.31
   110.1    2599     127 2595.92   131.2 2594.98   134.7 2593.59   148.1 2586.83
   156.8 2585.35   166.2 2583.05   170.1 2582.85   181.8 2584.13     194 2584.07
   212.42582.711     218 2582.35   235.52582.525   243.3 2583.16   258.2 2586.23
   267.2 2586.55   282.3 2586.17   306.5 2590.85   338.7 2600.31   366.9 2609.36
   378.9 2612.17   399.1 2619.79   415.1 2624.08   427.3  2626.7   432.9 2628.64
#Mann= 5 ,-1,0
       0      .1       0     140     .06       0   212.4    .045       0
   235.5     .06       0  244.18      .1       0
Bank Sta=212.4,235.5
XS Rating Curve= 0 ,0
Exp/Cntr(USF)=0,0
Exp/Cntr=0.3,0.1

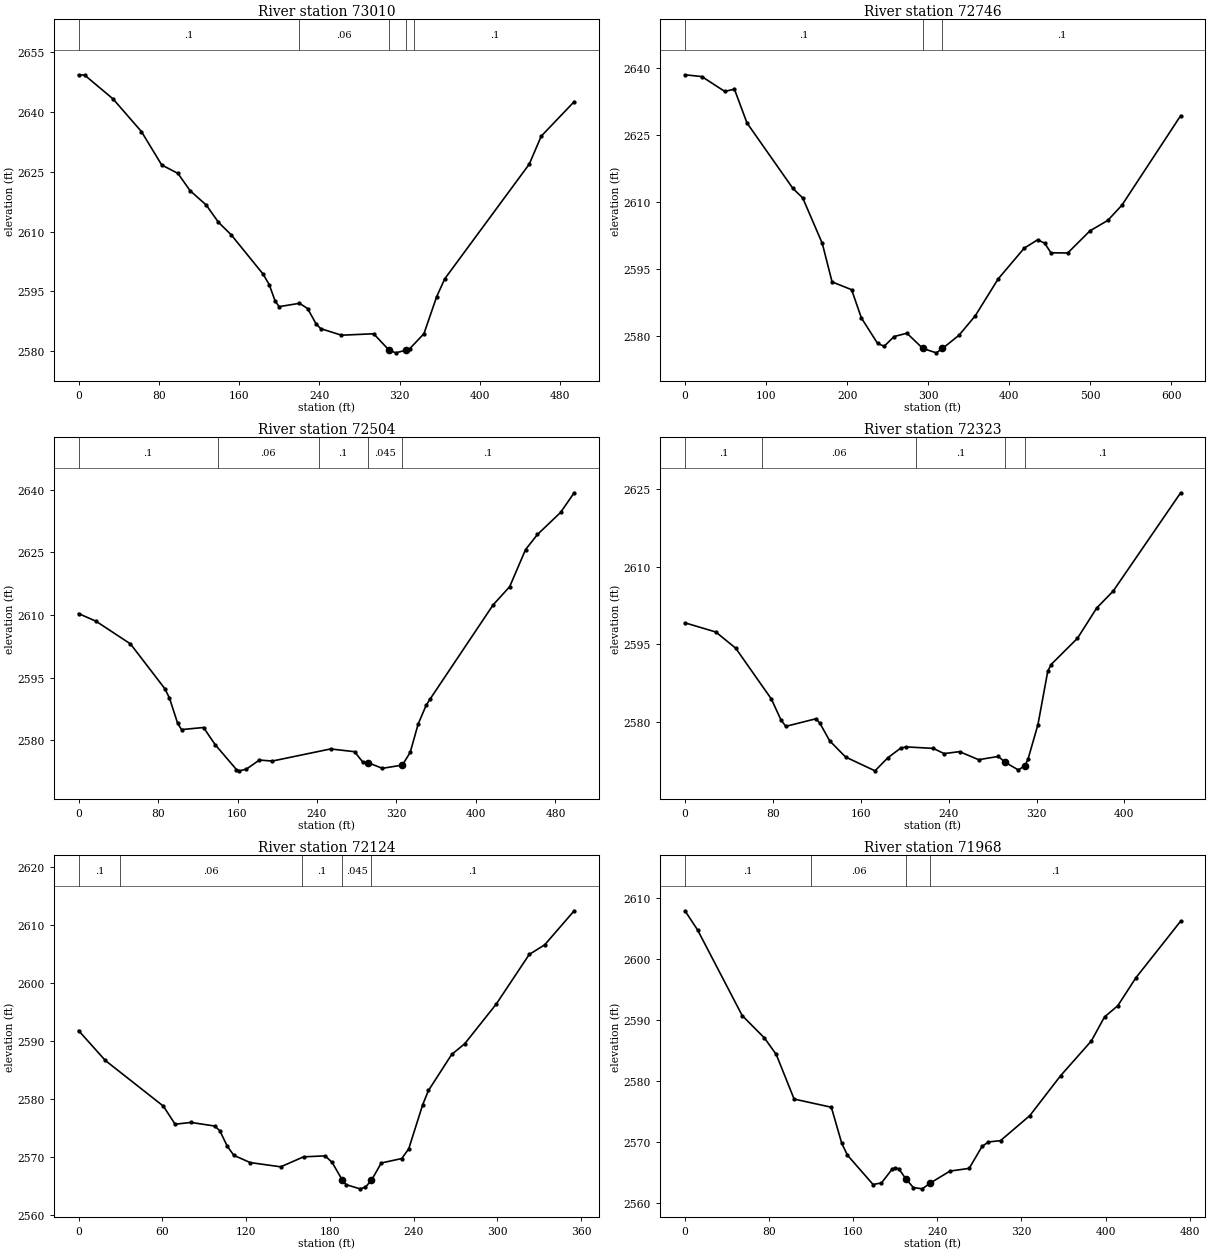
Type RM Length L Ch R = 1 ,73010   ,259,264.1,266.1
XS GIS Cut Line= 4
2215966.11198455645357.8081817952216198.58815655645325.001151203
2216297.09986156 645265.351861932216440.95518201645260.189754421
#Sta/Elev= 30
       0 2649.37     6.1 2649.29    34.4 2643.31    62.7 2635.11    82.9 2626.72
      99 2624.61   111.2 2620.27   127.3 2616.65   139.4 2612.34   152.2 2609.17
   183.9 2599.32     190 2596.69     196  2592.5     200 2591.14   220.2 2591.98
   228.3 2590.66   236.6 2586.87   241.3 2585.62     262 2583.97   294.1 2584.33
   309.52580.197   316.1 2579.54   326.32580.198   330.2 2580.62   344.2 2584.34
   356.9 2593.65     365 2598.15   449.1 2626.91   461.1 2633.96   493.9 2642.61
#Mann= 5 ,-1,0
       0      .1       0     220     .06       0   309.5    .045       0
   326.3     .06       0  334.78      .1       0
Bank Sta=309.5,326.3
XS Rating Curve= 0 ,0
Exp/Cntr(USF)=0,0
Exp/Cntr=0.3,0.1

Type RM Length L Ch R = 1 ,72746   ,240.1,241.9,244.7
XS GIS Cut Line= 4
2216003.31930471645555.4618666962216132.96813908645545.742403722
2216418.47132819645518.0868241492216607.17033436645566.306034036
#Sta/Elev= 30
       0 2638.51    20.9  2638.1      49 2634.78      61 2635.28    76.5  2627.7
   133.2    2613   145.3 2610.87   169.4 2600.68   181.5 2592.03   205.6 2590.28
   217.7 2583.93   237.7 2578.22   245.8 2577.58     258 2579.77   273.9 2580.51
   293.52577.091   310.1 2576.11   317.72577.084   338.2 2580.07   358.3 2584.45
   386.4 2592.69   418.6  2599.6   435.1 2601.47   443.8 2600.72   451.6 2598.56
   472.3 2598.52   499.7 2603.48   521.8 2605.84   539.2 2609.26   611.6 2629.32
#Mann= 3 ,-1,0
       0      .1       0   293.5    .045       0   317.7      .1       0
Bank Sta=293.5,317.7
XS Rating Curve= 0 ,0
Exp/Cntr(USF)=0,0
Exp/Cntr=0.3,0.1

Type RM Length L Ch R = 1 ,72504   ,167.7,181.5,194.2
XS GIS Cut Line= 4
2216055.80062479645670.192398587 2216270.2277814645758.175213476
2216480.86874042645766.8922201552216537.00961905645768.770587838
#Sta/Elev= 30
       0 2610.32    17.7 2608.47    52.3 2603.05    86.9 2592.33    91.5 2590.12
    99.8 2584.02   103.7 2582.55   125.8 2583.05   137.5 2578.95   158.9    2573
     162 2572.68     169  2573.1     182 2575.26     195 2575.02   253.7 2577.92
   277.8 2577.26   285.8 2574.86     2912574.663   305.8 2573.28   325.92574.058
   333.8  2577.1   341.8 2583.88   349.8 2588.34   353.8 2589.85   417.2 2612.38
   433.9 2616.75   449.9 2625.64   461.9 2629.25   485.1 2634.51   498.8 2639.22
#Mann= 5 ,-1,0
       0      .1       0     140     .06       0  241.78      .1       0
     291    .045       0   325.9      .1       0
Bank Sta=291,325.9
XS Rating Curve= 0 ,0
Exp/Cntr(USF)=0,0
Exp/Cntr=0.3,0.1

Type RM Length L Ch R = 1 ,72323   ,198.7,198.8,194.8
XS GIS Cut Line= 3
2216023.54429403645731.1573194532216219.92055502645838.271643625
2216322.57178235 646041.34254987
#Sta/Elev= 30
       0 2599.13    28.1 2597.35    46.2 2594.21    78.6 2584.38    87.5 2580.26
    91.8 2579.07   119.2 2580.54   122.8 2579.69   131.7 2576.27   146.2 2573.13
     173 2570.45   184.7 2572.99   196.3 2574.84   201.2 2575.09     226  2574.8
   235.9 2573.79   249.9 2574.17   267.3 2572.61   285.2 2573.24   291.62572.086
   303.4 2570.63   309.52571.428   312.4 2572.81   321.3  2579.4   330.2  2589.7
   333.2 2591.03   357.3 2596.14   374.9 2602.03   389.8 2605.28   451.2 2624.33
#Mann= 5 ,-1,0
       0      .1       0      70     .06       0     210      .1       0
   291.6    .045       0   309.5      .1       0
Bank Sta=291.6,309.5
XS Rating Curve= 0 ,0
Exp/Cntr(USF)=0,0
Exp/Cntr=0.3,0.1

Type RM Length L Ch R = 1 ,72124   ,156.8,155.8,154.4
XS GIS Cut Line= 4
2215960.37446488645811.1140341572216073.79656046645933.046882533
2216124.40807863646000.8301657992216199.37832168646072.929225213
#Sta/Elev= 30
       0 2591.85    19.2 2586.68    60.8  2578.8    69.2 2575.68    80.6 2575.99
    97.5 2575.37   101.2 2574.57   106.6 2571.87   111.3 2570.31     123 2569.06
   144.9 2568.33   161.2 2570.05   176.7 2570.22   181.7 2569.08   189.12566.004
   191.7 2565.26   201.6 2564.53   205.5 2564.81   209.92566.012   216.9 2568.99
   231.6 2569.76   236.6 2571.45   246.6 2579.06   250.7  2581.5   267.4 2587.73
   276.7 2589.57   299.3 2596.42   322.9 2604.97     334 2606.64   355.1 2612.51
#Mann= 5 ,-1,0
       0      .1       0      30     .06       0     160      .1       0
   189.1    .045       0   209.9      .1       0
Bank Sta=189.1,209.9
XS Rating Curve= 0 ,0
Exp/Cntr(USF)=0,0
Exp/Cntr=0.3,0.1

Type RM Length L Ch R = 1 ,71968   ,205.9,197.5,190.8
XS GIS Cut Line= 3
2215806.82548815645856.122947632 2215999.8544265646078.162015449
2216169.45210644646129.487629115
#Sta/Elev= 30
       0  2607.9      12 2604.75    54.4 2590.71    75.6 2587.02    86.8 2584.32
   103.8    2577   139.2 2575.66   149.1 2569.74   154.5  2567.8   178.9 2562.98
   186.9 2563.24   197.3 2565.56   200.2 2565.69   203.3 2565.57   209.92563.948
   217.2 2562.48   225.7 2562.27   233.42563.229     252 2565.18   270.3 2565.63
   282.5 2569.22   288.6 2569.96   300.1 2570.18     328 2574.29   357.2 2580.83
   386.5 2586.54     399 2590.48   411.6 2592.31   428.9 2596.92   471.4 2606.19
#Mann= 4 ,-1,0
       0      .1       0     120     .06       0   209.9    .045       0
   233.4      .1       0
Bank Sta=209.9,233.4
XS Rating Curve= 0 ,0
Exp/Cntr(USF)=0,0
Exp/Cntr=0.3,0.1