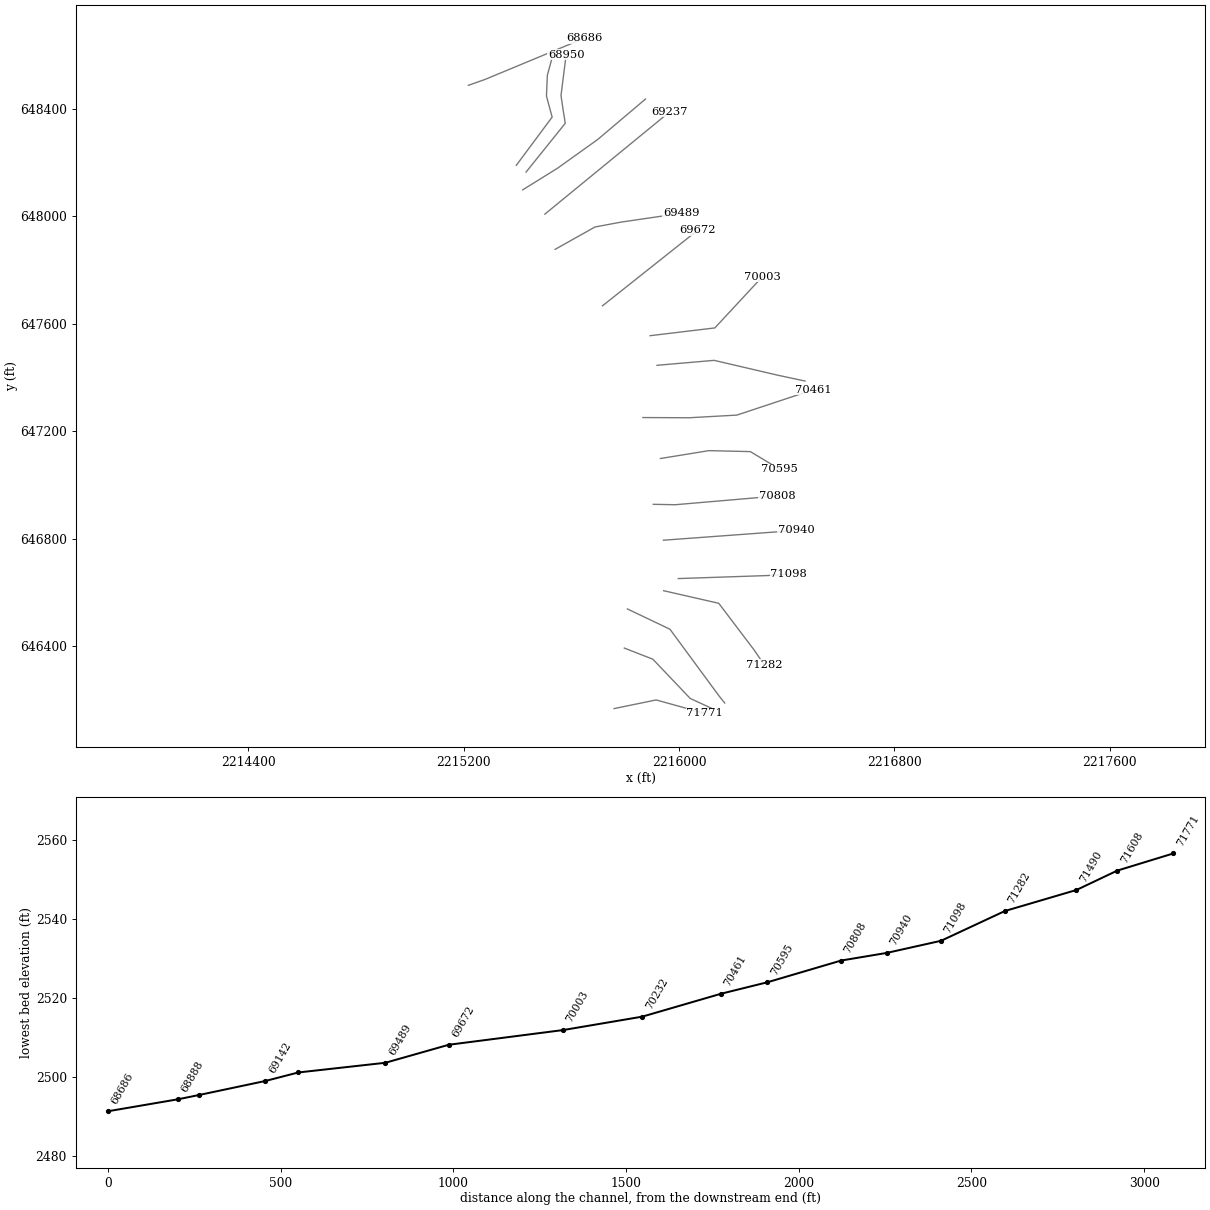
HEC-RAS study RFMIDDLERV.prj: RFMIDDLERV

--- RFMIDDLERV.g01 (geometry) --- (continued)

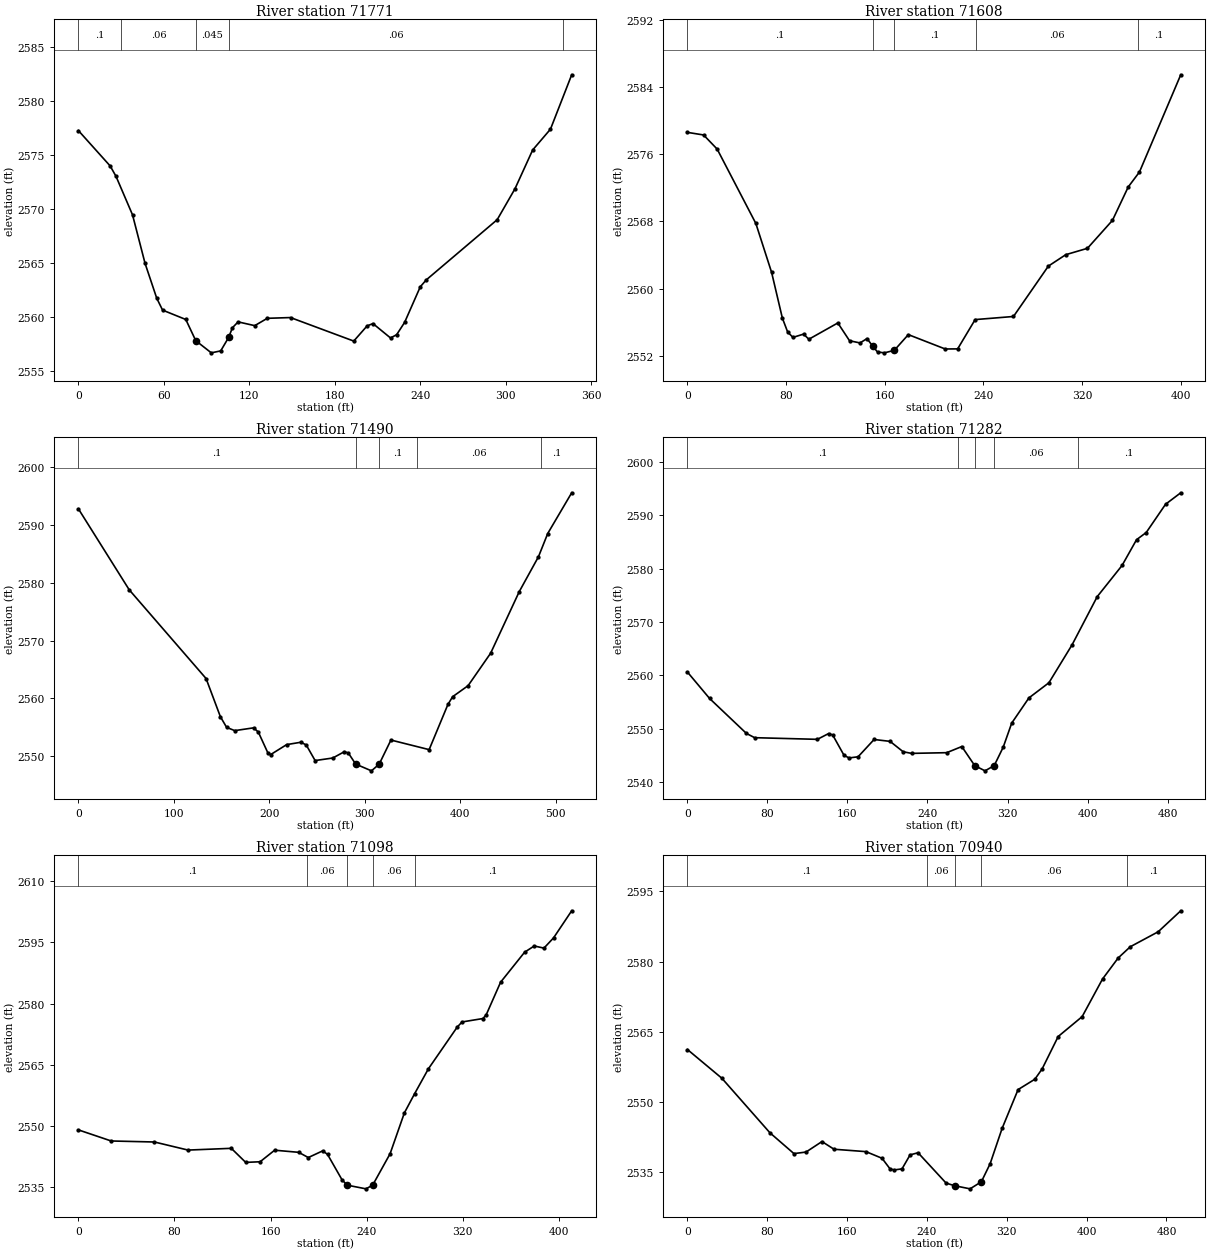
Type RM Length L Ch R = 1 ,71771   ,175.4,162.6,153.3
XS GIS Cut Line= 3
2215758.33203685646168.8835330712215914.91120971646201.063915223
2216094.54498471646151.112277256
#Sta/Elev= 30
       0 2577.29    22.3 2574.01    26.4 2573.05      38 2569.48    46.8 2564.98
      55 2561.75    59.1 2560.65    75.4 2559.78    82.42557.817    93.3 2556.69
    99.9 2556.87   105.52558.122   108.1 2559.01   112.1 2559.56   123.8 2559.21
   132.6 2559.89   148.9 2559.96   193.3 2557.78   202.7 2559.19   206.8  2559.4
   219.1 2558.07   223.4 2558.37     229 2559.51     240 2562.81   244.2 2563.45
     294 2569.03   306.5  2571.9   318.9 2575.49   331.4 2577.42   346.3 2582.46
#Mann= 5 ,-1,0
       0      .1       0      30     .06       0    82.4    .045       0
   105.5     .06       0  339.85      .1       0
Bank Sta=82.4,105.5
XS Rating Curve= 0 ,0
Exp/Cntr(USF)=0,0
Exp/Cntr=0.3,0.1

Type RM Length L Ch R = 1 ,71608   ,116.9,118.1,117.2
XS GIS Cut Line= 4
2215796.46669782646393.9426956072215902.60799882646352.434924266
2216041.36254873646206.5647564122216118.44840979646170.986666692
#Sta/Elev= 30
       0  2578.6    13.1 2578.29    24.1 2576.61    55.5 2567.75    68.3 2561.91
      77 2556.48    81.3 2554.82    85.6 2554.18    94.2 2554.57    98.5 2553.96
     122  2555.9   131.5 2553.78     140 2553.52   145.7 2554.04   150.32553.134
   154.2 2552.44   159.8 2552.34   167.82552.636   179.2 2554.51   209.1  2552.8
   219.2 2552.81   233.4  2556.3   264.5 2556.67   292.8 2562.67   306.9 2564.03
   324.5 2564.79   344.8 2568.12   357.6  2572.1   366.7 2573.88   400.2 2585.46
#Mann= 5 ,-1,0
       0      .1       0   150.3    .045       0   167.8      .1       0
  233.97     .06       0  365.29      .1       0
Bank Sta=150.3,167.8
XS Rating Curve= 0 ,0
Exp/Cntr(USF)=0,0
Exp/Cntr=0.3,0.1

Type RM Length L Ch R = 1 ,71490   ,206.1,207.4,207
XS GIS Cut Line= 4
2215808.11291024646539.2865991392215965.98406723646464.022772044
 2216149.4508206646214.5802896272216169.58601169646189.589433955
#Sta/Elev= 30
       0 2592.79    53.2 2578.78   133.7 2563.42   148.7 2556.81   155.2 2554.97
   163.7  2554.4   183.4 2554.88   188.4 2554.16   198.5 2550.52   201.4 2550.26
   218.1 2551.98     233 2552.39   238.6 2551.92   247.9 2549.22   266.4 2549.66
   278.6 2550.76   282.7 2550.52   290.42548.608   306.9 2547.44     3152548.598
   327.3 2552.77   367.3 2551.11     387 2558.94   391.9 2560.27   408.1 2562.18
   431.7  2567.8   461.7 2578.47   481.8  2584.5   491.5 2588.52   516.6 2595.57
#Mann= 5 ,-1,0
       0      .1       0   290.4    .045       0     315      .1       0
  354.89     .06       0  484.54      .1       0
Bank Sta=290.4,315
XS Rating Curve= 0 ,0
Exp/Cntr(USF)=0,0
Exp/Cntr=0.3,0.1

Type RM Length L Ch R = 1 ,71282   ,173.5,184.8,192.5
XS GIS Cut Line= 4
2215942.64231398 646607.16286546 2216147.4121254646560.383766004
2216279.36358349646385.954783734 2216315.5146679646332.631934231
#Sta/Elev= 30
       0 2560.61    22.1 2555.67      59 2549.11    67.2 2548.32   129.9 2548.01
   141.1 2549.09   145.2 2548.83   156.6    2545   161.6 2544.53   170.6 2544.74
   186.6 2547.98   202.6 2547.63   215.7 2545.68   224.1 2545.38   259.2 2545.51
   274.3 2546.66   287.22543.095   297.5 2542.11   306.72543.089   315.7 2546.54
   324.2 2551.05   341.4 2555.77   361.4 2558.61   384.6 2565.73   409.7 2574.74
   434.5 2580.57     449  2585.4   458.7 2586.75     478 2592.04   493.2 2594.19
#Mann= 5 ,-1,0
       0      .1       0  270.05     .06       0   287.2    .045       0
   306.7     .06       0  390.05      .1       0
Bank Sta=287.2,306.7
XS Rating Curve= 0 ,0
Exp/Cntr(USF)=0,0
Exp/Cntr=0.3,0.1

Type RM Length L Ch R = 1 ,71098   ,156.3,157.2,157.1
XS GIS Cut Line= 3
2215996.91619635646652.297688793 2216327.2587594646663.504787055
2216407.30946127646668.307829167
#Sta/Elev= 30
       0 2549.03    27.3 2546.31    63.3 2546.06    91.3 2544.08   127.3 2544.51
   139.3 2541.06   151.3 2541.22   163.4 2544.05   183.4 2543.53   191.4 2542.25
   203.4 2543.89   207.4 2543.03   219.4 2536.84   223.72535.487   239.4 2534.58
     2452535.485   259.5 2543.18   271.4  2553.2     280 2557.94   291.4    2564
   315.4 2574.23   319.4 2575.48   336.8 2576.32   339.5 2577.22   351.5 2585.22
   371.5 2592.58   379.5  2594.1   387.6 2593.58   395.6 2596.09   410.7 2602.73
#Mann= 5 ,-1,0
       0      .1       0     190     .06       0   223.7    .045       0
     245     .06       0     280      .1       0
Bank Sta=223.7,245
XS Rating Curve= 0 ,0
Exp/Cntr(USF)=0,0
Exp/Cntr=0.3,0.1

Type RM Length L Ch R = 1 ,70940   ,131.9,132.1,131.9
XS GIS Cut Line= 2
2215941.72217629 646794.924251932216434.71491149646831.274866106
#Sta/Elev= 30
       0 2561.24    34.5 2555.11    82.7 2543.46   106.7 2539.03   118.8 2539.36
   134.8  2541.6   146.9 2539.96   178.9 2539.45     195 2538.03     203 2535.77
     207 2535.54     215 2535.77   223.1 2538.76   231.1 2539.21   259.2 2532.73
   267.82532.172   283.2 2531.51   294.52533.016   303.3 2536.87   315.3 2544.41
   331.3 2552.69   348.1  2554.9   355.4  2557.1   371.5 2564.02   395.5 2568.26
   415.9 2576.28   431.6 2580.78   443.7 2583.17   471.7 2586.37   494.3 2590.85
#Mann= 5 ,-1,0
       0      .1       0     240     .06       0   267.8    .045       0
   294.5     .06       0     440      .1       0
Bank Sta=267.8,294.5
XS Rating Curve= 0 ,0
Exp/Cntr(USF)=0,0
Exp/Cntr=0.3,0.1

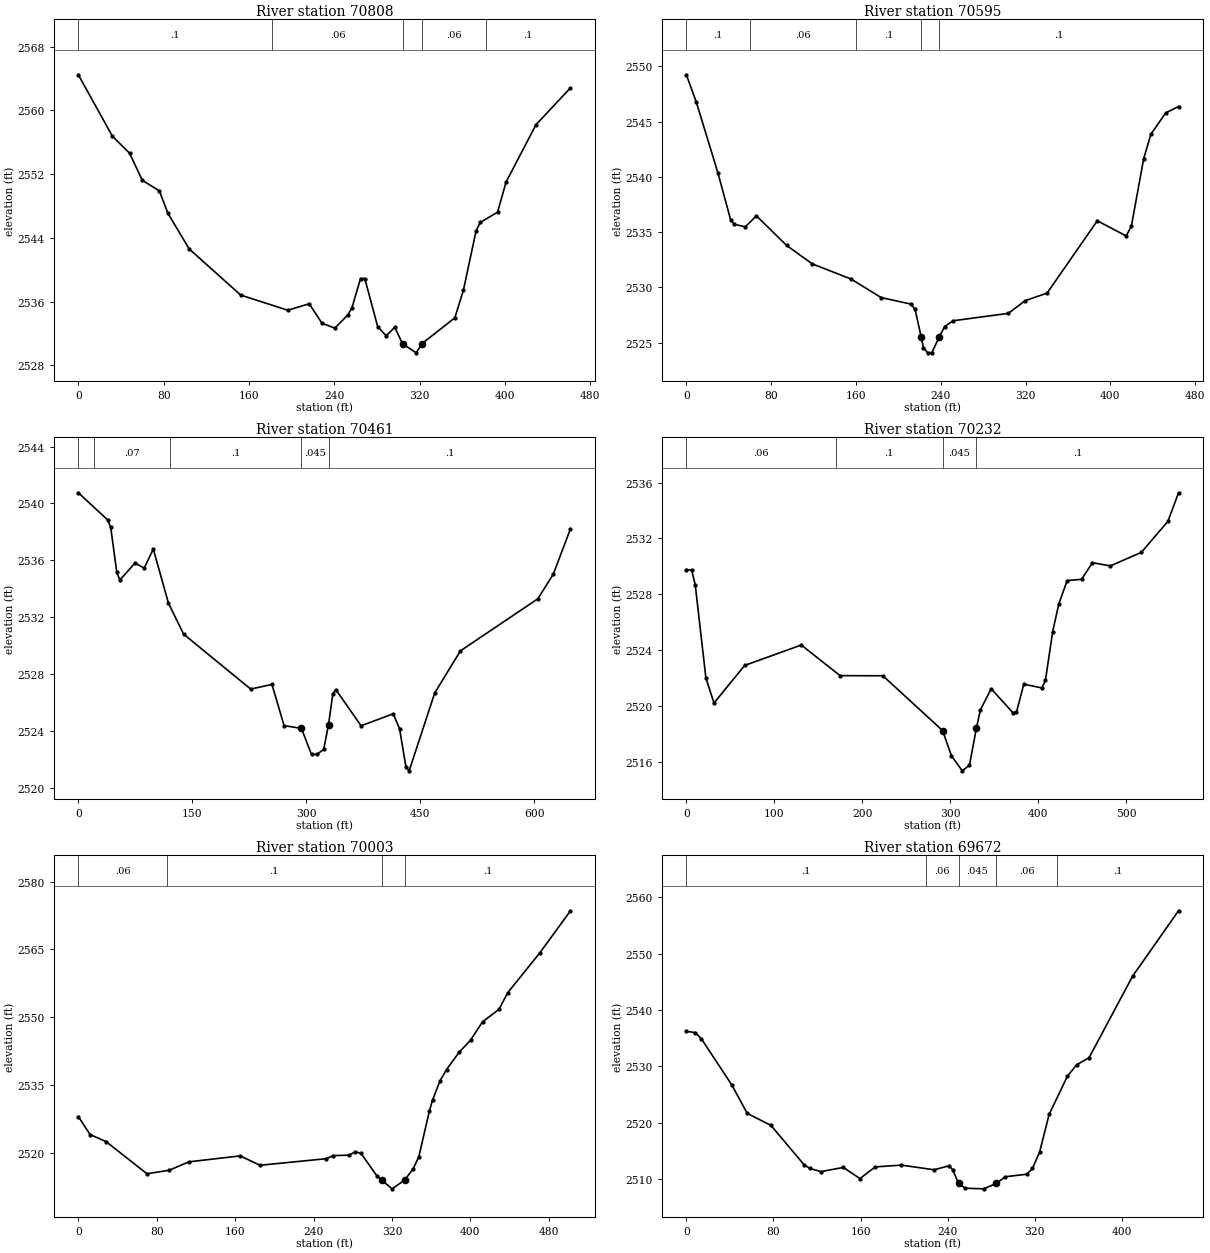
Type RM Length L Ch R = 1 ,70808   ,210.1,213.3,209.2
XS GIS Cut Line= 3
2215904.22893912646928.3686701822215986.07139053646926.899878041
2216364.30211116646959.435854008
#Sta/Elev= 30
       0 2564.46      32 2556.74      48 2554.63      60 2551.22      76  2549.9
      84 2547.07     104 2542.61   152.2 2536.83   196.4 2534.92   216.5 2535.74
   228.5 2533.29   240.5 2532.68   252.6 2534.32   256.6 2535.24   264.6  2538.9
   268.6  2538.9   280.7 2532.87   288.7 2531.71   296.7 2532.79     304 2530.72
   316.8 2529.58   322.32530.741     353 2533.97     361  2537.4     373 2544.89
     377 2545.95   393.1 2547.22   401.1 2551.01   429.2 2558.21   461.5 2562.82
#Mann= 5 ,-1,0
       0      .1       0  181.86     .06       0     304    .045       0
   322.3     .06       0  381.86      .1       0
Bank Sta=304,322.3
XS Rating Curve= 0 ,0
Exp/Cntr(USF)=0,0
Exp/Cntr=0.3,0.1

Type RM Length L Ch R = 1 ,70595   ,131.3,134,136.7
XS GIS Cut Line= 4
2215930.88416911647098.7114523742216110.97079609647127.993830745
2216264.70328253647124.3335334482216374.51220143647058.448182114
#Sta/Elev= 30
       0 2549.23     9.4 2546.76    29.7 2540.39    41.8 2536.11    45.1 2535.72
    55.6 2535.48    66.1 2536.48    94.5 2533.81   118.8 2532.13   155.3 2530.77
   183.7 2529.09   211.7  2528.5   215.7 2528.05   221.6 2525.51   223.7 2524.55
   227.7 2524.09   231.7 2524.12   238.52525.516   243.7 2526.47   251.7 2526.99
   303.8 2527.66   319.7 2528.81   340.3 2529.49   387.7 2536.03   414.9 2534.66
   419.8 2535.53   431.4 2541.62   438.2 2543.85   452.2 2545.78   464.3 2546.36
#Mann= 5 ,-1,0
       0      .1       0      60     .06       0     160      .1       0
   221.6    .045       0   238.5      .1       0
Bank Sta=221.6,238.5
XS Rating Curve= 0 ,0
Exp/Cntr(USF)=0,0
Exp/Cntr=0.3,0.1

Type RM Length L Ch R = 1 ,70461   ,229.7,228.6,220.1
XS GIS Cut Line= 4
 2215865.5930012647250.9694137682216037.34035409647250.213802524
2216214.57194918647260.096605225 2216497.6669864647354.007934263
#Sta/Elev= 30
       0 2540.75    38.6 2538.84    42.6 2538.32    50.6 2535.16    54.6 2534.61
    74.6 2535.81    86.6 2535.45    98.6 2536.79   118.6 2532.98   138.6  2530.8
   226.8 2526.94   254.7 2527.27   270.7 2524.37   293.52524.177   306.8 2522.34
   313.9 2522.35   322.8  2522.7   329.22524.447   334.8 2526.62   338.8  2526.9
     372 2524.36   414.2  2525.2   422.6 2524.16     431 2521.46   435.2 2521.19
   468.9 2526.67   502.7 2529.63   604.5 2533.29   624.9 2535.03   647.5 2538.22
#Mann= 5 ,-1,0
       0     .05       0      20     .07       0     120      .1       0
   293.5    .045       0   329.2      .1       0
Bank Sta=293.5,329.2
XS Rating Curve= 0 ,0
Exp/Cntr(USF)=0,0
Exp/Cntr=0.3,0.1

Type RM Length L Ch R = 1 ,70232   ,212.4,229,242.2
XS GIS Cut Line= 4
2215918.07617905647445.2750020842216130.30045422647463.621541622
2216365.29154064647408.7170821772216467.77986494647386.755298399
#Sta/Elev= 30
       0 2529.78     6.1 2529.72    10.1 2528.69    22.2 2522.03    31.4 2520.23
    66.3 2522.92   130.6 2524.38   174.7 2522.19   223.3 2522.18   291.12518.264
   301.2 2516.46   313.5 2515.38   321.7 2515.79   329.62518.443   334.1 2519.74
   346.4 2521.25     371 2519.54   375.1 2519.58   383.4 2521.58   403.9 2521.31
     408 2521.85   416.2 2525.33   423.1  2527.3   432.7 2528.99   449.1 2529.08
   461.4 2530.27   481.8 2530.04     517 2531.01   547.2 2533.23   559.2 2535.27
#Mann= 4 ,-1,0
       0     .06       0     170      .1       0   291.1    .045       0
   329.6      .1       0
Bank Sta=291.1,329.6
XS Rating Curve= 0 ,0
Exp/Cntr(USF)=0,0
Exp/Cntr=0.3,0.1

Type RM Length L Ch R = 1 ,70003   ,332.6,331,325.4
XS GIS Cut Line= 3
2215892.21214266647555.3334794332216132.86274043647584.225642942
2216309.43548201647774.634308299
#Sta/Elev= 30
       0    2528      12 2524.01    28.2 2522.47      70 2515.33    92.6  2516.1
   112.8 2517.97   165.1 2519.29   185.3 2517.21   253.1 2518.67     260 2519.36
   276.5 2519.44   282.5 2520.22   288.4 2519.84   304.8 2514.78   309.52513.934
   320.1 2511.99   332.92513.929   341.4 2516.35   347.3 2519.07   358.2 2529.27
   361.4 2531.67   369.1 2535.97   375.6 2538.39   388.4 2542.22   400.2 2544.93
   412.4 2548.99   429.2 2551.75   437.9 2555.38   470.8 2564.25   502.1 2573.57
#Mann= 4 ,-1,0
       0     .06       0      90      .1       0   309.5    .045       0
   332.9      .1       0
Bank Sta=309.5,332.9
XS Rating Curve= 0 ,0
Exp/Cntr(USF)=0,0
Exp/Cntr=0.3,0.1

Type RM Length L Ch R = 1 ,69672   ,187.6,183.7,178.9
XS GIS Cut Line= 2
2215715.37412671647666.3815500222216069.19733636 647947.48563584
#Sta/Elev= 30
       0 2536.22     8.3 2535.98    13.9 2534.87    41.9 2526.65    55.9 2521.66
    77.7 2519.52   108.3  2512.5   113.4  2511.9   123.6 2511.32   144.1 2512.07
   159.4 2510.09   173.4 2512.16   197.4 2512.48   227.5 2511.65   241.1 2512.36
   244.5 2511.67   249.92509.246   255.9 2508.38     273 2508.27   284.72509.238
   292.9 2510.41   312.7 2510.87   317.8 2511.89   324.3 2514.75   333.1 2521.47
   349.9 2528.25   358.4 2530.28   369.8 2531.54   409.7 2545.98   451.9  2557.6
#Mann= 5 ,-1,0
       0      .1       0     220     .06       0   249.9    .045       0
   284.7     .06       0     340      .1       0
Bank Sta=249.9,284.7
XS Rating Curve= 0 ,0
Exp/Cntr(USF)=0,0
Exp/Cntr=0.3,0.1

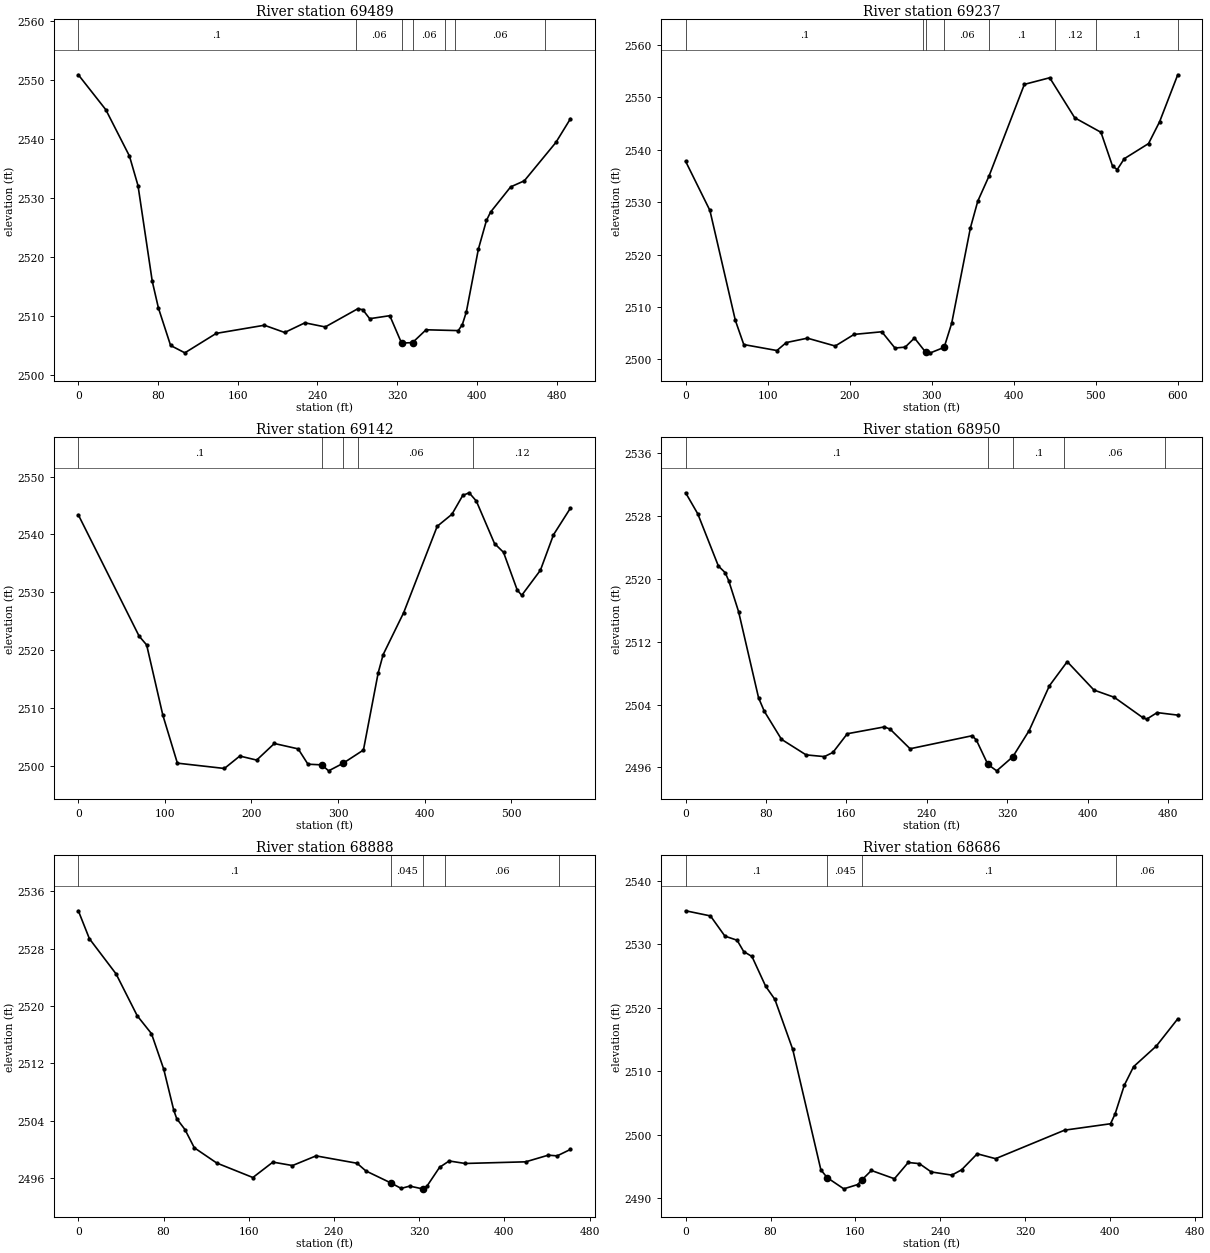
Type RM Length L Ch R = 1 ,69489   ,248.4,252,255.8
XS GIS Cut Line= 4
2215539.45734567647876.3889937122215687.67679175647959.536487852
2215784.38094254647977.612030056 2216007.5588506648010.371397991
#Sta/Elev= 30
       0 2550.86    27.6 2544.93    51.3 2537.08    59.9 2532.06    74.2 2515.83
    80.4  2511.3    92.6 2504.96   106.9 2503.71   138.4 2507.01   186.7 2508.39
   207.1 2507.16   227.4  2508.8   247.8  2508.1   280.2 2511.16   285.4 2511.04
   292.4  2509.5   312.6 2510.01   324.42505.366   335.42505.443     349 2507.62
   381.3 2507.48   385.4  2508.5   389.4 2510.64   401.5  2521.3   409.6 2526.16
   413.7 2527.57   433.9 2531.85   447.6 2532.88   479.3 2539.39   493.9 2543.41
#Mann= 7 ,-1,0
       0      .1       0  278.33     .06       0   324.4    .045       0
   335.4     .06       0  368.33      .1       0  378.33     .06       0
  468.33      .1       0
Bank Sta=324.4,335.4
XS Rating Curve= 0 ,0
Exp/Cntr(USF)=0,0
Exp/Cntr=0.3,0.1

Type RM Length L Ch R = 1 ,69237   ,96.1,95.1,93.9
XS GIS Cut Line= 2
2215501.32036028648007.3373212082215965.28608437648387.778915768
#Sta/Elev= 30
       0 2537.81    29.6 2528.44    60.6 2507.47    70.9 2502.84   111.3  2501.7
   122.7 2503.22   148.5 2504.06   182.4 2502.56   205.4 2504.78   239.2 2505.28
   255.2 2502.18   267.7 2502.35     279 2504.09   292.7 2501.37   298.5 2501.26
   315.22502.308   324.4 2506.91   347.2  2525.1   356.2 2530.21     370 2535.03
     413  2552.5   443.9 2553.76   474.4 2546.12   506.4 2543.35   520.6 2536.85
   526.3 2536.25   534.8 2538.31   564.4  2541.2   577.9 2545.37     600 2554.33
#Mann= 8 ,-1,0
       0      .1       0     290     .06       0   292.7    .045       0
   315.2     .06       0     370      .1       0     450     .12       0
     500      .1       0     600     .12       0
Bank Sta=292.7,315.2
XS Rating Curve= 0 ,0
Exp/Cntr(USF)=0,0
Exp/Cntr=0.3,0.1

Type RM Length L Ch R = 1 ,69142   ,183.1,191.5,204.8
XS GIS Cut Line= 4
2215419.03424973648097.6517277462215548.60877403648178.178268266
2215697.94890372648285.0589493212215875.10729286648435.131138473
#Sta/Elev= 30
       0 2543.39    70.2 2522.41    78.9 2520.89    97.6 2508.74   114.4 2500.44
   168.7 2499.52   186.5 2501.67     206 2500.97   226.4 2503.84   253.9 2502.91
   265.2 2500.26   281.22500.143   289.1 2499.11   305.52500.393   329.3 2502.71
   346.4 2516.11   352.1 2519.23   375.8 2526.48   414.5 2541.41   431.5 2543.49
     444 2546.75   451.4 2547.21   459.7 2545.78   480.7 2538.43   491.1 2536.91
   506.9  2530.4   512.1 2529.47   533.7 2533.81   548.8 2539.94   568.4 2544.56
#Mann= 5 ,-1,0
       0      .1       0   281.2    .045       0   305.5      .1       0
  322.56     .06       0   456.2     .12       0
Bank Sta=281.2,305.5
XS Rating Curve= 0 ,0
Exp/Cntr(USF)=0,0
Exp/Cntr=0.3,0.1

Type RM Length L Ch R = 1 ,68950   ,61.7,62,62.1
XS GIS Cut Line= 5
 2215431.4729341648163.7548893652215577.07956055648344.939605536
 2215569.8321719648390.4004979572215561.26707623648448.379607131
2215580.37382812648599.915915202
#Sta/Elev= 30
       0 2530.95    12.1 2528.27    32.6 2521.63    39.4 2520.78    42.9 2519.76
    52.7 2515.83    72.6 2504.86    78.3 2503.15    95.4 2499.58   119.9  2497.6
   138.1 2497.38   146.6 2497.91   160.9 2500.29   197.8 2501.16   203.5 2500.88
   223.4 2498.38   285.3 2500.04   289.4 2499.48   300.82496.394   309.6 2495.57
   325.62497.354   341.9 2500.69   362.1  2506.4   379.8 2509.46   406.4 2505.85
   426.6 2504.93   454.8 2502.36   458.8 2502.14   469.3 2502.98   489.8 2502.66
#Mann= 5 ,-1,0
       0      .1       0   300.8    .045       0   325.6      .1       0
  377.09     .06       0  477.09      .1       0
Bank Sta=300.8,325.6
XS Rating Curve= 0 ,0
Exp/Cntr(USF)=0,0
Exp/Cntr=0.3,0.1

Type RM Length L Ch R = 1 ,68888   ,218.9,202.3,180.9
XS GIS Cut Line= 5
2215395.23599087648188.7913228722215528.32440056648367.999478503
2215507.24108814648446.403046591 2215510.5353557648523.488907653
2215531.61866813648601.233622228
#Sta/Elev= 30
       0 2533.27    10.4 2529.37    35.4 2524.47    55.3 2518.62    68.7 2516.12
    80.2 2511.16    89.6 2505.44    92.4 2504.26   100.1 2502.75   108.9  2500.2
     130 2498.07   163.9 2496.05   182.7  2498.2   201.1 2497.72   223.2 2499.07
   261.7 2498.04     270 2496.97     2942495.254   303.1 2494.53   311.2 2494.85
   323.1 2494.47   323.62494.514   327.2 2494.81   339.2 2497.47   348.2 2498.36
   363.2 2498.01   420.1 2498.24   441.3 2499.17   449.6 2499.07   462.1 2499.97
#Mann= 5 ,-1,0
       0      .1       0     294    .045       0   323.6      .1       0
  344.41     .06       0  451.57      .1       0
Bank Sta=294,323.6
XS Rating Curve= 0 ,0
Exp/Cntr(USF)=0,0
Exp/Cntr=0.3,0.1

Type RM Length L Ch R = 1 ,68686   ,138.7,144.1,147.1
XS GIS Cut Line= 3
2215217.26745104648486.2631194552215278.72429454  648507.9537701
2215646.65693355648660.906925572
#Sta/Elev= 30
       0 2535.24    23.4 2534.43      37 2531.25    48.5  2530.6    54.7 2528.82
    62.5 2528.04    75.4 2523.35    84.1 2521.28   100.9 2513.41   127.4 2494.45
   133.32493.219     149 2491.45     162 2492.12   166.4 2492.91     175 2494.34
   196.7 2493.04   209.7  2495.6   220.2 2495.42   231.4 2494.11   250.8 2493.61
     260 2494.45   274.7 2496.97     292  2496.2     357 2500.69   400.3  2501.7
   404.6 2503.25   413.3 2507.78     422 2510.69   443.5 2513.95   463.6 2518.22
#Mann= 4 ,-1,0
       0      .1       0   133.3    .045       0   166.4      .1       0
  405.17     .06       0
Bank Sta=133.3,166.4
XS Rating Curve= 0 ,0
Exp/Cntr(USF)=0,0
Exp/Cntr=0.3,0.1