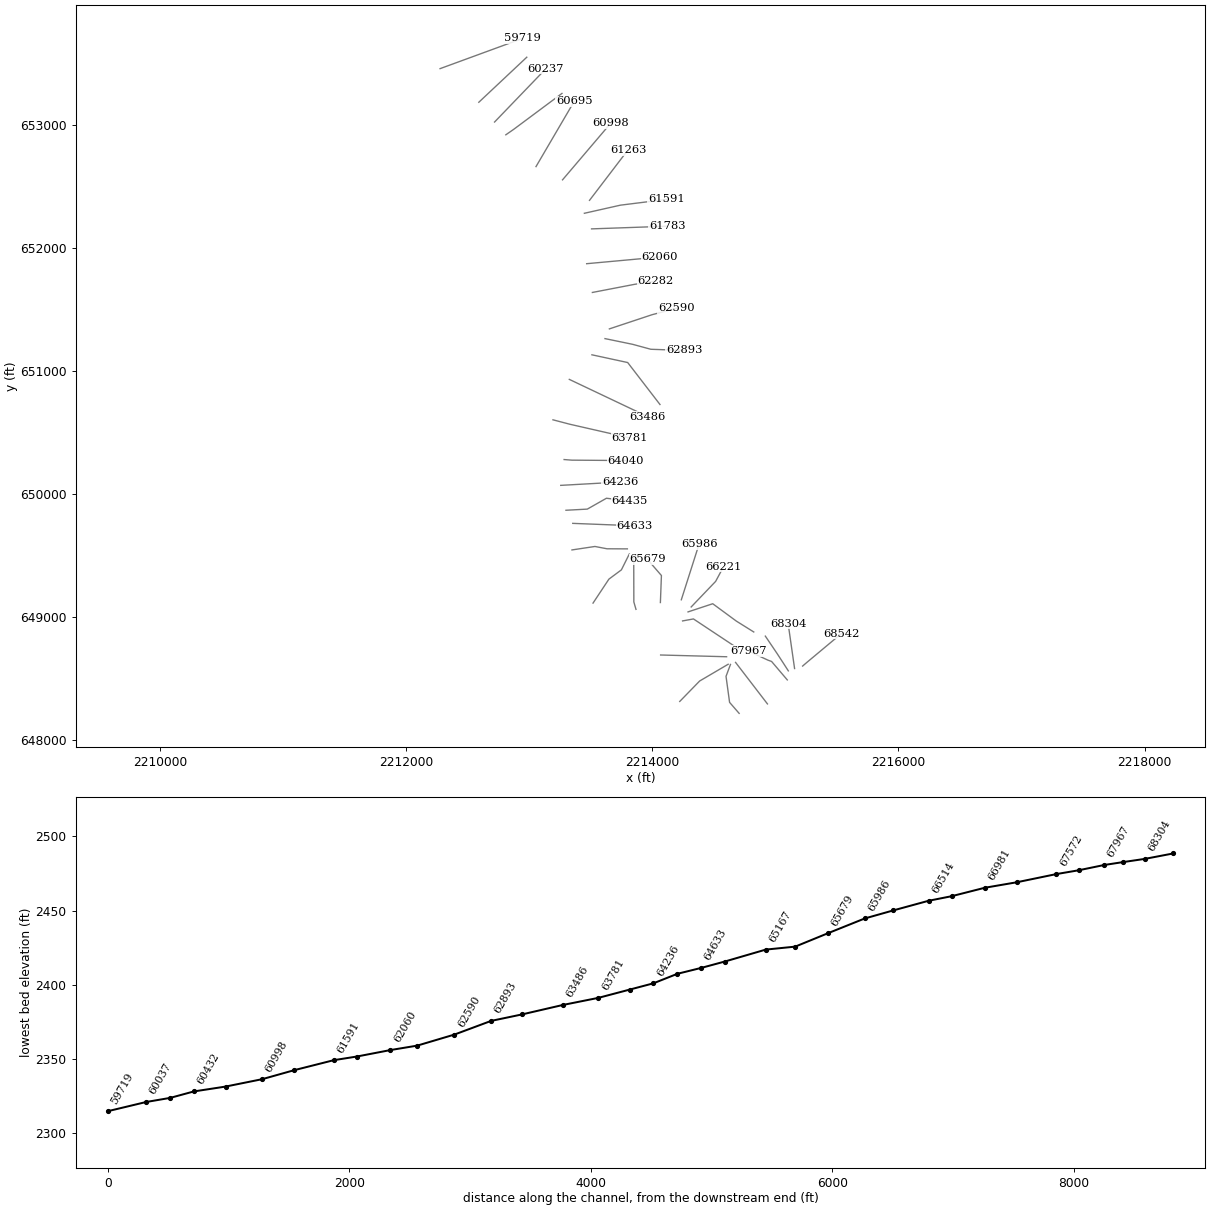
HEC-RAS study RFMIDDLERV.prj: RFMIDDLERV

--- RFMIDDLERV.g01 (geometry) --- (continued)

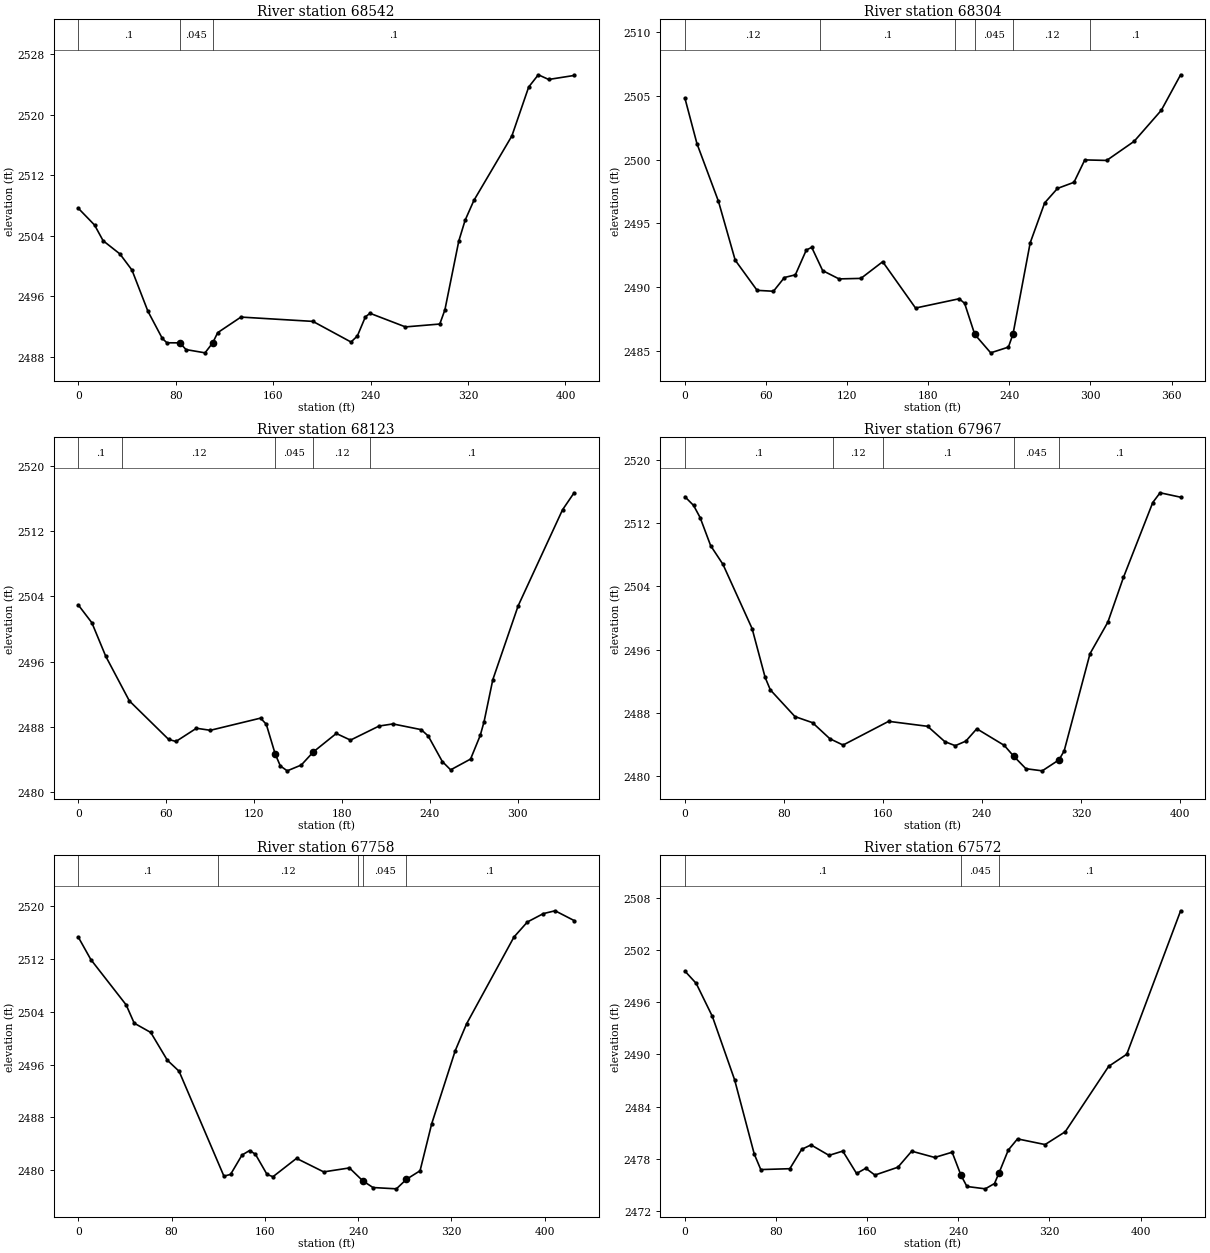
Type RM Length L Ch R = 1 ,68542   ,222.2,237.6,251.2
XS GIS Cut Line= 3
2215220.79608698648604.4689087412215253.00670319648632.287168193
2215532.81148674648865.890858862
#Sta/Elev= 30
       0 2507.63    13.3 2505.42    20.3 2503.35    34.1  2501.6      44 2499.47
    57.1 2494.02    68.9 2490.43    72.7 2489.85    83.3 2489.84    88.4 2488.95
     104 2488.52   110.32489.838   114.4 2491.19   133.5 2493.25   192.6 2492.68
   223.9 2489.95   229.1 2490.75   235.7 2493.28   239.5 2493.75   268.6 2491.95
   296.8 2492.33     301 2494.21   312.4 2503.31   317.6 2506.06   324.8 2508.68
     356 2517.21   369.8 2523.68   377.7  2525.3   386.2 2524.68   407.1 2525.21
#Mann= 3 ,-1,0
       0      .1       0    83.3    .045       0   110.3      .1       0
Bank Sta=83.3,110.3
XS Rating Curve= 0 ,0
Exp/Cntr(USF)=0,0
Exp/Cntr=0.3,0.1

Type RM Length L Ch R = 1 ,68304   ,171.9,181,184.4
XS GIS Cut Line= 2
2215155.36804686648584.3246207312215103.31861931648947.352906584
#Sta/Elev= 30
       0 2504.83     8.9 2501.26    24.8 2496.73    37.2  2492.1    53.4 2489.73
    65.5 2489.66    73.6 2490.74    81.7 2490.95    89.8  2492.9    93.8 2493.11
   101.9 2491.28     114 2490.63   130.2 2490.67   146.3 2491.98   170.6 2488.34
   202.9 2489.07   206.9 2488.71   214.4 2486.27   226.2 2484.82   239.3 2485.27
   242.72486.295   255.4 2493.46   266.1  2496.6   275.6 2497.74   287.8 2498.22
   295.8 2499.98     312 2499.94   332.3 2501.44   352.4 2503.88   366.7 2506.67
#Mann= 6 ,-1,0
       0     .12       0     100      .1       0     200     .12       0
   214.4    .045       0   242.7     .12       0     300      .1       0
Bank Sta=214.4,242.7
XS Rating Curve= 0 ,0
Exp/Cntr(USF)=0,0
Exp/Cntr=0.3,0.1

Type RM Length L Ch R = 1 ,68123   ,132.4,156.1,160.2
XS GIS Cut Line= 4
2215104.54187261648565.469252458  2215054.732547 648642.55511352
 2215012.6318075 648707.188643182214917.75690158648847.722097578
#Sta/Elev= 30
       0 2502.93     9.2 2500.77    18.7 2496.66    34.8 2491.21    61.6  2486.5
    66.6 2486.24    80.6 2487.86    90.1 2487.61   124.4  2489.1   128.3 2488.35
   134.42484.706   137.9 2483.25   142.6 2482.65   152.2 2483.36   160.42484.958
   176.1 2487.22   185.8 2486.41   205.3 2488.13   214.8 2488.39   234.1 2487.69
   238.9 2486.91   248.5 2483.79   254.2 2482.77   267.8 2484.09   274.4 2486.98
     277 2488.65     283 2493.81   300.3 2502.84   330.6 2514.59   338.5 2516.67
#Mann= 5 ,-1,0
       0      .1       0      30     .12       0   134.4    .045       0
   160.4     .12       0  198.91      .1       0
Bank Sta=134.4,160.4
XS Rating Curve= 0 ,0
Exp/Cntr(USF)=0,0
Exp/Cntr=0.3,0.1

Type RM Length L Ch R = 1 ,67967   ,217.6,209.1,199.7
XS GIS Cut Line= 5
2215096.10003032648491.8353437632214968.41252516648641.834858466
2214939.57412599648652.2100469282214827.05899579648704.514558032
2214783.96998973648727.391544478
#Sta/Elev= 30
       0 2515.35       7 2514.25    12.3 2512.71    20.8 2509.16    30.7 2506.81
    54.3 2498.67    64.8 2492.51      69 2490.93    88.9 2487.55   103.1 2486.78
   117.1 2484.75   127.8 2483.95   164.6 2486.95   196.1 2486.32     210 2484.38
   218.4 2483.87     227 2484.45   235.8 2486.01     258 2483.91   265.52482.563
   275.5 2480.96   288.7 2480.69   302.22482.075   306.4 2483.21   327.3 2495.51
   341.7 2499.49   354.3 2505.15     378 2514.62   383.9 2515.85   400.5 2515.29
#Mann= 5 ,-1,0
       0      .1       0     120     .12       0     160      .1       0
   265.5    .045       0   302.2      .1       0
Bank Sta=265.5,302.2
XS Rating Curve= 0 ,0
Exp/Cntr(USF)=0,0
Exp/Cntr=0.3,0.1

Type RM Length L Ch R = 1 ,67758   ,192.9,185.9,173.9
XS GIS Cut Line= 2
2214934.80627875648296.6900311322214675.72350715648634.100152278
#Sta/Elev= 30
       0 2515.31    10.7 2511.93      41 2505.06    47.9 2502.29    62.1 2500.88
    76.3 2496.68    86.4    2495   124.9 2479.09   130.6 2479.36   140.4 2482.29
   146.9 2482.98   151.9 2482.42   161.9 2479.35     167 2479.01   187.2 2481.79
   210.5 2479.74   232.6 2480.34     2442478.392   252.8 2477.37   272.9 2477.17
   281.52478.613   293.2 2479.91   303.2 2487.04   323.4 2498.12   333.1 2502.18
   373.8 2515.35   385.3 2517.63     399  2518.9   409.1 2519.33   425.4 2517.85
#Mann= 5 ,-1,0
       0      .1       0     120     .12       0     240      .1       0
     244    .045       0   281.5      .1       0
Bank Sta=244,281.5
XS Rating Curve= 0 ,0
Exp/Cntr(USF)=0,0
Exp/Cntr=0.3,0.1

Type RM Length L Ch R = 1 ,67572   ,342,328.1,306.8
XS GIS Cut Line= 4
2214704.78873658648219.833008734 2214627.0639051648309.306942645
2214598.14303757648520.7907864352214634.29412198648617.494937228
#Sta/Elev= 30
       0 2499.56     9.9 2498.15    24.1 2494.36    43.6  2487.1    60.9 2478.56
    66.6 2476.79    92.1 2476.89   102.5 2479.11   110.7 2479.62   126.5 2478.42
   138.6 2478.91   150.7 2476.34   158.8 2476.94   166.8 2476.16     187 2477.06
   199.1  2478.9   219.3 2478.18   234.6 2478.78   242.42476.123   247.6 2474.85
   263.7 2474.58   271.8 2475.19   275.72476.389   283.9 2479.03     292 2480.31
   316.2 2479.66   333.9 2481.13     372 2488.63   387.9 2490.02   435.2 2506.48
#Mann= 3 ,-1,0
       0      .1       0   242.4    .045       0   275.7      .1       0
Bank Sta=242.4,275.7
XS Rating Curve= 0 ,0
Exp/Cntr(USF)=0,0
Exp/Cntr=0.3,0.1

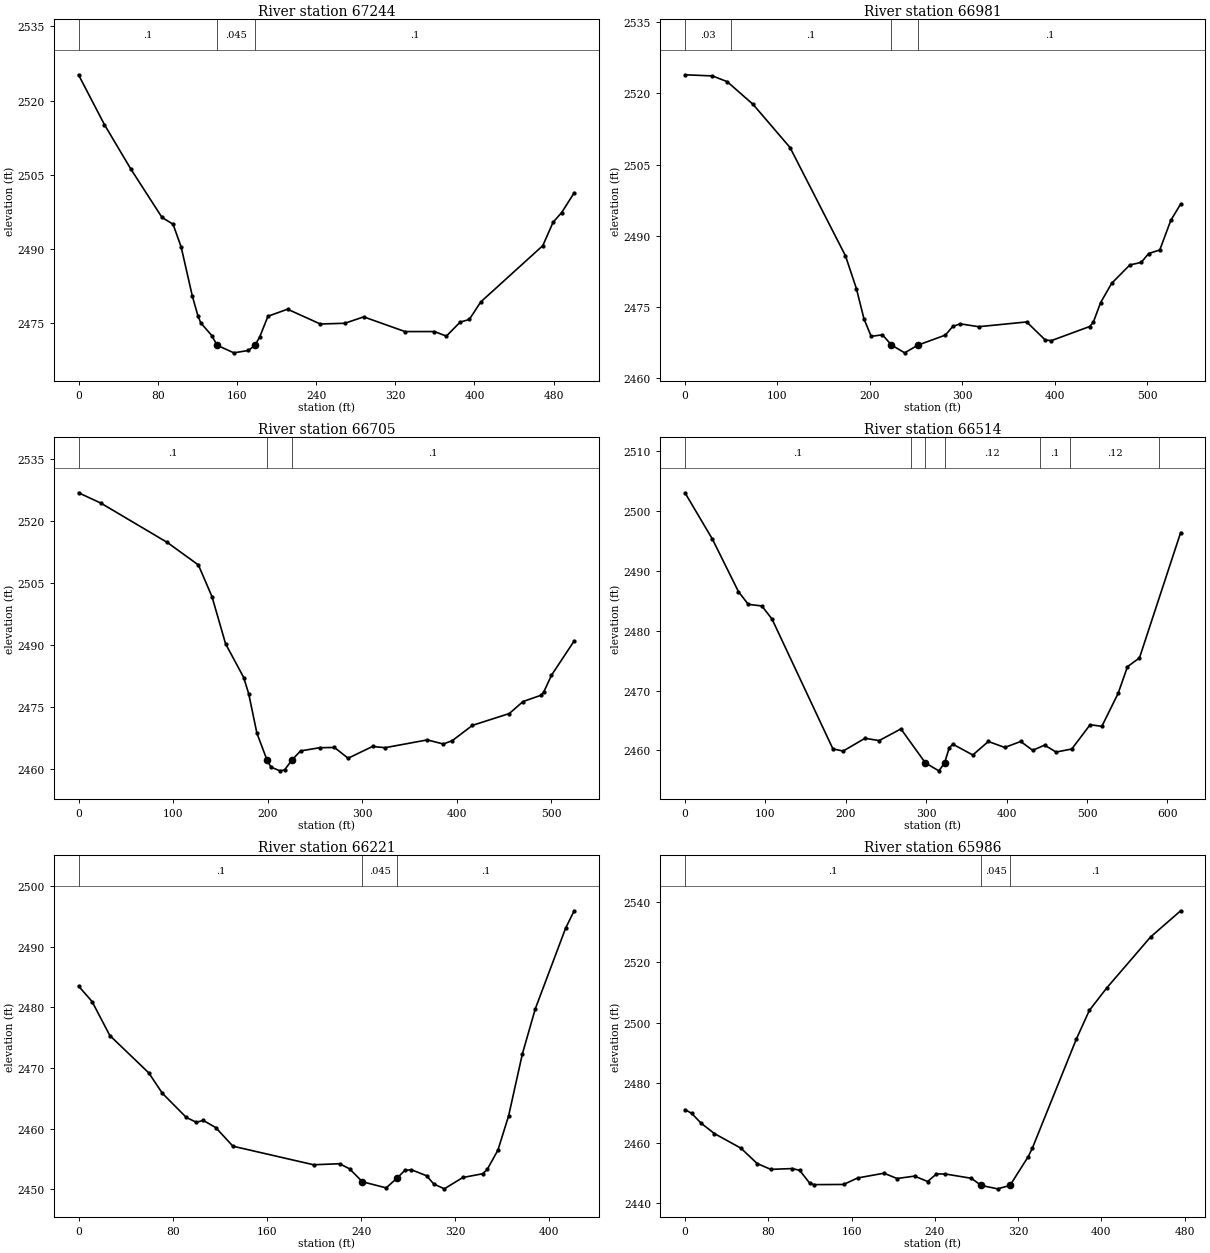
Type RM Length L Ch R = 1 ,67244   ,277.8,263.4,247.8
XS GIS Cut Line= 3
2214221.88379997648316.7946860412214383.82057419648482.969170706
2214615.43639195648619.041806295
#Sta/Elev= 30
       0  2525.2    26.2 2515.13    52.8 2506.18    84.3 2496.41    95.5 2495.03
   103.7 2490.42     115  2480.5   120.7 2476.48   123.6 2475.09   134.6 2472.55
     1402470.592   156.9 2469.06   171.6 2469.54   178.22470.583   182.9  2472.2
   191.4 2476.45   211.2 2477.87   244.3 2474.88     269 2475.03   288.1 2476.32
   329.9 2473.35   359.6 2473.36   371.6 2472.43   385.5 2475.26   394.8  2475.8
   406.3 2479.33     469  2490.7   479.4 2495.42   488.1 2497.39   500.7 2501.36
#Mann= 3 ,-1,0
       0      .1       0     140    .045       0   178.2      .1       0
Bank Sta=140,178.2
XS Rating Curve= 0 ,0
Exp/Cntr(USF)=0,0
Exp/Cntr=0.3,0.1

Type RM Length L Ch R = 1 ,66981   ,285.9,275.9,270
XS GIS Cut Line= 2
2214066.52394995648694.3520162672214602.77116363648680.124059362
#Sta/Elev= 30
       0 2523.89    29.7 2523.65    45.7 2522.44    73.7 2517.66   113.7 2508.58
   173.7 2485.79   185.5  2478.9   193.7 2472.53   201.5 2468.85   213.7 2469.17
   223.42467.039   237.7 2465.38   252.42467.032   281.8 2469.11   289.8 2470.93
   297.8 2471.48   317.8 2470.88   369.8 2471.88   389.8  2468.1   396.4 2467.94
   437.8 2470.91   441.8 2471.78   449.8 2475.95   461.8 2480.02   481.4 2483.87
   493.8 2484.42   501.8 2486.28   513.8 2487.02   525.8 2493.27   536.4 2496.69
#Mann= 4 ,-1,0
       0     .03       0      50      .1       0   223.4    .045       0
   252.4      .1       0
Bank Sta=223.4,252.4
XS Rating Curve= 0 ,0
Exp/Cntr(USF)=0,0
Exp/Cntr=0.3,0.1

Type RM Length L Ch R = 1 ,66705   ,190.5,190.6,188.6
XS GIS Cut Line= 3
2214245.02653356648971.3167761472214333.30658907648987.506659937
2214695.50676817 648747.31560684
#Sta/Elev= 30
       0 2526.91    23.5 2524.43      94 2514.89   126.8 2509.46   141.2 2501.81
   155.6 2490.39   174.8 2482.23   180.1 2478.27   188.7 2468.81   199.32462.354
   203.6 2460.57   213.2 2459.67     218 2459.89     226 2462.34   234.9 2464.48
   255.1 2465.26   270.8 2465.32   285.2 2462.72   311.1 2465.56   324.4 2465.27
     369 2467.15     386 2466.16   395.6 2466.99   416.7 2470.66   455.8 2473.53
   470.3 2476.43   488.9 2477.91     492 2478.62   500.4 2482.78   524.4 2491.08
#Mann= 3 ,-1,0
       0      .1       0   199.3    .045       0     226      .1       0
Bank Sta=199.3,226
XS Rating Curve= 0 ,0
Exp/Cntr(USF)=0,0
Exp/Cntr=0.3,0.1

Type RM Length L Ch R = 1 ,66514   ,269.6,292.9,307.6
XS GIS Cut Line= 4
2214289.43541705649044.7111520122214490.07480939649111.069500994
2214681.67555676648970.0802718012214823.56856306   648881.510115
#Sta/Elev= 30
       0 2503.09    34.2 2495.32    66.5 2486.56    78.7 2484.44    95.6 2484.16
   108.2 2481.99     184 2460.26   196.7  2459.9   223.9 2462.03   241.5 2461.65
   268.6  2463.6   299.12457.902   315.8 2456.59   322.9  2457.9   328.6 2460.41
   333.1 2461.05     358 2459.24   377.3  2461.5   397.7  2460.5   417.6  2461.5
   432.5 2460.02   447.3 2460.89   461.6 2459.73   481.1 2460.24   503.9  2464.3
   518.5 2464.03   538.8 2469.56   550.4 2474.01   565.3 2475.48   616.5 2496.43
#Mann= 7 ,-1,0
       0      .1       0  281.33     .12       0   299.1    .045       0
   322.9     .12       0  441.33      .1       0  479.21     .12       0
  589.21      .1       0
Bank Sta=299.1,322.9
XS Rating Curve= 0 ,0
Exp/Cntr(USF)=0,0
Exp/Cntr=0.3,0.1

Type RM Length L Ch R = 1 ,66221   ,228.2,235.7,240.8
XS GIS Cut Line= 3
2214314.91465064649084.8927492742214513.74561489649292.761484623
 2214577.0100126649410.252508951
#Sta/Elev= 30
       0 2483.52    11.5 2480.97    26.6 2475.36    59.7  2469.2    71.3 2465.82
    91.6 2461.85   100.1 2461.06     106 2461.36   116.6 2460.18   131.2 2457.11
   199.7 2454.05   221.8 2454.22   230.3 2453.38   241.22451.242   261.4 2450.24
     2712451.911   277.2 2453.13   282.7 2453.23   295.7 2452.24   301.8 2450.88
   310.8 2450.08   326.5 2451.95   343.4 2452.57   347.2 2453.27   356.3 2456.45
   365.4 2462.11   377.1 2472.33   388.1 2479.78   413.8 2493.04   421.1 2495.93
#Mann= 3 ,-1,0
       0      .1       0   241.2    .045       0     271      .1       0
Bank Sta=241.2,271
XS Rating Curve= 0 ,0
Exp/Cntr(USF)=0,0
Exp/Cntr=0.3,0.1

Type RM Length L Ch R = 1 ,65986   ,290.9,306.3,317
XS GIS Cut Line= 2
2214234.71050086649143.1244967132214379.39648199649596.657467745
#Sta/Elev= 30
       0 2471.02     6.4  2469.8    15.5  2466.5    28.3 2463.05    53.7  2458.2
    69.3 2453.09    82.4 2451.14   102.9 2451.41   110.1 2450.83   119.7 2446.59
   123.9 2446.06   152.4 2446.12   165.9 2448.28   191.1 2449.86   203.7  2448.1
   220.5 2448.89   233.1  2447.1   241.5  2449.6   249.9 2449.61   275.1 2448.17
   284.52445.788   300.3 2444.66   312.22445.805   329.6 2455.31   333.8 2458.31
   375.8  2494.4   388.4 2504.04   405.2 2511.55   447.2 2528.47   476.1  2537.2
#Mann= 3 ,-1,0
       0      .1       0   284.5    .045       0   312.2      .1       0
Bank Sta=284.5,312.2
XS Rating Curve= 0 ,0
Exp/Cntr(USF)=0,0
Exp/Cntr=0.3,0.1

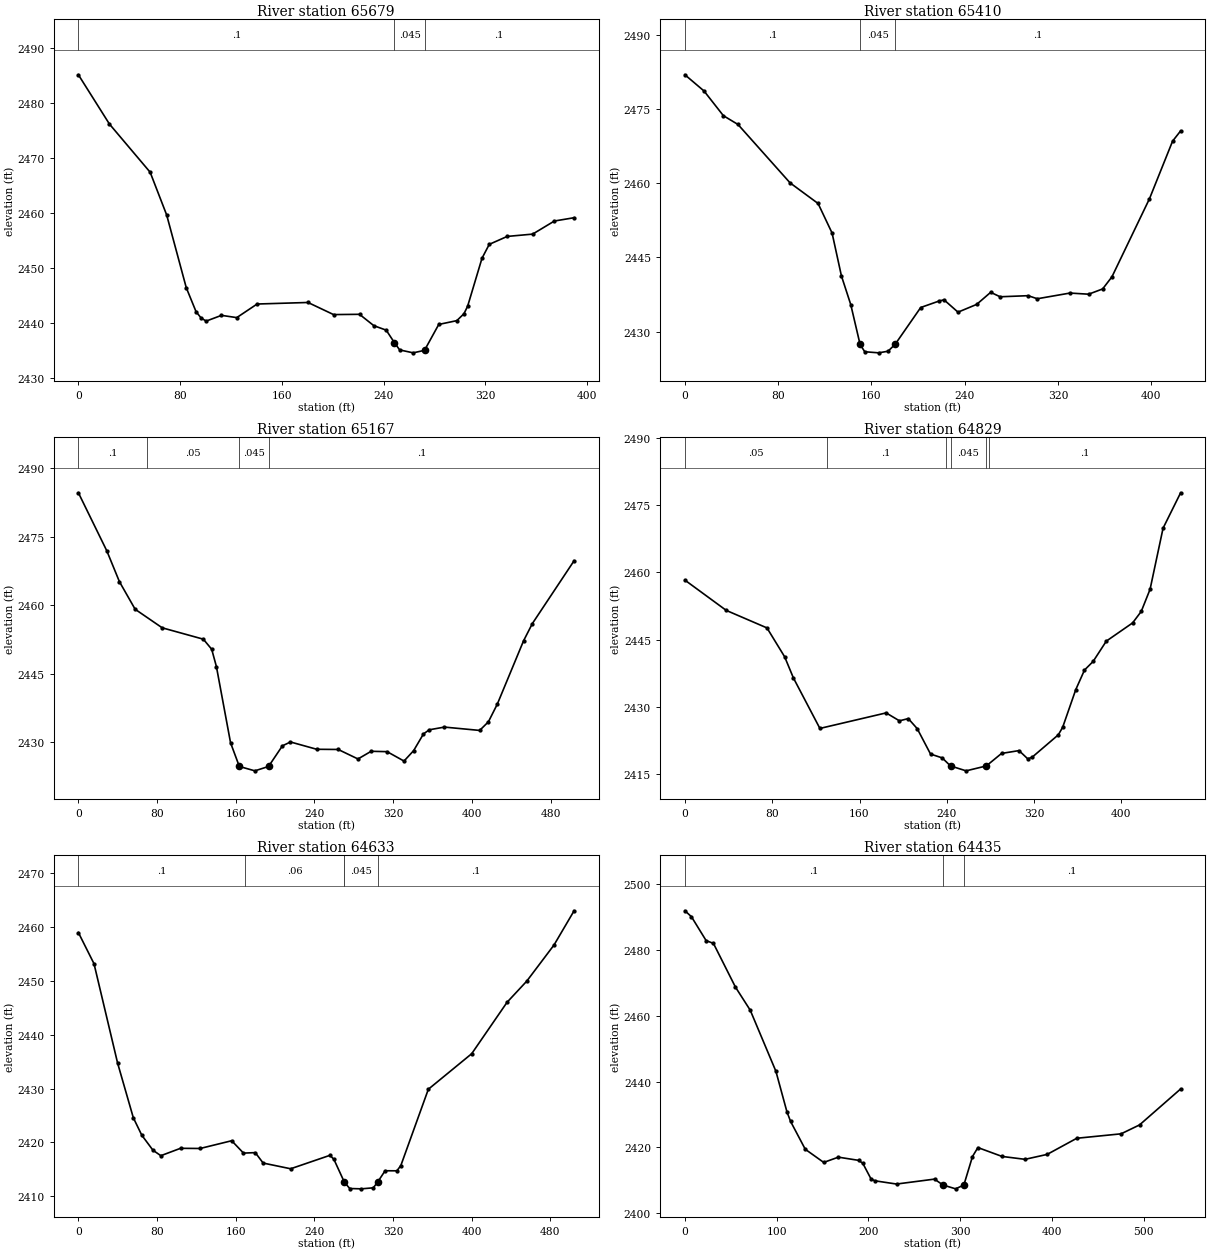
Type RM Length L Ch R = 1 ,65679   ,271.2,268.7,248.3
XS GIS Cut Line= 4
 2214064.5999451649120.7823088552214072.99723464649340.410870217
2213986.25111695649440.4907188952213964.12022664649470.743409484
#Sta/Elev= 30
       0 2485.17    24.4 2476.22    56.4 2467.47    69.4  2459.7    84.8 2446.49
    92.5 2442.13    96.5 2440.97   100.5 2440.42   112.5 2441.46   124.5 2441.05
   140.5 2443.52   180.5  2443.8   200.6  2441.6     221 2441.65   232.3 2439.58
     242 2438.77   248.52436.476   252.6 2435.18   263.2 2434.65   272.12435.103
   283.3 2439.81   297.5  2440.5   303.1 2441.75     306 2443.12   317.3 2451.84
     323 2454.36   337.1  2455.8   357.1 2456.22   374.2  2458.6   389.7  2459.2
#Mann= 3 ,-1,0
       0      .1       0   248.5    .045       0   272.1      .1       0
Bank Sta=248.5,272.1
XS Rating Curve= 0 ,0
Exp/Cntr(USF)=0,0
Exp/Cntr=0.3,0.1

Type RM Length L Ch R = 1 ,65410   ,251.2,243.4,233.5
XS GIS Cut Line= 3
2213866.19908464649065.4370191672213848.81532245649125.655353288
2213847.91154534649488.069974484
#Sta/Elev= 30
       0 2481.89    16.4 2478.61      33 2473.62    45.5 2471.85    90.2 2460.04
   114.2 2455.88   126.2 2449.91   134.2 2441.26   142.2 2435.46   150.2 2427.41
   154.2 2425.92   166.2  2425.7   174.2 2426.03   180.32427.427   202.2 2434.86
   218.2 2436.19   222.2 2436.41   234.2 2433.92   250.2 2435.49   262.2 2437.93
   270.3 2437.03   294.3 2437.25   302.2 2436.63   330.2 2437.78   346.2 2437.55
   358.2 2438.61   366.2 2441.06   398.4 2456.85   418.2 2468.48   425.1 2470.55
#Mann= 3 ,-1,0
       0      .1       0   150.2    .045       0   180.3      .1       0
Bank Sta=150.2,180.3
XS Rating Curve= 0 ,0
Exp/Cntr(USF)=0,0
Exp/Cntr=0.3,0.1

Type RM Length L Ch R = 1 ,65167   ,355.5,338.6,320.2
XS GIS Cut Line= 4
2213517.11920501649116.2406984532213646.05311373649310.881310666
2213747.71254177649386.5060071312213811.94924397649515.031892704
#Sta/Elev= 30
       0  2484.6    28.9 2471.88    41.7 2465.14    57.7 2459.09    85.2 2455.03
     127 2452.54   135.5 2450.34   140.3 2446.54   154.7 2429.84   163.6 2424.67
   179.4 2423.71   193.32424.669   207.4 2429.19   215.6 2430.03   242.3 2428.43
   264.1 2428.39   284.2 2426.31   297.6 2427.99   313.8 2427.91     331 2425.85
   340.8 2428.14   350.8  2431.8   356.7  2432.7   372.1 2433.29   407.9 2432.56
   416.8 2434.45   425.8  2438.3   452.6 2452.22   461.5 2455.97   503.9 2469.72
#Mann= 4 ,-1,0
       0      .1       0      70     .05       0   163.6    .045       0
   193.3      .1       0
Bank Sta=163.6,193.3
XS Rating Curve= 0 ,0
Exp/Cntr(USF)=0,0
Exp/Cntr=0.3,0.1

Type RM Length L Ch R = 1 ,64829   ,193.2,195.5,198.2
XS GIS Cut Line= 4
2213345.83669532649548.399482602 2213532.6172981649576.516992698
2213630.51118103649557.7184425812213796.26245189649557.010017377
#Sta/Elev= 30
       0 2458.27    37.9 2451.51    75.2  2447.6    91.4 2441.15    99.4 2436.44
   123.7 2425.15   184.4 2428.62   196.6 2426.85   204.7 2427.35   212.9  2425.1
   225.1 2419.43   235.8 2418.57   243.42416.772   257.7 2415.68   276.22416.771
   290.2 2419.57   306.2  2420.2   314.2 2418.36   318.2 2418.72   342.2 2423.72
   346.2 2425.41   358.2 2433.82   366.2 2438.19   374.1 2440.11   386.2 2444.65
   410.3 2448.72   418.2 2451.28   426.3 2456.23   438.2 2469.87   454.3 2477.78
#Mann= 6 ,-1,0
       0     .05       0     130      .1       0  238.89     .06       0
   243.4    .045       0   276.2     .06       0  278.89      .1       0
Bank Sta=243.4,276.2
XS Rating Curve= 0 ,0
Exp/Cntr(USF)=0,0
Exp/Cntr=0.3,0.1

Type RM Length L Ch R = 1 ,64633   ,190.5,198,207.5
XS GIS Cut Line= 2
 2213352.3285865649764.3218899762213856.29478709649744.647443328
#Sta/Elev= 30
       0    2459    15.9 2453.21    39.9 2434.75    55.9 2424.59    64.5 2421.35
    75.9 2418.55    83.9 2417.54   103.9 2418.91   123.9 2418.88     156 2420.32
     168 2418.02     180 2418.11     188 2416.17     216 2415.11     256 2417.61
     260 2416.86   270.62412.635   276.1 2411.44     288 2411.38   300.1 2411.57
   304.52412.644   312.1 2414.74   324.1 2414.73   328.1 2415.71   356.1 2429.89
   400.2 2436.49   436.2 2446.05   456.2 2449.97     484  2456.7   504.4 2463.05
#Mann= 5 ,-1,0
       0      .1       0     170     .06       0     270      .1       0
   270.6    .045       0   304.5      .1       0
Bank Sta=270.6,304.5
XS Rating Curve= 0 ,0
Exp/Cntr(USF)=0,0
Exp/Cntr=0.3,0.1

Type RM Length L Ch R = 1 ,64435   ,205.3,198.8,190.7
XS GIS Cut Line= 4
2213297.11623158649870.8961338252213470.65591583649880.198539031
2213626.14534498 649968.484909822213812.60088926649946.083890366
#Sta/Elev= 30
       0    2492     7.1  2490.2    23.1 2482.93    31.1 2482.07    55.1 2468.77
    71.2 2461.75    99.2 2443.15   111.2 2430.84   115.2  2427.9   131.2 2419.43
   151.3 2415.43   167.3 2417.03   189.3 2416.06   193.9 2415.17   203.1 2410.29
   207.7 2409.81   230.7 2408.85   272.1 2410.35   281.2 2408.57   295.1 2407.39
   304.12408.567   313.5 2417.23   319.4 2419.95   345.7 2417.25   370.8 2416.37
   394.9 2417.87   427.2 2422.78   475.5 2424.13   495.6 2426.84   540.4 2437.78
#Mann= 3 ,-1,0
       0      .1       0   281.2    .045       0   304.1      .1       0
Bank Sta=281.2,304.1
XS Rating Curve= 0 ,0
Exp/Cntr(USF)=0,0
Exp/Cntr=0.3,0.1

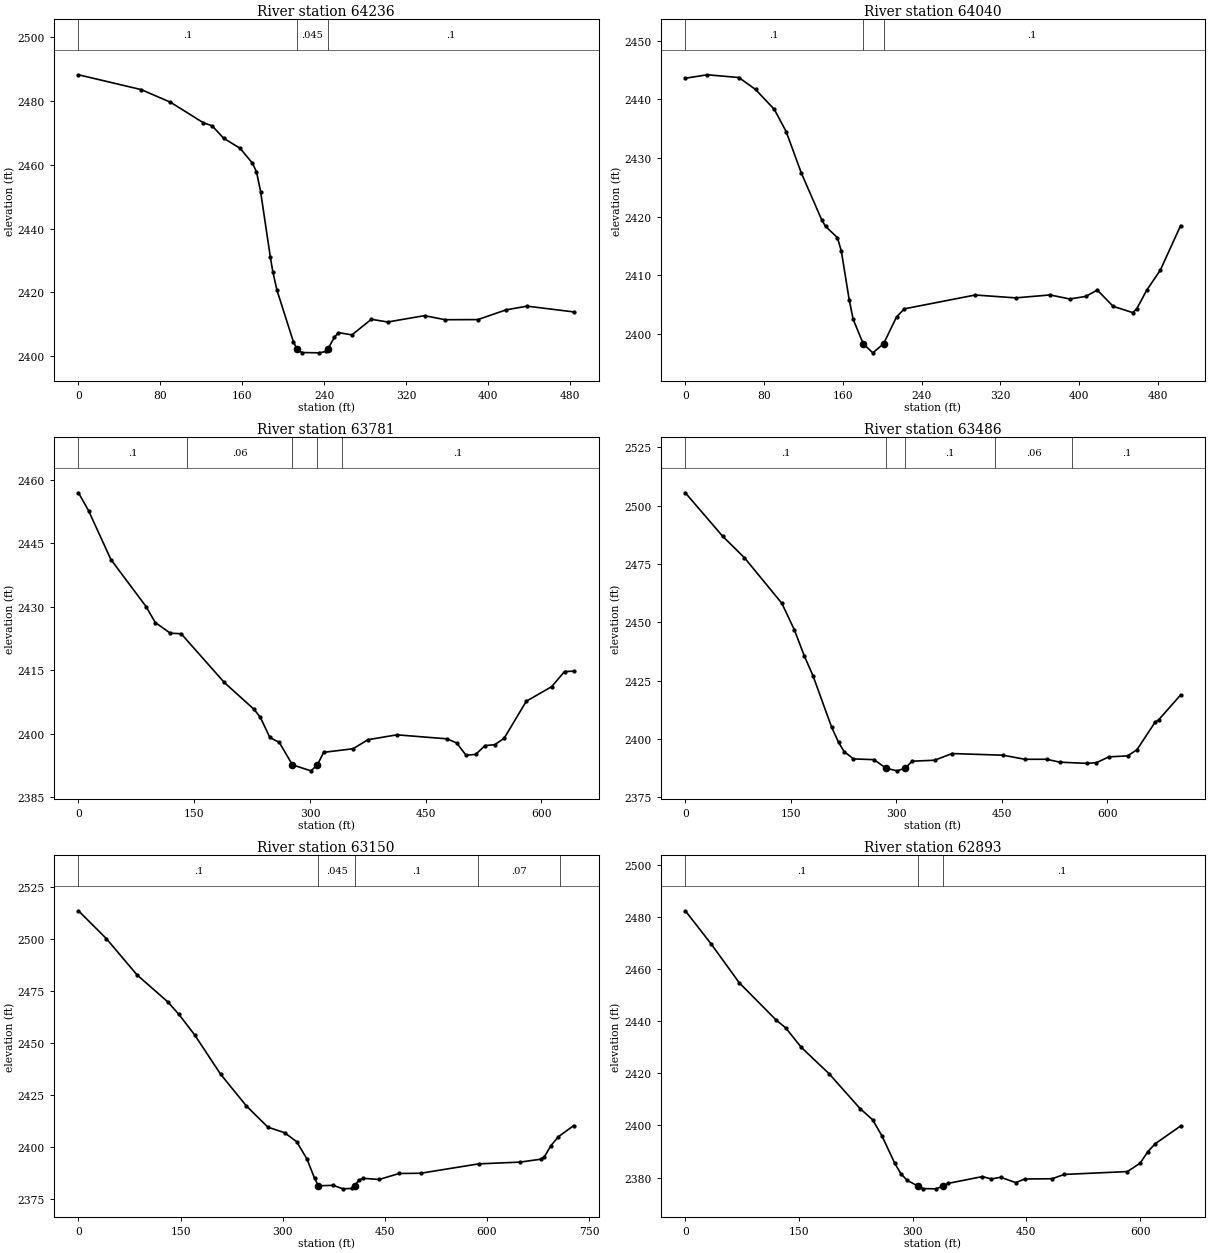
Type RM Length L Ch R = 1 ,64236   ,195.3,196.1,194.5
XS GIS Cut Line= 2
2213254.55526367650073.2154666962213737.71450679650100.301666689
#Sta/Elev= 30
       0 2488.29    61.2 2483.64    89.8 2479.68   121.8 2473.25   130.5 2472.26
   141.8 2468.38   157.9 2465.19   169.9 2460.55   173.9 2457.81   177.9 2451.62
   187.4 2431.07   189.9 2426.34   193.9 2420.63   209.9 2404.48   213.3 2402.27
     218 2401.07   235.2 2400.97     242 2401.43   243.82402.288     250 2405.86
     254 2407.33   267.1  2406.6   286.1  2411.5   302.1 2410.66   338.1 2412.65
   358.1 2411.37   390.2 2411.41   417.7 2414.47   438.3 2415.63   483.9 2413.82
#Mann= 3 ,-1,0
       0      .1       0   213.3    .045       0   243.8      .1       0
Bank Sta=213.3,243.8
XS Rating Curve= 0 ,0
Exp/Cntr(USF)=0,0
Exp/Cntr=0.3,0.1

Type RM Length L Ch R = 1 ,64040   ,263.1,259.2,256.1
XS GIS Cut Line= 3
2213281.98232028650283.0781649442213345.20952553650278.119168455
2213784.81246724650274.956147965
#Sta/Elev= 30
       0 2443.61    22.3  2444.2    54.4 2443.73    71.3 2441.69    90.4 2438.29
   102.4  2434.5   117.8 2427.43   138.4 2419.48   142.4 2418.32   154.4 2416.43
   158.4 2414.13   166.4 2405.82   170.4 2402.49   180.62398.312   190.4 2396.75
   201.3  2398.3   214.5 2402.88   222.4 2404.26   294.4 2406.62   335.4 2406.13
   370.4 2406.63   390.4 2405.94   406.4 2406.37   418.4 2407.46   434.4 2404.69
   454.4 2403.61   458.4 2404.26   468.4  2407.4   482.4 2410.88     503 2418.47
#Mann= 3 ,-1,0
       0      .1       0   180.6    .045       0   201.3      .1       0
Bank Sta=180.6,201.3
XS Rating Curve= 0 ,0
Exp/Cntr(USF)=0,0
Exp/Cntr=0.3,0.1

Type RM Length L Ch R = 1 ,63781   ,298.7,295.1,291.7
XS GIS Cut Line= 3
2213191.51261013650606.0176632442213327.88501359650570.202688597
2213816.25236397650458.834490367
#Sta/Elev= 30
       0 2456.88    13.1 2452.63      42 2441.11    87.5 2430.01    99.5 2426.22
   119.1 2423.69     133 2423.58   188.9 2412.07   227.5 2405.71   235.7 2403.81
     248 2399.06   260.3 2397.89   277.22392.596   301.3 2391.18   309.7 2392.62
   317.7 2395.55   355.9  2396.4   375.1 2398.54   412.7 2399.69   477.7 2398.74
     490 2397.77   502.3 2394.86   514.6 2395.06   526.9 2397.15   539.3 2397.35
   551.6 2398.87   580.3 2407.62   613.2 2411.07   629.9 2414.65   641.9 2414.72
#Mann= 5 ,-1,0
       0      .1       0     140     .06       0   277.2    .045       0
   309.7     .06       0     341      .1       0
Bank Sta=277.2,309.7
XS Rating Curve= 0 ,0
Exp/Cntr(USF)=0,0
Exp/Cntr=0.3,0.1

Type RM Length L Ch R = 1 ,63486   ,340.1,335.5,329
XS GIS Cut Line= 2
2213324.26903688650934.6306811482213960.28614919650632.572174424
#Sta/Elev= 30
       0 2505.53      53 2486.92      84  2477.7   137.2 2458.16   154.9 2446.85
   169.1 2435.65   181.5 2427.09     208 2405.05   217.8 2398.59   225.7 2394.64
     239 2391.48   268.2 2391.17   285.42387.491     301 2386.37   312.62387.513
   322.3  2390.5   354.2 2390.91   379.3 2393.78   451.6 2393.07   482.6 2391.32
   513.6 2391.33   532.4 2390.08   571.1 2389.57   584.4 2389.87   602.1 2392.36
   628.7 2392.78     642 2395.42   667.5  2407.1     673  2408.3   704.1 2418.91
#Mann= 5 ,-1,0
       0      .1       0   285.4    .045       0   312.6      .1       0
     440     .06       0     550      .1       0
Bank Sta=285.4,312.6
XS Rating Curve= 0 ,0
Exp/Cntr(USF)=0,0
Exp/Cntr=0.3,0.1

Type RM Length L Ch R = 1 ,63150   ,215,257.4,262.3
XS GIS Cut Line= 3
2213508.15894531651134.4304008492213798.79443584651071.613031158
 2214061.2145127650730.470223365
#Sta/Elev= 30
       0 2513.69    40.9 2500.33      86 2482.87     131 2469.97   147.3 2463.98
   170.7 2454.02   208.7 2435.18   246.7 2419.87   278.3 2409.69   302.9 2407.01
   320.6 2402.69   335.7 2394.35   346.8 2385.14   352.52381.529   374.2 2381.74
   388.5 2380.05   401.3 2380.25   406.12381.553   411.4 2384.11   417.7 2385.11
   441.7 2384.56   471.2 2387.43   502.6 2387.54   588.1 2392.06   648.6 2392.89
   678.9 2394.28     684  2395.2     694 2400.79   705.1 2405.11   727.7 2410.48
#Mann= 5 ,-1,0
       0      .1       0   352.5    .045       0   406.1      .1       0
  587.35     .07       0  707.35      .1       0
Bank Sta=352.5,406.1
XS Rating Curve= 0 ,0
Exp/Cntr(USF)=0,0
Exp/Cntr=0.3,0.1

Type RM Length L Ch R = 1 ,62893   ,281.1,303.3,301.9
XS GIS Cut Line= 4
2213614.42246734651266.0570722192213839.29486708651219.603844224
2213986.91179508651179.4359726592214257.64653293651170.013211097
#Sta/Elev= 30
       0 2482.38    34.5 2469.48    71.2 2454.72   120.2 2440.33   132.5 2437.42
   152.9 2429.98   189.7 2419.82   230.5 2406.48   247.1 2402.16   259.6 2395.89
   276.1 2385.56   284.4 2381.47   292.7 2378.88   307.3 2376.68   313.4 2375.74
   330.3 2375.65   340.42376.674     347 2377.76   391.9 2380.35   403.9 2379.44
   415.9  2380.1   435.9 2378.04   447.9 2379.44   483.9 2379.52   499.9 2381.18
   583.3 2382.28     600 2385.49   610.3 2389.95     620 2392.98   653.5 2399.78
#Mann= 3 ,-1,0
       0      .1       0   307.3    .045       0   340.4      .1       0
Bank Sta=307.3,340.4
XS Rating Curve= 0 ,0
Exp/Cntr(USF)=0,0
Exp/Cntr=0.3,0.1

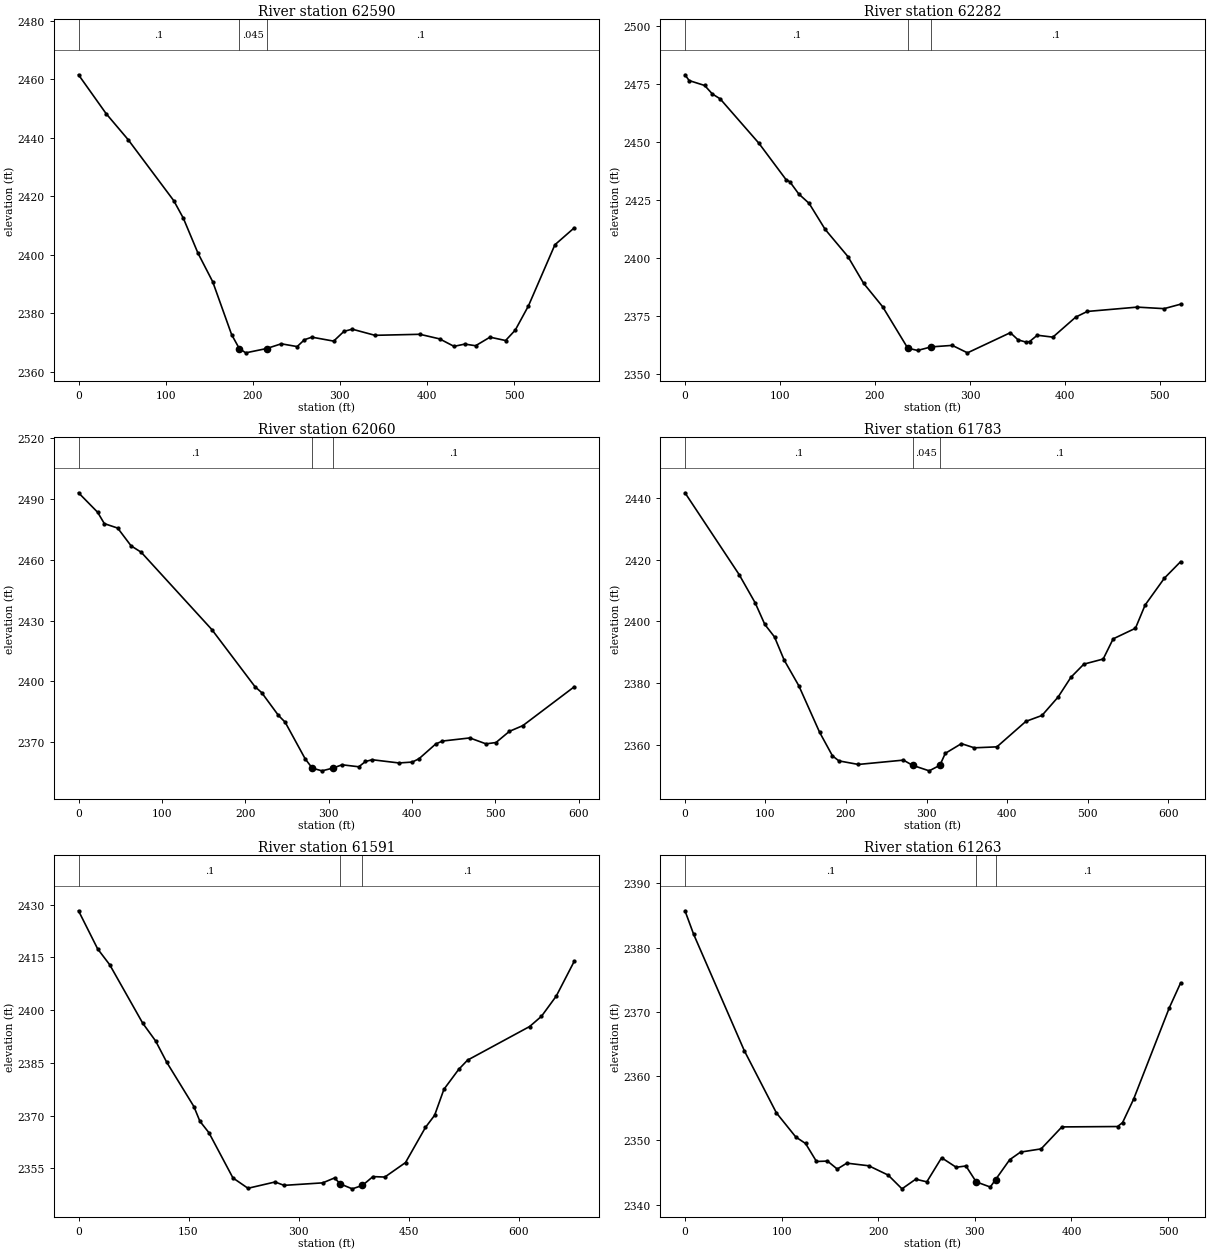
Type RM Length L Ch R = 1 ,62590   ,307.8,308.1,302.6
XS GIS Cut Line= 3
2213650.04724597  651345.17055612213997.29945665651460.501979094
 2214193.5390737651511.900513001
#Sta/Elev= 30
       0 2461.52    31.7 2448.23      57 2439.32   109.3 2418.48   120.3 2412.48
   137.1 2400.53     154 2390.76   175.7 2372.68   184.52367.924   191.9 2366.45
   215.92367.923   232.7 2369.54   250.9 2368.59   259.3 2370.94   267.8 2371.81
   292.8 2370.46   304.6 2373.79   314.1 2374.54   340.2 2372.44   391.8 2372.79
   414.4 2371.22   430.9 2368.67   443.3 2369.44   455.7 2368.88   472.2 2371.81
   490.1 2370.66   501.2 2374.22   516.3 2382.49   546.7  2403.4   568.8 2409.16
#Mann= 3 ,-1,0
       0      .1       0   184.5    .045       0   215.9      .1       0
Bank Sta=184.5,215.9
XS Rating Curve= 0 ,0
Exp/Cntr(USF)=0,0
Exp/Cntr=0.3,0.1

Type RM Length L Ch R = 1 ,62282   ,219.6,221.7,216.4
XS GIS Cut Line= 3
2213511.81122389651641.2540109582213854.34274866651707.229740004
2214025.30032863651733.327489737
#Sta/Elev= 30
       0 2479.12     4.4 2476.62    20.7  2474.5    28.9  2470.8      37 2468.74
    77.8 2449.56   106.3 2433.88   110.4 2432.89   119.8 2427.62   130.7 2423.56
   147.6 2412.31   171.5 2400.61   188.1 2389.02   208.1 2378.91   234.52361.044
   244.8 2360.03   259.22361.572   281.4 2362.22   297.4    2359   342.5  2367.7
   350.7  2364.6   358.8 2363.66   362.8 2363.88   370.9 2366.61   387.3 2365.78
   411.4 2374.45   423.5 2376.88   476.1 2378.75   504.4 2378.09   521.8 2380.02
#Mann= 3 ,-1,0
       0      .1       0   234.5    .045       0   259.2      .1       0
Bank Sta=234.5,259.2
XS Rating Curve= 0 ,0
Exp/Cntr(USF)=0,0
Exp/Cntr=0.3,0.1

Type RM Length L Ch R = 1 ,62060   ,275.6,276.7,277
XS GIS Cut Line= 2
2213465.32259067 651875.023890142214057.54410903651929.338951255
#Sta/Elev= 30
       0 2492.92    22.9 2483.35      31 2477.73      47 2475.54    63.1 2466.78
    75.2 2463.65     160 2425.56   211.7 2397.47   219.8 2394.51   239.9 2383.29
   247.9 2379.98     272 2361.89   280.52357.333   292.1 2356.01   305.12357.343
   316.2 2358.99   336.3 2358.01   344.3 2360.61   352.3 2361.48   384.5 2359.89
   400.5 2360.33   408.6 2361.99   428.6 2369.24   436.7 2370.68   469.5 2372.21
   488.9  2369.3   500.9 2369.95     517 2375.46   533.1 2378.27   594.7 2397.36
#Mann= 3 ,-1,0
       0      .1       0   280.5    .045       0   305.1      .1       0
Bank Sta=280.5,305.1
XS Rating Curve= 0 ,0
Exp/Cntr(USF)=0,0
Exp/Cntr=0.3,0.1

Type RM Length L Ch R = 1 ,61783   ,190.5,192.4,192.8
XS GIS Cut Line= 2
2213505.05148532 652158.05674412  2214120.268686 652179.73496388
#Sta/Elev= 30
       0 2441.63    67.2 2415.19    87.2 2406.01    99.2 2399.02   111.2 2394.99
   123.2  2387.5   141.4 2379.19   167.2 2364.15   183.2 2356.51   191.2 2354.89
   215.3 2353.74   271.3 2355.14   282.62353.463   303.3 2351.67   316.62353.468
   323.3 2357.33   343.3 2360.47   359.3 2359.12   387.4 2359.43   423.4 2367.67
   443.4 2369.59   463.4 2375.54   479.4 2381.96   495.4 2386.19   519.4 2387.84
   531.8 2394.37   559.5  2397.8   571.5 2405.32   595.5 2414.03   615.6 2419.35
#Mann= 3 ,-1,0
       0      .1       0   282.6    .045       0   316.6      .1       0
Bank Sta=282.6,316.6
XS Rating Curve= 0 ,0
Exp/Cntr(USF)=0,0
Exp/Cntr=0.3,0.1

Type RM Length L Ch R = 1 ,61591   ,317,327.7,335.8
XS GIS Cut Line= 3
2213446.75823958652284.8531916472213739.58847446652350.774541017
2214112.40547916652397.403882866
#Sta/Elev= 30
       0 2428.29    26.1 2417.45    42.5 2412.95    87.6  2396.3   105.2 2391.24
   120.4 2385.16   157.3 2372.61   165.5 2368.43   177.8 2365.17   210.6 2352.29
   231.1 2349.35     268 2351.14   280.3 2350.18     333 2350.89   349.1 2352.29
   357.12350.577   373.3 2349.19   387.12350.158   401.5 2352.67   417.7 2352.54
   445.9 2356.66   473.1 2366.66   485.6 2370.11   498.3 2377.51   518.4 2383.16
   530.5  2385.8   615.2 2395.37   631.3 2398.27   651.5 2404.03   675.9 2413.88
#Mann= 3 ,-1,0
       0      .1       0   357.1    .045       0   387.1      .1       0
Bank Sta=357.1,387.1
XS Rating Curve= 0 ,0
Exp/Cntr(USF)=0,0
Exp/Cntr=0.3,0.1

Type RM Length L Ch R = 1 ,61263   ,264.6,265,263.1
XS GIS Cut Line= 3
2213488.56903116652390.0076417442213762.41349555652748.807154501
2213801.27591129652796.707341342
#Sta/Elev= 30
       0 2385.74       9 2382.07    61.4 2363.96    94.6 2354.28   114.7 2350.52
   124.8 2349.51   136.1 2346.71   147.5 2346.77   157.6 2345.53   167.5 2346.45
   190.2 2346.04   210.3 2344.59   224.6 2342.45   238.8 2343.95   250.3 2343.54
   265.6 2347.29   280.7 2345.81   290.8 2346.01   301.42343.536     316 2342.73
   321.52343.898   336.1 2346.99   347.3 2348.17   368.6 2348.67   390.1 2352.09
   447.7 2352.15   452.9 2352.76   464.3  2356.4   501.2 2370.61     513 2374.51
#Mann= 3 ,-1,0
       0      .1       0   301.4    .045       0   321.5      .1       0
Bank Sta=301.4,321.5
XS Rating Curve= 0 ,0
Exp/Cntr(USF)=0,0
Exp/Cntr=0.3,0.1

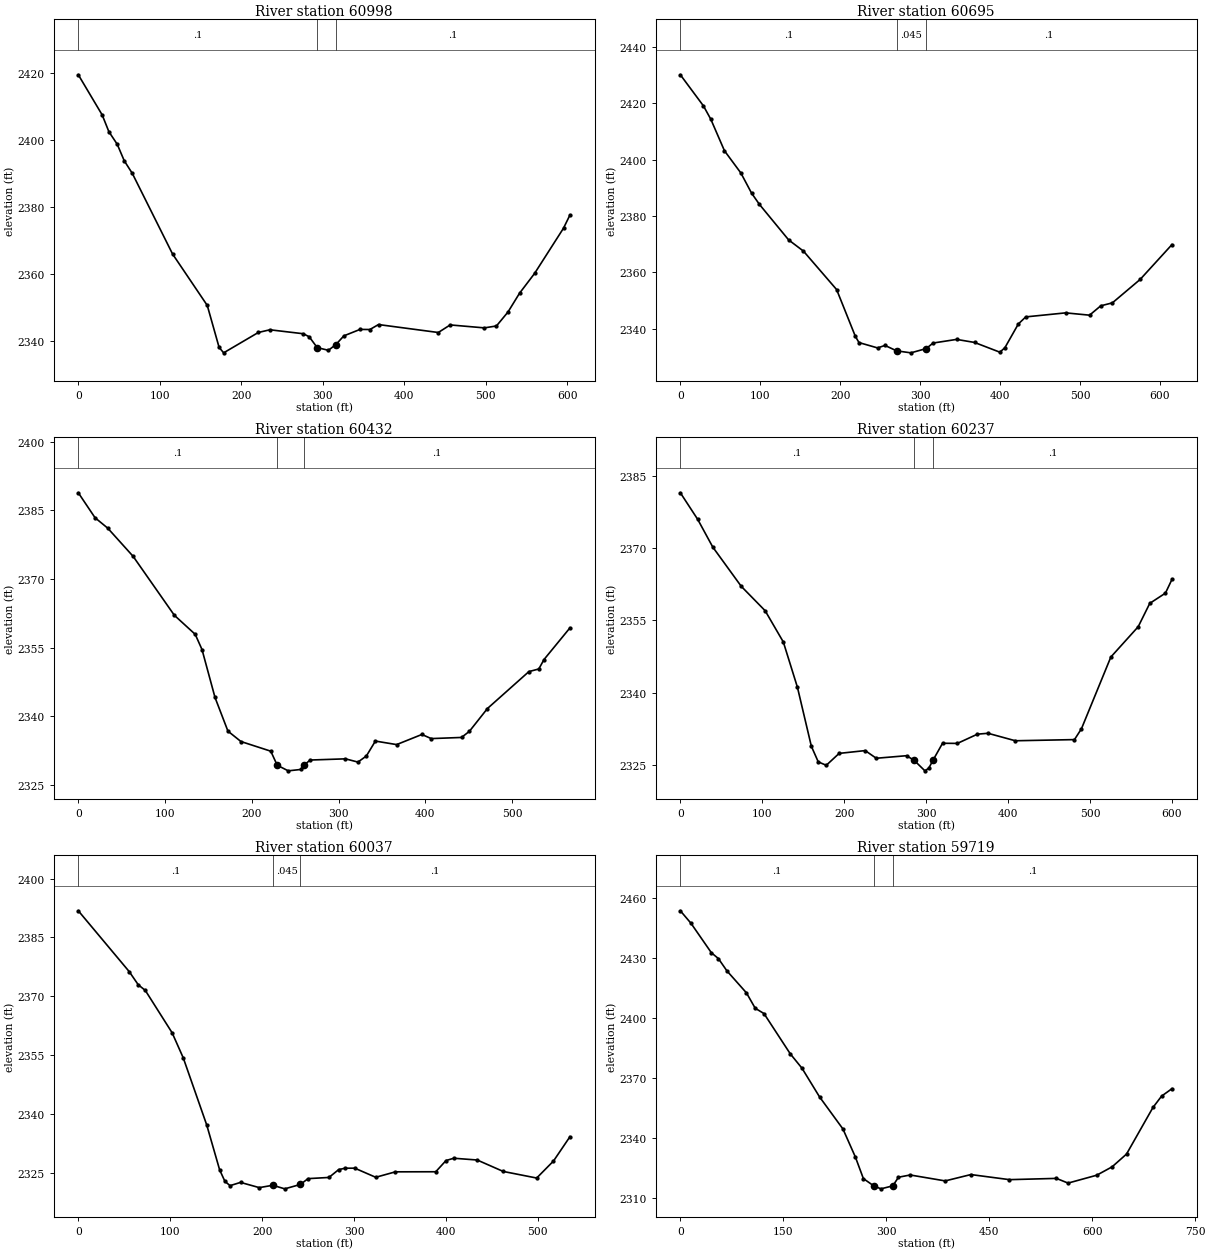
Type RM Length L Ch R = 1 ,60998   ,302.8,303.3,304.3
XS GIS Cut Line= 2
2213269.20265337652556.626409932 2213660.3064899653016.239588832
#Sta/Elev= 30
       0 2419.38    29.3  2407.4    37.5 2402.41    47.8 2398.63    56.4 2393.71
    66.3 2389.94   115.7 2365.89   158.3 2350.54   172.8 2338.04   178.4 2336.39
     221 2342.47   235.2 2343.27   276.2 2342.09   283.4 2341.19   293.32337.945
     307 2337.15   316.22338.863     326 2341.46   345.8 2343.38   357.9 2343.35
   368.5 2344.83   441.9 2342.46   456.5 2344.72   498.4 2343.84   513.3 2344.41
   527.5 2348.59   541.6 2354.17   560.1 2360.09   595.6 2373.59   603.5 2377.52
#Mann= 3 ,-1,0
       0      .1       0   293.3    .045       0   316.2      .1       0
Bank Sta=293.3,316.2
XS Rating Curve= 0 ,0
Exp/Cntr(USF)=0,0
Exp/Cntr=0.3,0.1

Type RM Length L Ch R = 1 ,60695   ,270.4,262.9,258.3
XS GIS Cut Line= 2
2213053.56210194652664.2727485392213364.26037688 653194.97905372
#Sta/Elev= 30
       0 2430.11    28.9 2419.06    38.1 2414.33    55.2 2403.13    75.7 2395.25
    89.1 2388.09      99 2384.07   135.5 2371.48     154 2367.51   195.5 2353.86
   218.9 2337.27   223.5 2335.04   246.7 2333.15     256 2334.03   270.6  2332.1
   288.4  2331.4   307.52332.908   316.2 2334.88   345.6 2336.17     368 2335.09
   399.7 2331.63     406 2333.22   422.8 2341.64   432.1 2344.16     482 2345.59
   511.9 2344.77   525.9 2348.09   540.5 2349.15   575.2 2357.46     615 2369.83
#Mann= 3 ,-1,0
       0      .1       0   270.6    .045       0   307.5      .1       0
Bank Sta=270.6,307.5
XS Rating Curve= 0 ,0
Exp/Cntr(USF)=0,0
Exp/Cntr=0.3,0.1

Type RM Length L Ch R = 1 ,60432   ,193.8,195,196.3
XS GIS Cut Line= 3
2212808.27932355 652922.748260632212870.53952447652965.928722563
2213264.49202312653259.060737354
#Sta/Elev= 30
       0 2388.83    19.3 2383.38    33.9 2381.11    63.2 2374.95   110.7 2362.09
   134.8 2357.92   142.6 2354.61   157.6 2344.14   172.5 2336.79   187.5 2334.52
   221.9 2332.41   229.32329.349     242 2328.12   256.5 2328.42   260.2 2329.35
   267.3 2330.48     308 2330.74   322.4 2330.03   332.1 2331.36   342.5 2334.62
     367 2333.85   396.1 2336.06   406.9 2335.16   441.8 2335.41   450.9 2336.75
   471.7 2341.73   519.5 2349.79   530.9 2350.36   536.9 2352.42   566.8 2359.33
#Mann= 3 ,-1,0
       0      .1       0   229.3    .045       0   260.2      .1       0
Bank Sta=229.3,260.2
XS Rating Curve= 0 ,0
Exp/Cntr(USF)=0,0
Exp/Cntr=0.3,0.1

Type RM Length L Ch R = 1 ,60237   ,200.8,199.8,197.7
XS GIS Cut Line= 2
2212716.68115677653026.640193858 2213132.7799935653458.915289218
#Sta/Elev= 30
       0 2381.47    21.2 2375.95    39.6  2370.2    74.3 2362.07   103.5    2357
   125.7 2350.51   142.9 2341.12   159.9 2328.88   168.3 2325.65   178.1 2324.94
   193.8 2327.41   225.6 2327.99   239.1  2326.4   276.1 2326.93   285.32325.975
   298.5 2323.79   303.3 2324.37   308.52326.036     320 2329.51   338.1 2329.48
   362.6  2331.4   375.5 2331.58   408.8 2330.03     481 2330.27   489.5 2332.51
   525.4  2347.4   558.8 2353.69   572.9 2358.53     592 2360.65     600  2363.5
#Mann= 3 ,-1,0
       0      .1       0   285.3    .045       0   308.5      .1       0
Bank Sta=285.3,308.5
XS Rating Curve= 0 ,0
Exp/Cntr(USF)=0,0
Exp/Cntr=0.3,0.1

Type RM Length L Ch R = 1 ,60037   ,321.2,318.2,310.5
XS GIS Cut Line= 2
2212588.64238444653187.2894639452212978.59242337 653553.44196067
#Sta/Elev= 30
       0 2391.79    55.4  2376.3    65.2 2372.96    72.9 2371.51   102.1 2360.72
   114.2 2354.33   139.7 2337.27   153.8 2325.81   159.5 2322.91   165.1 2321.81
   176.5 2322.64   196.9 2321.31   211.62321.908   224.6    2321   241.5 2322.11
     250  2323.6   272.7  2323.9   283.3  2325.9   290.2 2326.25   300.8 2326.26
   323.6 2323.94     345 2325.33   388.9 2325.35   400.1 2328.21   408.5 2328.79
     434 2328.34   462.3 2325.43   498.7 2323.75     517 2328.08   534.9 2334.27
#Mann= 3 ,-1,0
       0      .1       0   211.6    .045       0   241.5      .1       0
Bank Sta=211.6,241.5
XS Rating Curve= 0 ,0
Exp/Cntr(USF)=0,0
Exp/Cntr=0.3,0.1

Type RM Length L Ch R = 1 ,59719   ,265.1,263.8,261.5
XS GIS Cut Line= 2
 2212273.7327045653460.516574398 2212946.3133926 653706.87529368
#Sta/Elev= 30
       0  2453.7    15.4  2447.5    45.2 2432.74    55.4 2429.84    67.9 2423.66
    96.3  2412.7   109.1    2405   121.9 2402.34   160.2 2382.22   177.3 2375.02
   202.8 2360.73   236.9 2344.69     255 2330.71   266.7  2319.9   281.82316.276
   292.3 2314.79   309.6 2316.29   317.8 2320.59   334.9 2321.71   385.9 2318.75
   423.3 2321.92   479.5 2319.38   547.9 2320.01   564.9 2317.66   606.7  2321.6
   629.1 2325.79   650.1 2332.17   688.6 2355.44   701.2 2361.12   716.3 2364.83
#Mann= 3 ,-1,0
       0      .1       0   281.8    .045       0   309.6      .1       0
Bank Sta=281.8,309.6
XS Rating Curve= 0 ,0
Exp/Cntr(USF)=0,0
Exp/Cntr=0.3,0.1