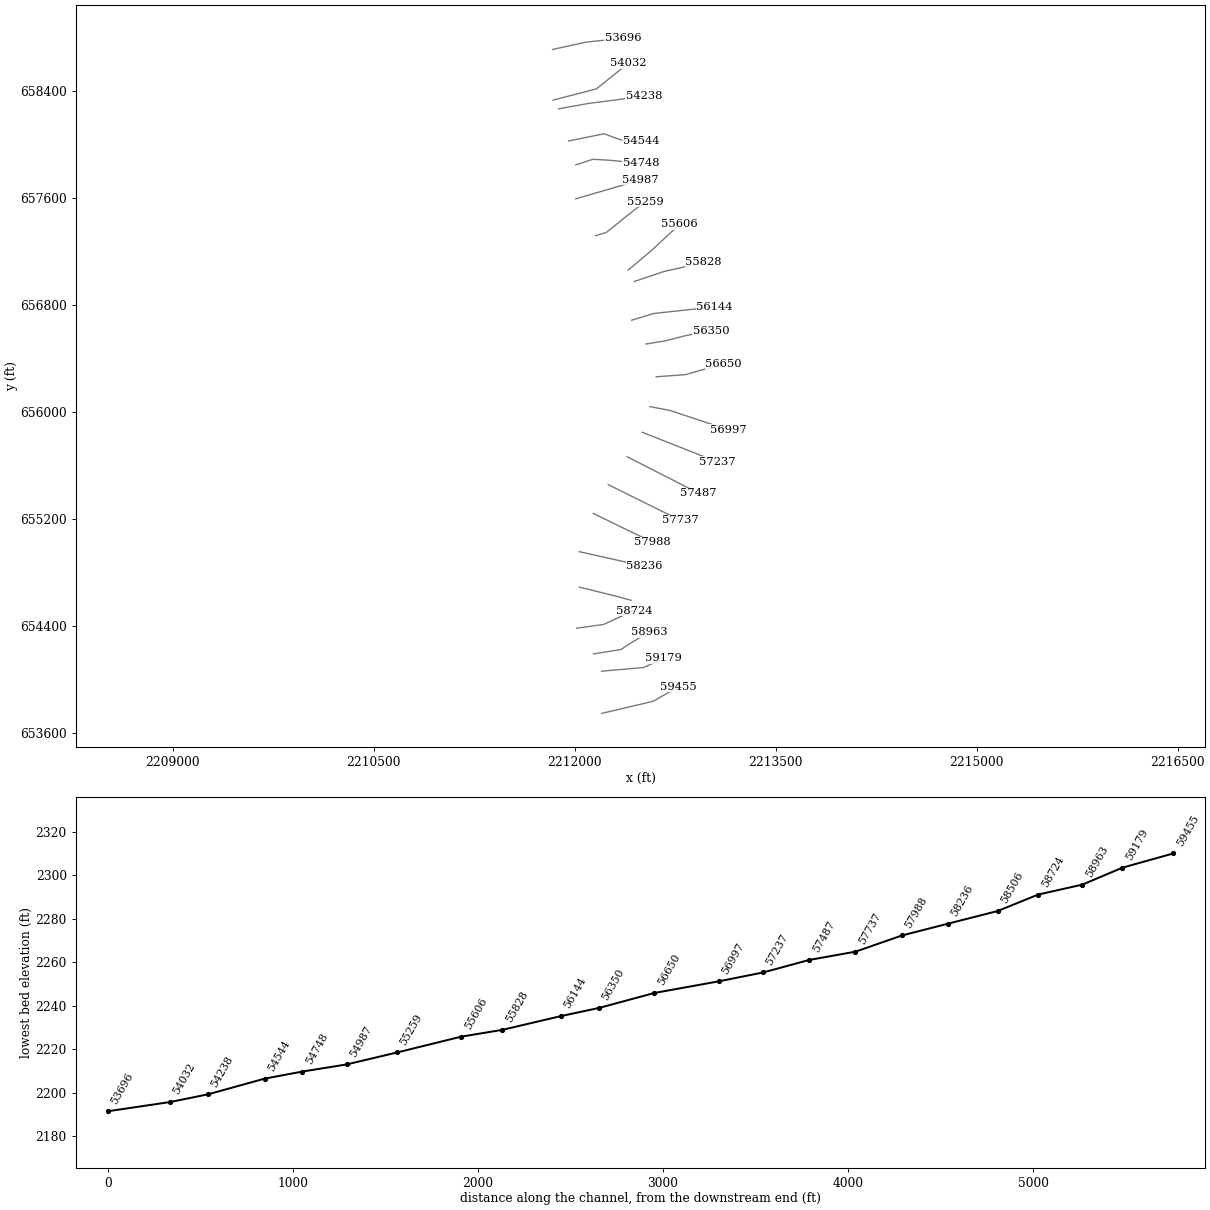
HEC-RAS study RFMIDDLERV.prj: RFMIDDLERV

--- RFMIDDLERV.g01 (geometry) --- (continued)

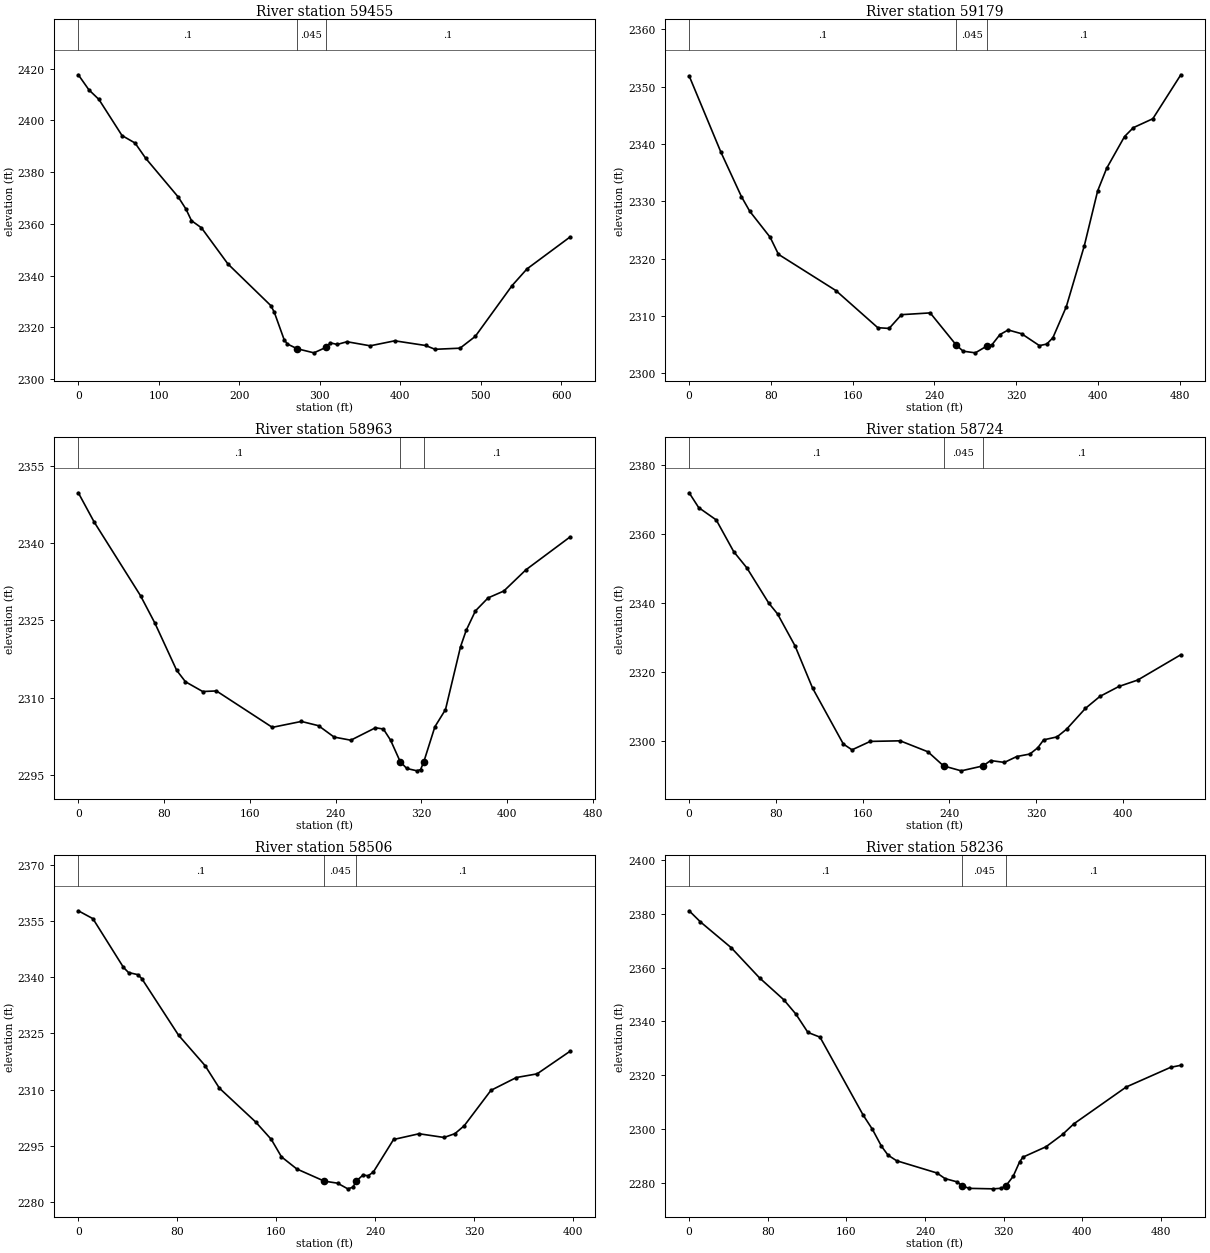
Type RM Length L Ch R = 1 ,59455   ,277.8,275.8,272.4
XS GIS Cut Line= 3
2212203.29059637653749.2452813842212587.71463607 653839.86026518
2212774.32885836653948.396392679
#Sta/Elev= 30
       0  2417.6    13.2 2411.76    25.6 2408.07    54.3 2394.11    70.5 2391.21
    83.8 2385.28   124.2 2370.32   133.7  2365.7   140.6  2361.2     153 2358.43
   185.8 2344.49   239.3 2328.32   243.5 2325.76   255.7 2315.19   259.8 2313.51
     2722311.684   292.7 2310.11   307.3 2312.18   313.2 2313.97   321.5 2313.35
   333.8  2314.4   362.6 2312.83   393.1 2314.76   431.4 2312.95   443.1 2311.48
   474.2 2311.91   493.1 2316.46   538.9 2336.13   557.4 2342.57   610.8 2354.88
#Mann= 3 ,-1,0
       0      .1       0     272    .045       0   307.3      .1       0
Bank Sta=272,307.3
XS Rating Curve= 0 ,0
Exp/Cntr(USF)=0,0
Exp/Cntr=0.3,0.1

Type RM Length L Ch R = 1 ,59179   ,207.5,216.4,219.5
XS GIS Cut Line= 3
2212201.15170513654064.0272957712212513.83002678654091.757009626
2212666.41396109654160.463324286
#Sta/Elev= 30
       0 2351.88    31.1 2338.56    51.2  2330.8    59.3 2328.26    79.3 2323.71
    87.4 2320.74   143.6 2314.42   184.6 2307.94   195.7 2307.81   207.8 2310.21
   235.9 2310.52   261.22304.952   268.1 2303.84   280.1 2303.55   291.52304.752
   296.2 2304.93   304.2 2306.74   312.2 2307.54   325.3 2306.89   342.8 2304.81
     350 2305.08     356 2306.19   369.1 2311.59   386.7 2322.21   399.8 2331.81
   408.6 2335.75   426.1 2341.29   434.7 2342.84   453.8  2344.4   481.2 2352.07
#Mann= 3 ,-1,0
       0      .1       0   261.2    .045       0   291.5      .1       0
Bank Sta=261.2,291.5
XS Rating Curve= 0 ,0
Exp/Cntr(USF)=0,0
Exp/Cntr=0.3,0.1

Type RM Length L Ch R = 1 ,58963   ,239.3,238.7,230.5
XS GIS Cut Line= 5
2212141.61446677654193.2915732732212346.87000711654226.348675621
2212408.14338386654267.8564469622212506.97141086 654326.49440965
2212560.52399219654357.182074336
#Sta/Elev= 30
       0 2349.84    14.7 2344.18      58 2329.82    71.5 2324.45    91.7 2315.31
    99.9 2313.08     116 2311.18   128.8 2311.29   180.9 2304.21     208 2305.36
     224 2304.53   238.5 2302.32   254.1 2301.71   277.1 2304.13   284.5 2303.88
   291.2 2301.71   300.2 2297.52   306.3 2296.21   315.9 2295.75   319.2 2296.01
   322.22297.531   332.5 2304.32   342.4 2307.67   356.4 2319.88   361.7 2323.08
   370.3 2326.86   382.1 2329.39   396.8 2330.73   417.3 2334.84   458.5 2341.24
#Mann= 3 ,-1,0
       0      .1       0   300.2    .045       0   322.2      .1       0
Bank Sta=300.2,322.2
XS Rating Curve= 0 ,0
Exp/Cntr(USF)=0,0
Exp/Cntr=0.3,0.1

Type RM Length L Ch R = 1 ,58724   ,227.1,218.3,206.5
XS GIS Cut Line= 4
2212015.45182779654385.3528939532212217.25521453 654413.53868943
2212380.50447395654488.9408137362212444.75311797654516.241485622
#Sta/Elev= 30
       0 2372.05     8.8 2367.74      25 2364.15    41.1 2354.93    53.2 2350.22
    73.4 2339.97    81.5 2336.83    97.7 2327.49   113.8 2315.26   142.2 2298.97
   150.2 2297.29     167 2299.74   194.6 2299.91   220.2 2296.72   234.62292.615
   250.9 2291.18     2712292.615     278 2294.17   290.7 2293.63   302.1 2295.34
   314.2 2296.07   321.5 2297.89   326.9 2300.19   339.2 2301.05     348 2303.28
   365.4 2309.34   378.8 2312.83   396.3 2315.72   413.6 2317.58   453.4 2324.95
#Mann= 3 ,-1,0
       0      .1       0   234.6    .045       0     271      .1       0
Bank Sta=234.6,271
XS Rating Curve= 0 ,0
Exp/Cntr(USF)=0,0
Exp/Cntr=0.3,0.1

Type RM Length L Ch R = 1 ,58506   ,267.1,269.5,270.5
XS GIS Cut Line= 3
2212036.75385841654691.7989390862212309.81203672654624.449468832
2212421.81713399654593.702971542
#Sta/Elev= 30
       0 2357.68    11.8 2355.58    36.5  2342.6    40.6 2341.23      48 2340.68
    51.3 2339.62      81 2324.55   102.4 2316.47     114 2310.45   143.3 2301.45
     156 2296.78   164.2 2292.15   176.6 2288.92   198.8 2285.68   209.5 2285.14
   217.8 2283.63   221.9 2284.06   224.72285.708   230.1 2287.31   234.2 2287.11
   238.4 2288.08   254.8 2296.77   275.4  2298.3   295.6 2297.31   304.4 2298.33
   311.9 2300.43   333.5 2309.86     354 2313.27   370.8 2314.25   397.4 2320.26
#Mann= 3 ,-1,0
       0      .1       0   198.8    .045       0   224.7      .1       0
Bank Sta=198.8,224.7
XS Rating Curve= 0 ,0
Exp/Cntr(USF)=0,0
Exp/Cntr=0.3,0.1

Type RM Length L Ch R = 1 ,58236   ,251.9,248.1,243.2
XS GIS Cut Line= 2
2212034.35177056654957.1249828792212522.24130079654847.512854569
#Sta/Elev= 30
       0 2381.15    11.5 2377.01    42.9 2367.39    71.6  2356.2    96.2  2348.1
   108.5 2342.78   120.8 2335.93   133.1 2334.17     177 2305.19   186.4 2299.91
   195.6 2293.63   202.3 2290.31     211 2288.23     252 2283.68   260.2  2281.6
   272.4 2280.38   277.82278.913   284.7 2277.96   309.2 2277.78   317.5 2277.99
   322.22278.919   329.5 2282.39   336.2 2287.86   339.6 2289.58     363 2293.43
   379.8    2298   391.3 2301.95   444.6 2315.65   489.7 2322.95   500.1 2323.71
#Mann= 3 ,-1,0
       0      .1       0   277.8    .045       0   322.2      .1       0
Bank Sta=277.8,322.2
XS Rating Curve= 0 ,0
Exp/Cntr(USF)=0,0
Exp/Cntr=0.3,0.1

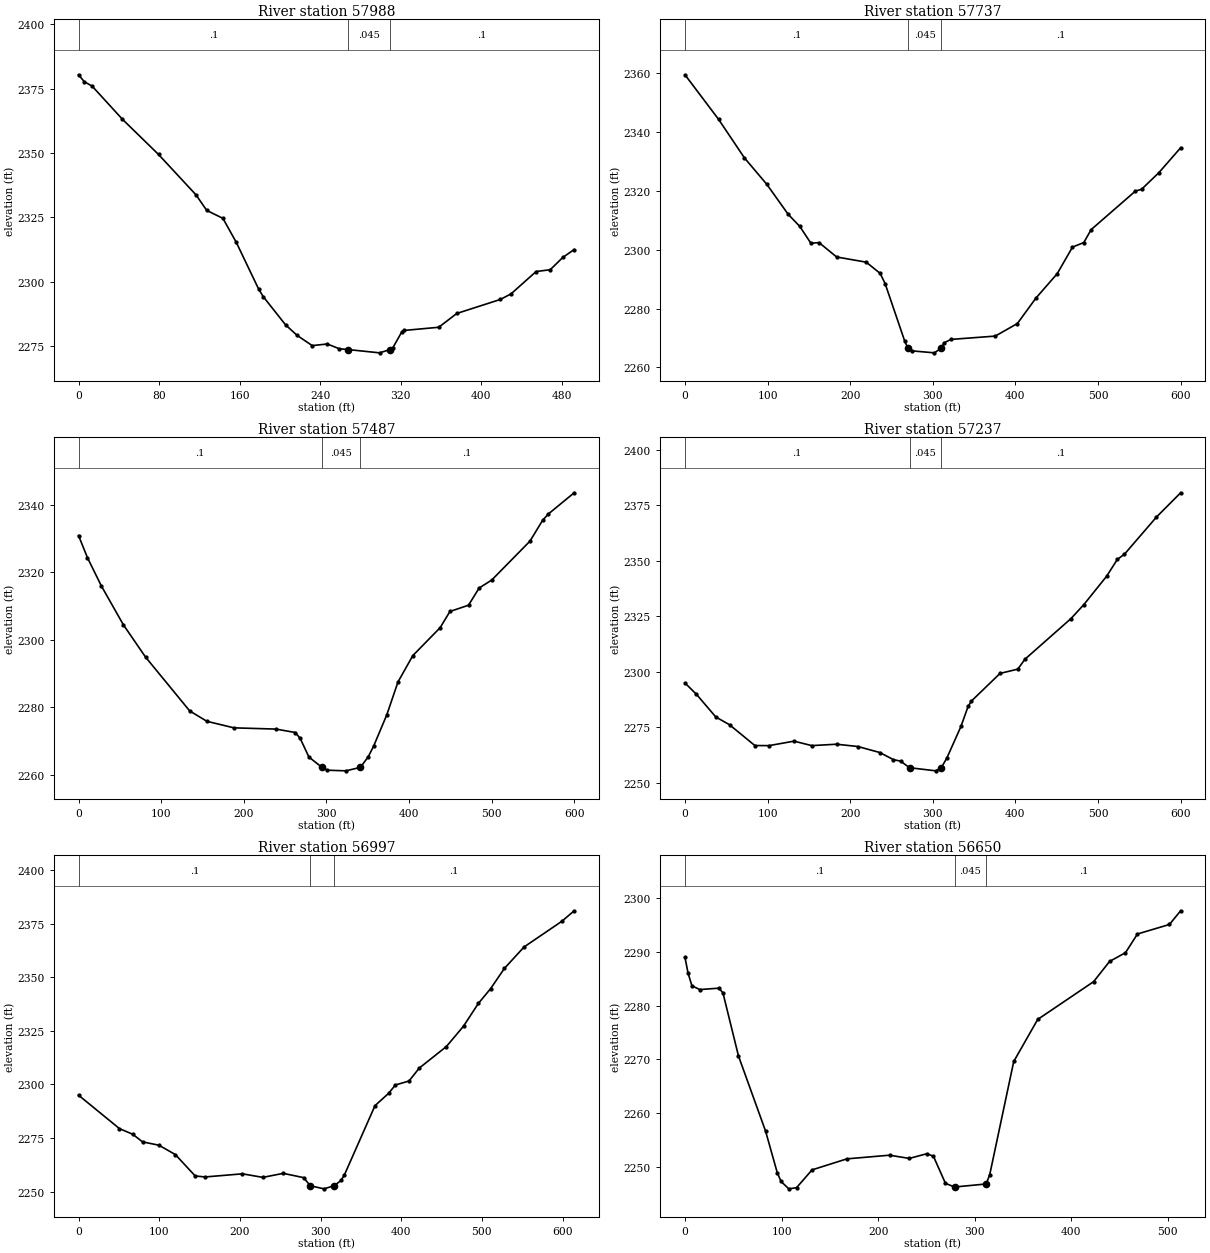
Type RM Length L Ch R = 1 ,57988   ,246.9,251.5,249.9
XS GIS Cut Line= 2
2212139.04806343655242.2722674562212582.20999335655027.415398753
#Sta/Elev= 30
       0 2380.45     5.7 2377.78    13.6 2376.01    43.6 2363.17    79.5 2349.48
   116.8 2333.75   127.4 2327.73   143.5 2324.64   156.8 2315.29   179.1 2297.06
   183.5 2294.25   205.7 2283.26   217.2 2279.16   232.2 2275.18   247.2 2275.81
   259.1 2273.97   268.22273.627   299.1 2272.37   309.42273.628   312.4  2274.4
   321.3 2280.55   323.4 2281.07   357.9 2282.31   375.9 2287.68   419.1 2293.11
   429.8  2295.3   454.7 2303.98   468.7 2304.67   481.3 2309.48   492.5 2312.52
#Mann= 3 ,-1,0
       0      .1       0   268.2    .045       0   309.4      .1       0
Bank Sta=268.2,309.4
XS Rating Curve= 0 ,0
Exp/Cntr(USF)=0,0
Exp/Cntr=0.3,0.1

Type RM Length L Ch R = 1 ,57737   ,253.3,250,254.2
XS GIS Cut Line= 2
2212251.62639045655457.2599468882212789.22696779655190.828681367
#Sta/Elev= 30
       0 2359.56    40.8 2344.34      72 2331.26      99 2322.29   124.9 2312.08
     139 2307.94   152.4 2302.23   162.3 2302.43   183.6 2297.54   219.4 2295.77
   236.3 2291.95   242.3 2288.46   266.1 2268.81     2702266.476   275.1 2265.57
     302 2264.91   309.92266.454   313.9 2268.37     322 2269.48   375.6 2270.61
   402.4 2274.89   424.7  2283.5   450.6 2291.86   469.1  2300.9   482.8 2302.46
   491.7 2306.86   545.3 2319.98   552.7 2320.58   573.6 2326.22     600 2334.71
#Mann= 3 ,-1,0
       0      .1       0     270    .045       0   309.9      .1       0
Bank Sta=270,309.9
XS Rating Curve= 0 ,0
Exp/Cntr(USF)=0,0
Exp/Cntr=0.3,0.1

Type RM Length L Ch R = 1 ,57487   ,247.1,250,250.5
XS GIS Cut Line= 2
2212391.93152245655666.1031378362212926.06618848655392.789840421
#Sta/Elev= 30
       0 2330.83    10.8 2324.27    27.6 2315.91    54.2 2304.42    81.1 2294.82
   134.6 2278.85   155.4 2275.78   188.1 2273.84   239.1 2273.47   262.4 2272.46
   268.4 2270.69   278.9 2265.19   294.72262.129   301.3 2261.29   323.8  2261.1
   341.22262.134   350.7 2265.25   357.3 2268.45   373.2  2277.7   386.7 2287.42
   404.7 2295.25   437.8 2303.53   449.6 2308.32   472.1 2310.17     485 2315.28
   500.2 2317.63   546.5 2329.16   561.9 2335.36   568.9 2337.24     600 2343.49
#Mann= 3 ,-1,0
       0      .1       0   294.7    .045       0   341.2      .1       0
Bank Sta=294.7,341.2
XS Rating Curve= 0 ,0
Exp/Cntr(USF)=0,0
Exp/Cntr=0.3,0.1

Type RM Length L Ch R = 1 ,57237   ,236.6,239.8,239.3
XS GIS Cut Line= 2
2212505.46046767 655848.548407112213063.42683945655627.927628471
#Sta/Elev= 30
       0  2294.9    13.9  2289.8    37.3 2279.59      54 2276.07    84.6 2266.72
   101.8 2266.69     132  2268.7   153.5 2266.69   183.5 2267.32   209.4 2266.28
   235.9 2263.57   252.4 2260.36     261  2259.7   271.82256.738   303.7 2255.33
   310.22256.727   316.9    2261   334.1 2275.35   342.7 2284.33   346.8 2286.78
   381.4 2299.21   402.9 2301.14   411.5 2305.59   467.1 2323.85   482.5 2330.05
   510.5 2343.02   523.4 2350.57     532  2352.9   570.7 2369.62     600 2380.57
#Mann= 3 ,-1,0
       0      .1       0   271.8    .045       0   310.2      .1       0
Bank Sta=271.8,310.2
XS Rating Curve= 0 ,0
Exp/Cntr(USF)=0,0
Exp/Cntr=0.3,0.1

Type RM Length L Ch R = 1 ,56997   ,339.3,346.5,357.8
XS GIS Cut Line= 3
2212562.27328534656040.3367045052212713.87384439656010.866731343
2213150.54103527655866.229333731
#Sta/Elev= 30
       0 2294.99    50.8 2279.36    67.1 2276.76    79.4 2273.18    99.7 2271.62
   120.1 2267.24   144.6 2257.27   156.9  2256.8   203.2 2258.26   228.5  2256.6
   253.8 2258.48   279.1 2256.48   287.32252.682   304.3 2251.25   316.92252.707
   325.4 2255.15   329.6 2257.76   367.5 2290.09   384.4 2295.85   392.8 2299.75
   409.7  2301.6   422.3 2307.61     456 2317.69   477.3 2327.23   495.6 2337.81
   510.8 2344.71   527.9 2354.17   552.3 2364.19   599.3 2376.23   614.4 2381.09
#Mann= 3 ,-1,0
       0      .1       0   287.3    .045       0   316.9      .1       0
Bank Sta=287.3,316.9
XS Rating Curve= 0 ,0
Exp/Cntr(USF)=0,0
Exp/Cntr=0.3,0.1

Type RM Length L Ch R = 1 ,56650   ,304.5,300.6,301.2
XS GIS Cut Line= 4
2212608.95356345656262.799492602 2212828.9486653656279.138151441
2212941.41870569656311.2724486932213111.45906175656355.385120667
#Sta/Elev= 30
       0 2288.99     3.2 2286.05     7.2  2283.7    15.3    2283    35.1 2283.26
    39.3 2282.39    55.4 2270.64    83.5 2256.63    95.5 2248.95    99.5 2247.29
   107.5 2245.92   115.5 2246.13   131.6 2249.45   167.7  2251.5   211.8 2252.18
   232.3 2251.58   250.7 2252.47   257.3 2251.96   269.7 2246.94   279.12246.261
   311.82246.824   315.5 2248.53   340.4 2269.62   365.2 2277.44   423.1 2284.47
   439.6 2288.23   456.1 2289.86   468.5 2293.34   501.6 2295.11   513.2 2297.66
#Mann= 3 ,-1,0
       0      .1       0   279.1    .045       0   311.8      .1       0
Bank Sta=279.1,311.8
XS Rating Curve= 0 ,0
Exp/Cntr(USF)=0,0
Exp/Cntr=0.3,0.1

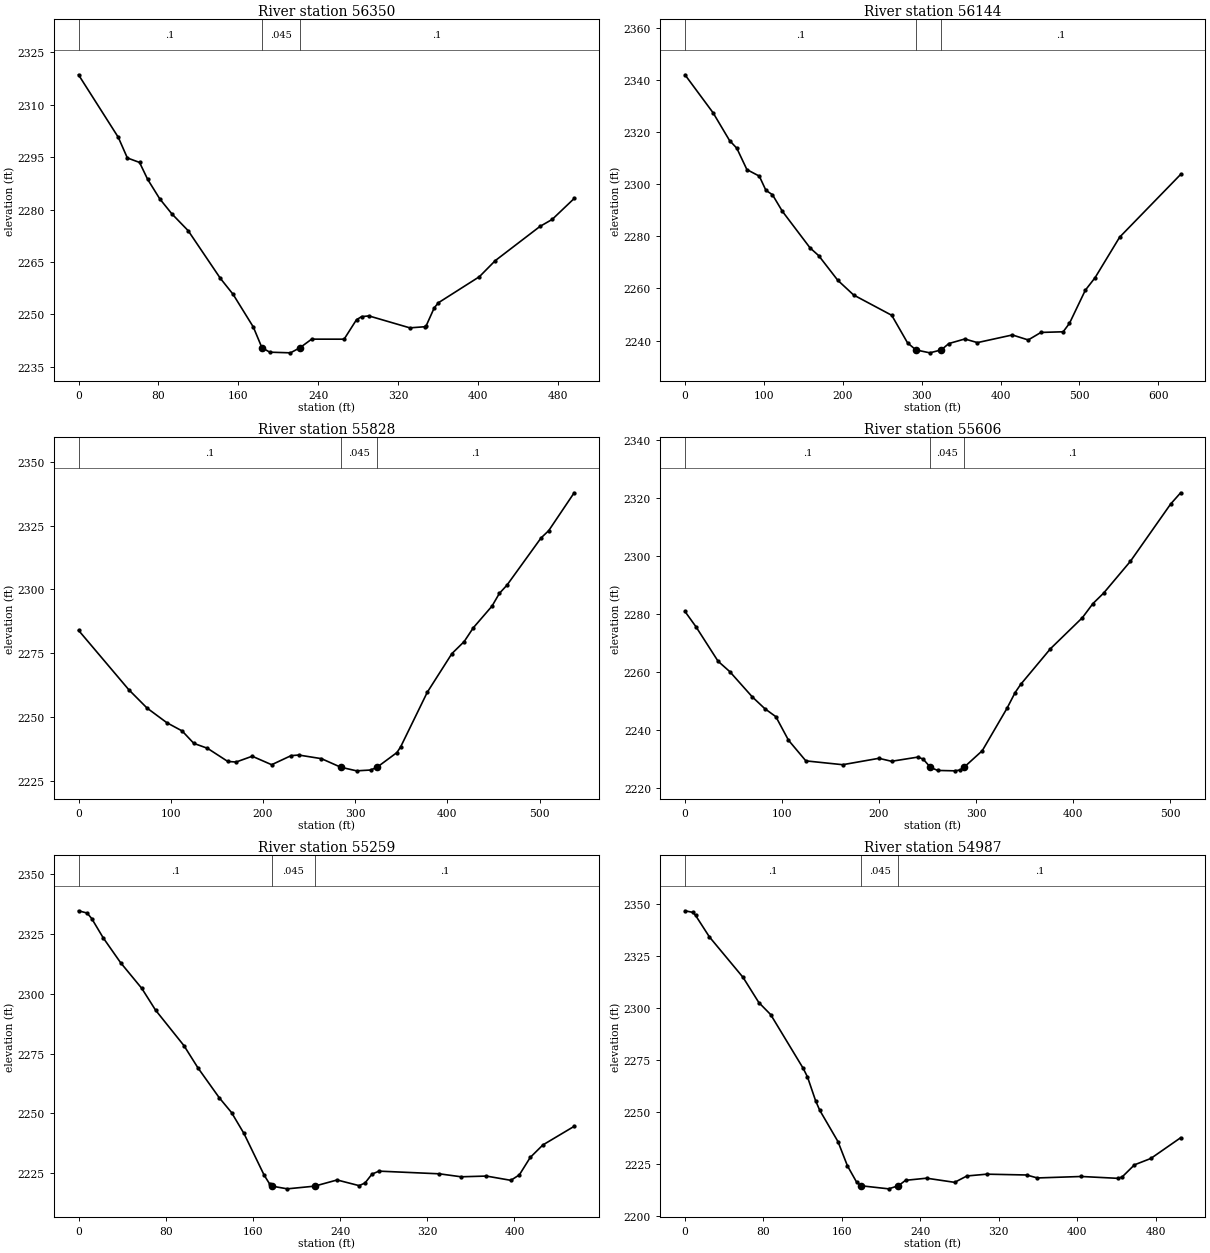
Type RM Length L Ch R = 1 ,56350   ,209.1,205.7,203
XS GIS Cut Line= 5
2212531.94159793656507.5875446062212597.01425671656518.385549301
2212675.34160626 656530.435910772212829.98791179656570.603782335
2213017.77271136656606.754866744
#Sta/Elev= 30
       0  2318.6    39.8 2300.71    48.9 2294.79    61.1 2293.51    69.2 2288.68
    81.3  2283.1    93.4 2278.81   109.8 2273.97     142 2260.33   154.7 2255.78
     175  2246.4   183.6 2240.49   191.5  2239.2   212.2 2239.01   221.72240.474
   233.4 2242.93   265.9 2242.92   278.3  2248.5   283.4 2249.37   290.7 2249.58
   331.7 2246.16   346.6 2246.48     348 2246.72   356.1 2251.88   360.3 2253.35
   401.3  2260.8   417.2  2265.4     462  2275.2   474.2  2277.2   496.2 2283.19
#Mann= 3 ,-1,0
       0      .1       0   183.6    .045       0   221.7      .1       0
Bank Sta=183.6,221.7
XS Rating Curve= 0 ,0
Exp/Cntr(USF)=0,0
Exp/Cntr=0.3,0.1

Type RM Length L Ch R = 1 ,56144   ,313.9,316.2,319.6
XS GIS Cut Line= 3
2212426.08801853656685.2304621632212590.81176974656735.488102775
2213044.26148516656784.768566432
#Sta/Elev= 30
       0 2342.09    35.6  2327.5    56.5 2316.84    65.7 2313.88    78.5 2305.66
    94.2 2303.16   102.6 2297.69   110.9 2296.01   123.4 2289.67   158.6 2275.57
   169.5 2272.61   193.7 2263.14   213.8 2257.49   262.1 2249.69   282.2 2239.07
   292.82236.387   310.4 2235.27   324.82236.393   334.5 2238.84   354.7 2240.59
   370.7  2239.2     415 2242.14   435.1 2240.22   451.2 2243.11   479.4 2243.36
   487.4 2246.62   507.5 2259.34   519.8 2264.12     551 2279.71   628.3 2303.81
#Mann= 3 ,-1,0
       0      .1       0   292.8    .045       0   324.8      .1       0
Bank Sta=292.8,324.8
XS Rating Curve= 0 ,0
Exp/Cntr(USF)=0,0
Exp/Cntr=0.3,0.1

Type RM Length L Ch R = 1 ,55828   ,212.2,222.2,232.8
XS GIS Cut Line= 4
2212445.65054377656974.6007494292212667.70857976657049.433494155
2212792.15868783657077.0890737282212963.06648111657118.286379278
#Sta/Elev= 30
       0 2284.01    54.5 2260.74    74.4 2253.52    95.8  2247.8   112.4 2244.57
   125.1 2239.69   139.8 2237.79   161.9 2232.62   170.9 2232.39   188.4 2234.66
   209.5 2231.34   230.6  2234.9   238.9 2235.13   263.5 2233.71   284.5 2230.35
   301.6 2228.94   316.8 2229.26   323.82230.347   345.4 2236.11   349.5 2238.41
   378.3 2259.74     405 2274.88   418.3 2279.59   428.2 2284.99   448.5 2293.49
   456.5 2298.48   464.7 2301.69   501.7  2320.2     510 2323.06   537.6 2337.89
#Mann= 3 ,-1,0
       0      .1       0   284.5    .045       0   323.8      .1       0
Bank Sta=284.5,323.8
XS Rating Curve= 0 ,0
Exp/Cntr(USF)=0,0
Exp/Cntr=0.3,0.1

Type RM Length L Ch R = 1 ,55606   ,343.3,347.1,339.4
XS GIS Cut Line= 3
2212400.81895917657060.5260750432212577.93215946657209.396240638
2212782.24905076 657400.21973969
#Sta/Elev= 30
       0 2280.87    11.4 2275.55    34.1 2263.68    46.2 2260.08    69.4 2251.35
    82.3 2247.29    93.7 2244.51   106.7 2236.39   124.6 2229.25   162.6 2227.93
   199.9 2230.14   212.9 2229.11   239.9 2230.55   245.4  2229.9     2532227.021
   260.4 2225.95   278.2 2225.81   283.7 2226.12   287.62227.029   306.4 2232.75
   331.9  2247.4   340.3 2252.85     346 2255.66   376.7 2267.99   409.6 2278.71
   420.5 2283.59   431.5  2287.2   459.2 2298.23   500.6 2317.98   510.9 2321.87
#Mann= 3 ,-1,0
       0      .1       0     253    .045       0   287.6      .1       0
Bank Sta=253,287.6
XS Rating Curve= 0 ,0
Exp/Cntr(USF)=0,0
Exp/Cntr=0.3,0.1

Type RM Length L Ch R = 1 ,55259   ,278.1,271.8,263.2
XS GIS Cut Line= 4
2212156.64488293657316.4407256122212236.88020639657341.143966624
2212420.34695976 657488.459635592212528.19769491657570.502513262
#Sta/Elev= 30
       0 2334.58     7.9 2333.63    12.1 2331.34    22.6 2323.33    38.6 2312.93
    58.1 2302.17    70.7 2293.11    96.8 2278.27   109.6 2269.01   129.2 2256.51
   140.4 2250.38   151.8 2241.64   170.3 2224.27   175.4 2220.54   177.82219.635
   191.6 2218.53   216.6 2219.65   237.3 2222.23   257.5 2219.86   262.9 2220.98
   269.3 2224.67   275.7 2225.92   331.1  2224.8     351 2223.56   374.3 2223.86
   396.7 2222.08   404.5 2224.36   414.5 2231.64   426.1 2236.85   454.8 2244.62
#Mann= 3 ,-1,0
       0      .1       0   177.8    .045       0   216.6      .1       0
Bank Sta=177.8,216.6
XS Rating Curve= 0 ,0
Exp/Cntr(USF)=0,0
Exp/Cntr=0.3,0.1

Type RM Length L Ch R = 1 ,54987   ,247.6,239.3,235.1
XS GIS Cut Line= 2
2212008.25714457657591.7491150232212493.35425494657733.072370511
#Sta/Elev= 30
       0 2346.54     8.2 2345.75    10.8 2344.32    24.9    2334    59.2 2314.57
    75.3 2302.48    87.4 2296.67   120.5  2270.9   124.9 2266.76   133.2 2255.29
   137.4 2250.75     156  2235.7   165.6  2224.1   174.9 2216.31   179.42214.521
   207.6 2213.04   217.62214.535   224.9 2217.13   246.3 2218.15   274.9 2216.16
   287.4 2219.22   307.6 2220.08   348.3 2219.69   359.2 2218.27     404 2218.97
   441.5 2218.08   445.7 2218.76   458.2 2224.56   474.9 2227.62   505.3 2237.57
#Mann= 3 ,-1,0
       0      .1       0   179.4    .045       0   217.6      .1       0
Bank Sta=179.4,217.6
XS Rating Curve= 0 ,0
Exp/Cntr(USF)=0,0
Exp/Cntr=0.3,0.1

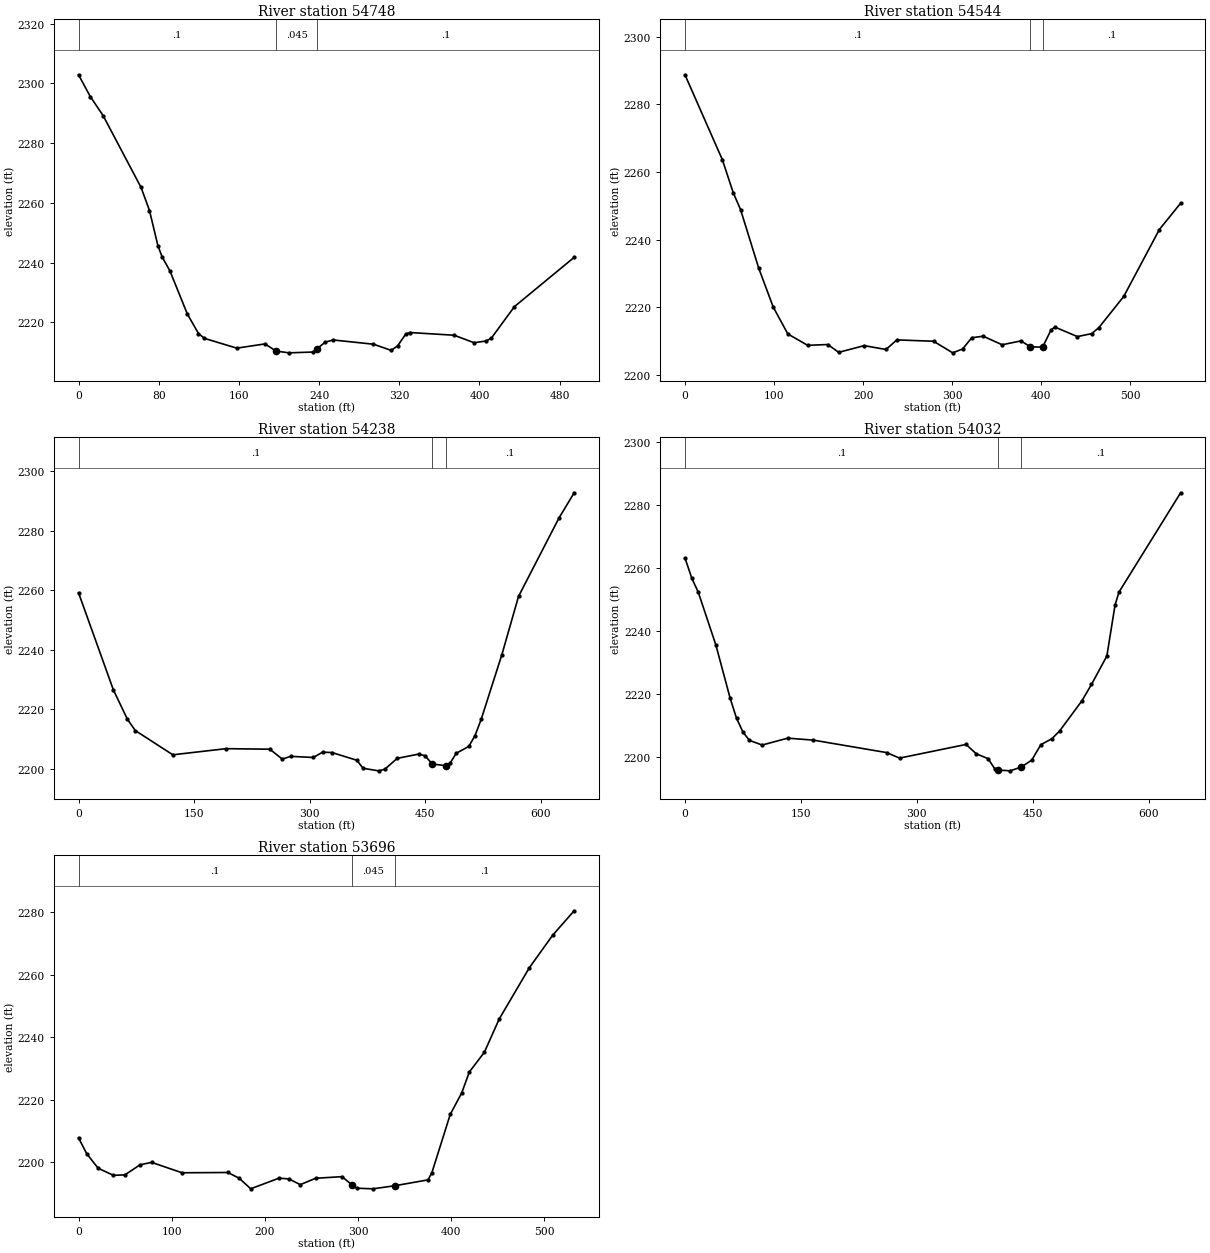
Type RM Length L Ch R = 1 ,54748   ,210.9,204,188
XS GIS Cut Line= 4
2212008.89706769  657845.48848222212136.55862818657887.135062225
2212252.52614559657880.5948798912212495.50588891657857.269281488
#Sta/Elev= 30
       0 2302.91    11.9 2295.53    24.5 2289.26    62.4 2265.17    70.8 2257.44
    79.2 2245.67    83.4  2241.9    91.2 2237.21   108.6 2222.75   119.7 2216.23
   125.5 2214.62   157.9 2211.33     186 2212.75   197.12210.352     210 2209.76
   234.1 2210.03   238.32211.213   246.1 2213.34   254.1 2214.07   294.3 2212.65
   311.9 2210.59   318.4 2212.11   326.4 2216.01   330.4 2216.57   374.7 2215.66
   394.7 2213.14   406.8 2213.75   411.8 2214.65   434.9 2225.24   494.5 2241.75
#Mann= 3 ,-1,0
       0      .1       0   197.1    .045       0   238.3      .1       0
Bank Sta=197.1,238.3
XS Rating Curve= 0 ,0
Exp/Cntr(USF)=0,0
Exp/Cntr=0.3,0.1

Type RM Length L Ch R = 1 ,54544   ,302.6,305.9,309.4
XS GIS Cut Line= 5
2211955.04925214658023.7035900212212220.96975159658078.050605692
2212290.44482975658051.3454812322212379.61982967658021.132757625
2212496.03449297 658024.20806169
#Sta/Elev= 30
       0 2288.76      42 2263.61    54.2 2253.86    62.4 2248.88    82.8 2231.54
    99.1 2220.03   115.5 2212.08   137.8 2208.72   160.4 2208.96   172.6 2206.65
   201.2 2208.63   225.7 2207.49   237.9 2210.33   279.1 2209.93   300.6  2206.5
   311.7 2207.64     322 2210.96   334.8 2211.42   356.1 2208.89   377.2 2210.03
   387.82208.272   401.52208.182     411 2213.27   415.2 2214.13   440.6 2211.31
   456.6 2212.18   464.6 2213.93   492.6 2223.17   532.6 2242.97   556.5 2250.77
#Mann= 3 ,-1,0
       0      .1       0   387.8    .045       0   401.5      .1       0
Bank Sta=387.8,401.5
XS Rating Curve= 0 ,0
Exp/Cntr(USF)=0,0
Exp/Cntr=0.3,0.1

Type RM Length L Ch R = 1 ,54238   ,202,205.7,206
XS GIS Cut Line= 4
2211879.67232555658264.0209401422212104.86410515658304.537944554
2212310.71328918 658330.903689142212515.70279818658359.645507303
#Sta/Elev= 30
       0 2259.14    45.2 2226.53    63.4 2216.65    73.7 2212.83   122.4 2204.68
   191.5 2206.74   248.3 2206.56   264.5 2203.23   275.2 2204.16   304.7 2203.78
   316.8 2205.56     329 2205.44   361.2 2202.84   369.3 2200.15   389.4 2199.29
   397.5 2199.82   413.6 2203.48   441.9 2204.94   449.9 2204.33     459  2201.6
   476.42201.025   482.2 2201.87   490.3 2205.21   506.5 2207.49   514.6 2211.12
   522.6 2216.57   549.5 2238.35   571.1 2257.92   623.6 2284.26   643.3 2292.73
#Mann= 3 ,-1,0
       0      .1       0     459    .045       0   476.4      .1       0
Bank Sta=459,476.4
XS Rating Curve= 0 ,0
Exp/Cntr(USF)=0,0
Exp/Cntr=0.3,0.1

Type RM Length L Ch R = 1 ,54032   ,341.6,335.5,322.2
XS GIS Cut Line= 3
2211839.56387212658329.0574175742212162.62224813658412.694372248
2212402.31170375658605.176375466
#Sta/Elev= 30
       0 2263.29     8.9 2256.81    17.2 2252.41      40 2235.64    58.5 2218.71
    66.7  2212.4      75 2208.04    83.3 2205.41    99.8 2203.92   132.9  2206.1
   165.9 2205.48   260.9 2201.52   277.5 2199.77   363.6 2204.11   376.7 2201.14
     392 2199.61   400.6 2196.42   404.62195.996   420.5 2195.73   435.12196.934
   448.6 2199.16   460.3 2204.03   474.6 2205.93   484.5 2208.36   513.4 2217.96
   525.8 2223.15   545.7 2232.19   556.3 2248.39   561.4 2252.48   641.1 2283.98
#Mann= 3 ,-1,0
       0      .1       0   404.6    .045       0   435.1      .1       0
Bank Sta=404.6,435.1
XS Rating Curve= 0 ,0
Exp/Cntr(USF)=0,0
Exp/Cntr=0.3,0.1

Type RM Length L Ch R = 1 ,53696   ,171.2,175.9,176.2
XS GIS Cut Line= 3
2211835.59984712  658707.30008872212088.65743798658762.530912103
2212360.12058852658790.455924805
#Sta/Elev= 30
       0 2207.84     8.8 2202.75    21.1  2198.1    37.4 2195.84    49.7 2195.97
    66.1  2199.2    78.4 2199.98   111.1 2196.65   160.3 2196.74   172.5 2194.89
   184.8 2191.53   215.2 2194.93   225.8 2194.68     238 2192.85   254.4 2194.89
   282.7 2195.41   293.32192.832   298.7 2191.72   315.7 2191.51   339.42192.503
   375.1 2194.38   379.2 2196.66   398.9 2215.32   411.3 2222.25   419.4  2228.9
   435.5  2235.2   451.5 2245.87   483.7 2262.21   508.9 2272.69   531.9 2280.48
#Mann= 3 ,-1,0
       0      .1       0   293.3    .045       0   339.4      .1       0
Bank Sta=293.3,339.4
XS Rating Curve= 0 ,0
Exp/Cntr(USF)=0,0
Exp/Cntr=0.3,0.1