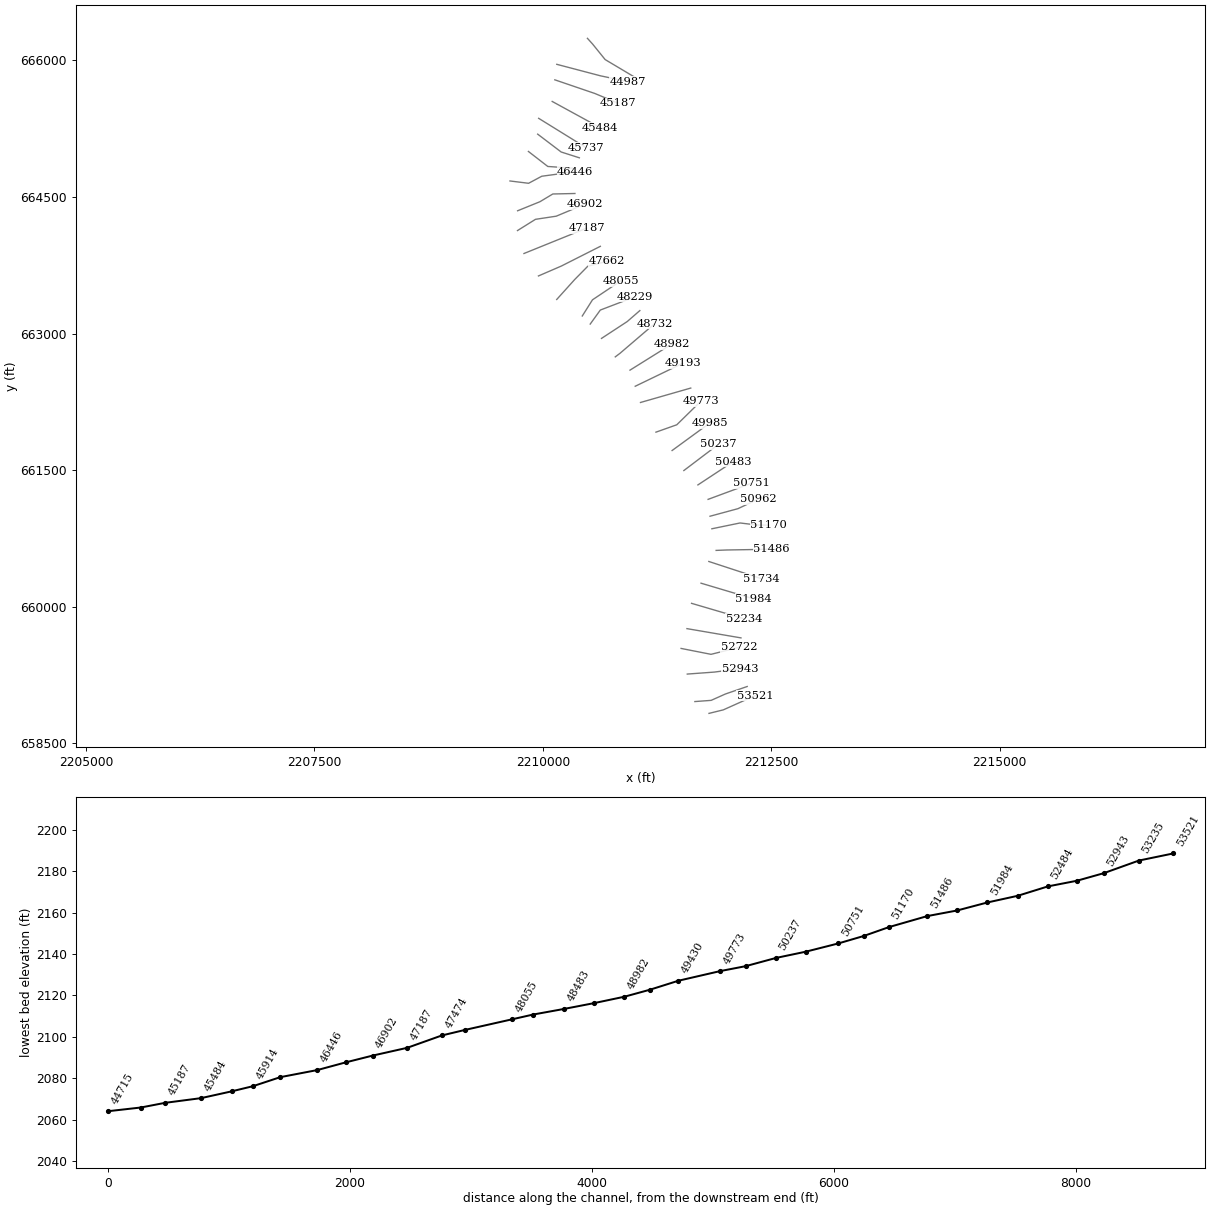
HEC-RAS study RFMIDDLERV.prj: RFMIDDLERV

--- RFMIDDLERV.g01 (geometry) --- (continued)

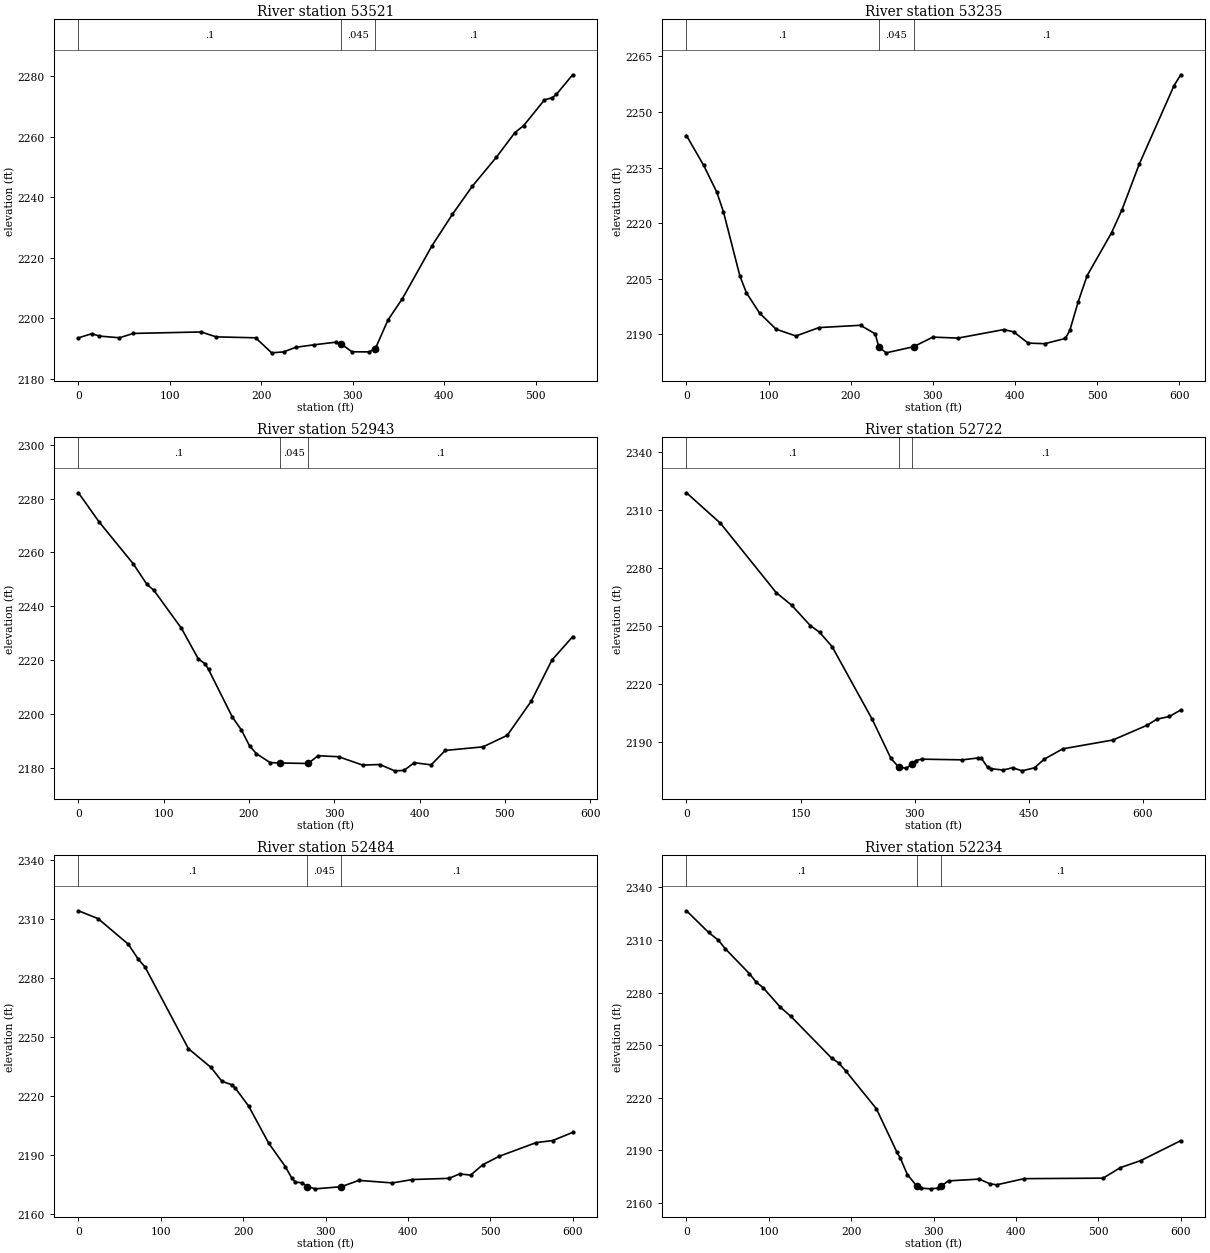
Type RM Length L Ch R = 1 ,53521   ,277.2,285.8,267.5
XS GIS Cut Line= 3
2211817.90945795658829.0770772092211974.48939669658867.584580877
2212320.33756085659023.120461466
#Sta/Elev= 30
       0 2193.45    14.7 2194.84    22.9 2194.04    44.9 2193.48      60 2194.92
   134.2  2195.4   150.6 2193.78   193.8 2193.47   211.3  2188.5   224.5 2188.82
   237.7 2190.34   257.5 2191.15   281.5 2192.02   287.52191.413   299.1 2188.85
     318 2188.81     3242189.851   325.4 2190.35   338.5 2199.34   354.3 2206.42
   386.8 2223.96   408.9 2234.25   430.6 2243.51   457.2 2253.21   477.2 2261.24
     487 2263.65   509.6 2272.09   518.4 2272.87   522.7 2273.94   540.5 2280.42
#Mann= 3 ,-1,0
       0      .1       0   287.5    .045       0     324      .1       0
Bank Sta=287.5,324
XS Rating Curve= 0 ,0
Exp/Cntr(USF)=0,0
Exp/Cntr=0.3,0.1

Type RM Length L Ch R = 1 ,53235   ,296.2,292,283.2
XS GIS Cut Line= 4
2211663.33390351658958.7546063612211841.43688985658971.952557696
 2211997.6095745659041.9049060272212235.78524779659124.108847903
#Sta/Elev= 30
       0 2243.63    20.9 2235.61    36.9 2228.38      45 2223.07      65 2205.78
      73 2201.22    89.1 2195.74   109.1 2191.42   133.2  2189.6   161.3 2191.86
   211.9 2192.48   229.8 2190.15   234.12186.669     243 2185.05   276.42186.697
   299.9 2189.29   330.6 2189.03   386.3 2191.32   398.3 2190.71   415.9 2187.68
   436.1 2187.51   461.3 2188.93   466.7 2191.11     477 2198.89   487.8 2205.89
   517.5 2217.42   530.2 2223.63   551.3 2235.98   593.6 2257.11   601.7 2260.03
#Mann= 3 ,-1,0
       0      .1       0   234.1    .045       0   276.4      .1       0
Bank Sta=234.1,276.4
XS Rating Curve= 0 ,0
Exp/Cntr(USF)=0,0
Exp/Cntr=0.3,0.1

Type RM Length L Ch R = 1 ,52943   ,220.2,220.9,218.1
XS GIS Cut Line= 3
2211580.04700024659260.6776206092211875.66245102659282.458648965
2212156.26261439659319.094547295
#Sta/Elev= 30
       0 2282.16    24.2 2271.35    64.3 2255.77    80.3 2248.15    88.4 2245.97
   120.8 2231.82   140.5  2220.5   148.5 2218.64   152.5 2216.58   180.6  2198.8
   191.1 2194.07   200.7 2188.15   208.7 2185.29   224.7    2182   235.9 2181.85
   269.32181.658   280.9 2184.54     305 2184.17   333.2 2181.06   353.4 2181.28
   370.7 2178.93   381.6 2179.08   393.7 2181.95   413.5 2181.15   430.1 2186.51
   474.4 2187.84   502.7  2192.1   530.9 2204.82   555.1 2220.05   579.4 2228.72
#Mann= 3 ,-1,0
       0      .1       0   235.9    .045       0   269.3      .1       0
Bank Sta=235.9,269.3
XS Rating Curve= 0 ,0
Exp/Cntr(USF)=0,0
Exp/Cntr=0.3,0.1

Type RM Length L Ch R = 1 ,52722   ,235,238.2,239.5
XS GIS Cut Line= 3
2211512.37378104659542.1803593932211840.04994118659477.413317183
2212146.62307908659554.451261799
#Sta/Elev= 30
       0 2318.86    44.6 2303.15     118 2267.32   138.4 2260.79   162.9 2250.29
   175.1 2246.84   191.6 2239.39   244.4 2201.83   268.9 2181.71   279.42177.105
   289.3 2176.67   296.42178.714   301.5 2180.63   309.7 2181.32     363 2180.98
   383.6 2181.95   387.8 2181.81     396 2177.18   400.1 2176.42   416.6 2175.71
     429 2176.91   441.4  2175.3   457.9 2176.88   470.2 2181.24     495 2186.66
     561 2191.23   606.4 2198.94   618.7 2201.96   635.2 2203.36   650.1 2206.71
#Mann= 3 ,-1,0
       0      .1       0   279.4    .045       0   296.4      .1       0
Bank Sta=279.4,296.4
XS Rating Curve= 0 ,0
Exp/Cntr(USF)=0,0
Exp/Cntr=0.3,0.1

Type RM Length L Ch R = 1 ,52484   ,251.7,250,248.6
XS GIS Cut Line= 2
2211576.57762695659759.5280933772212167.91460058659657.937820132
#Sta/Elev= 30
       0 2314.18    23.9 2310.17    60.5 2297.16    72.6 2289.55    80.8 2285.59
   133.5 2243.98     161 2234.39   174.1 2227.38   186.3 2225.57   190.3 2223.95
   206.6 2214.76   230.9 2195.92   251.1 2183.96   259.3 2177.87   263.4 2176.06
   271.5 2175.65     278 2173.71   287.8  2172.6   319.22173.693   340.5 2176.91
   381.1 2175.61   405.5 2177.34   450.1 2177.94   462.7  2180.2   476.2 2179.58
   490.7 2184.82   510.8 2189.17   555.6 2196.12   575.9 2197.21     600 2201.33
#Mann= 3 ,-1,0
       0      .1       0     278    .045       0   319.2      .1       0
Bank Sta=278,319.2
XS Rating Curve= 0 ,0
Exp/Cntr(USF)=0,0
Exp/Cntr=0.3,0.1

Type RM Length L Ch R = 1 ,52234   ,249.9,250,252.9
XS GIS Cut Line= 2
2211626.99180616660037.3181214362212202.51580291659867.694629086
#Sta/Elev= 30
       0 2326.69    26.8 2314.36    38.8 2309.86    47.1 2305.03    76.3 2290.85
    84.6 2285.99      93 2282.83   113.8 2271.75   126.7 2266.45   176.4 2242.55
   184.7 2239.89   193.1 2235.47   230.6 2213.72   255.6 2188.85   259.8  2185.4
   268.1 2176.23   279.32169.788   284.8 2168.41   297.2 2168.06   305.7 2168.55
   309.32169.791   318.2  2172.6   355.4 2173.62   368.1 2170.98   376.5 2170.35
   409.9 2173.87   505.8 2174.16   526.7 2180.15   551.7 2184.22     600 2195.52
#Mann= 3 ,-1,0
       0      .1       0   279.3    .045       0   309.3      .1       0
Bank Sta=279.3,309.3
XS Rating Curve= 0 ,0
Exp/Cntr(USF)=0,0
Exp/Cntr=0.3,0.1

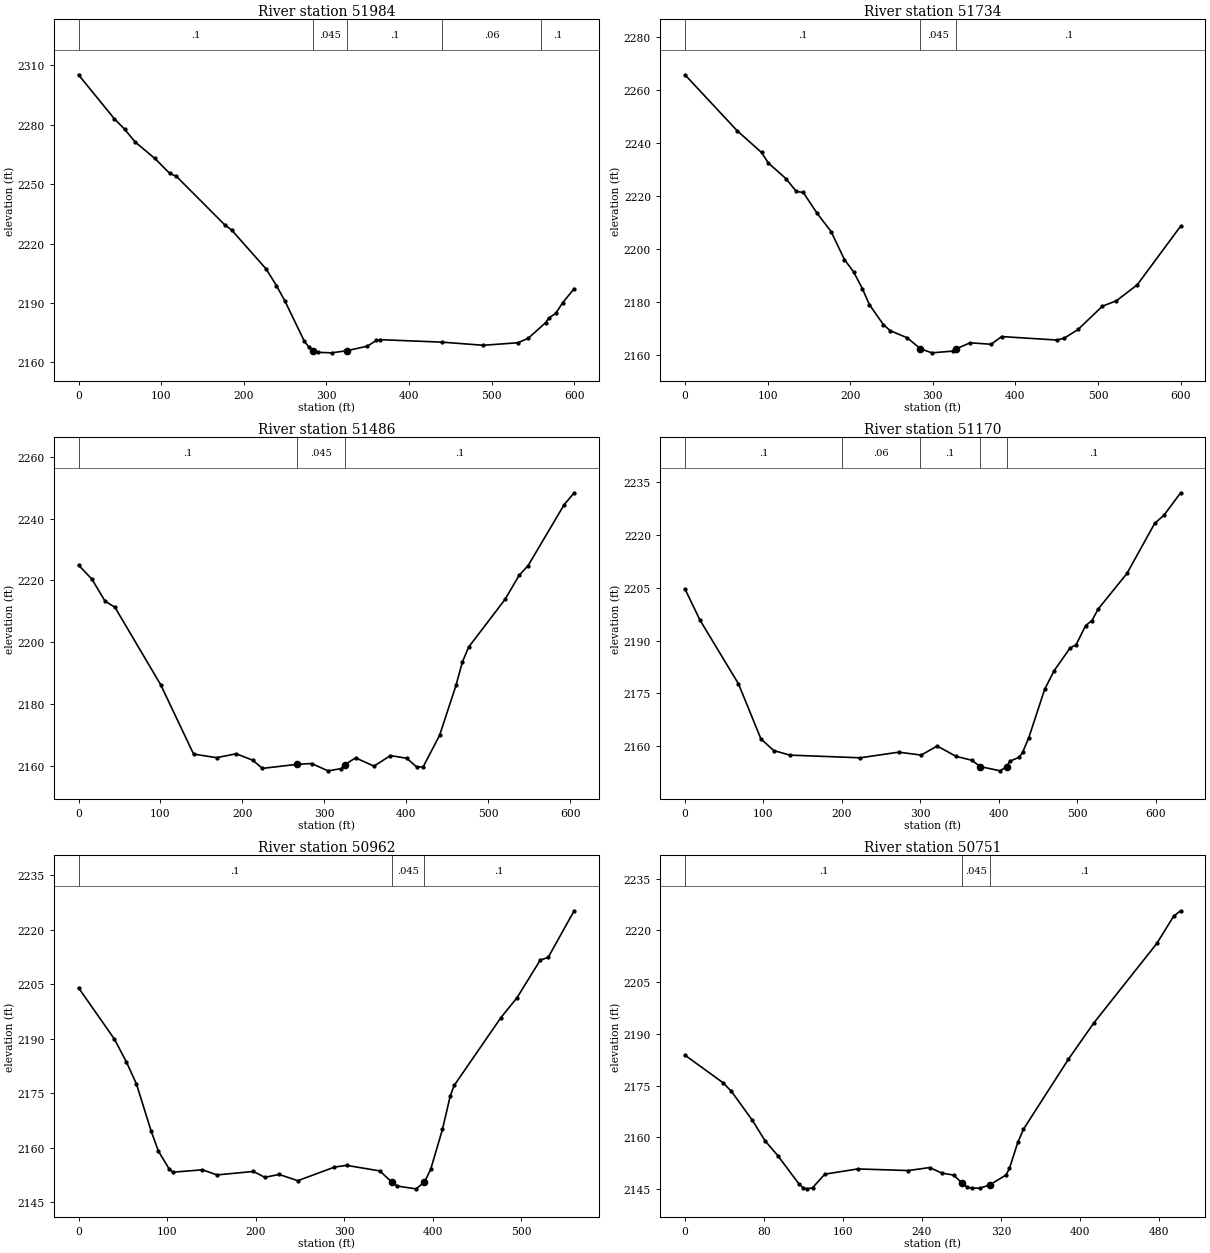
Type RM Length L Ch R = 1 ,51984   ,248.8,250,246.7
XS GIS Cut Line= 2
2211730.59117143 660258.561662562212305.44606355660086.684226563
#Sta/Elev= 30
       0 2305.28    43.4 2283.05    55.9 2277.75    68.5 2271.35    92.4 2263.02
   110.2 2255.54   118.6 2253.94     177  2229.5   185.4 2226.88   227.1 2207.21
   239.6 2198.83   249.9 2190.98     273 2171.03   278.8 2167.77   283.8 2165.94
   289.7 2165.11   306.4 2164.85     3252165.938   349.5 2168.21   360.7 2171.15
   364.9 2171.51     440 2170.25   490.1 2168.67   531.9 2169.94   544.4 2172.18
   565.3 2180.04   569.4 2182.46   577.8 2184.81   586.1 2190.19     600 2197.26
#Mann= 5 ,-1,0
       0      .1       0   283.8    .045       0     325      .1       0
     440     .06       0     560      .1       0
Bank Sta=283.8,325
XS Rating Curve= 0 ,0
Exp/Cntr(USF)=0,0
Exp/Cntr=0.3,0.1

Type RM Length L Ch R = 1 ,51734   ,233.5,247.8,253.8
XS GIS Cut Line= 2
2211816.09334338660496.8705225552212386.10652926660309.560704553
#Sta/Elev= 30
       0 2265.86    63.2 2244.75    92.7 2236.55   101.1 2232.52   122.2  2226.7
   134.8 2221.85   143.2 2221.47   160.1 2213.55   176.9 2206.71   193.1 2196.13
     204 2191.59   214.8 2185.15   223.2 2179.19   240.1 2171.67   248.5 2169.34
   269.2 2166.64   285.12162.491     299 2160.99   324.3 2161.65   328.42162.508
   345.2 2164.78   370.6 2164.22   383.3 2167.13   450.6 2165.81   459.3 2166.57
   475.9 2169.81   505.3 2178.59   522.2 2180.62   547.4 2186.62     600 2208.77
#Mann= 3 ,-1,0
       0      .1       0   285.1    .045       0   328.4      .1       0
Bank Sta=285.1,328.4
XS Rating Curve= 0 ,0
Exp/Cntr(USF)=0,0
Exp/Cntr=0.3,0.1

Type RM Length L Ch R = 1 ,51486   ,317,316.2,310.2
XS GIS Cut Line= 3
 2211895.8467172660618.5810670812212010.24374923660623.124252538
2212500.37742075660631.335645074
#Sta/Elev= 30
       0 2224.96    16.3 2220.43    32.4 2213.27    44.4 2211.31   100.4 2186.11
   140.4  2163.7   168.4 2162.54   192.4 2163.79   212.4 2161.74   224.4 2159.07
   266.62160.372   284.4 2160.64   304.4 2158.27   320.4 2158.99     3252160.308
   338.1 2162.47   360.5 2159.79   380.5 2163.21   400.5 2162.35   412.5 2159.53
   420.5 2159.56   440.5 2169.78   460.5 2185.94   468.3 2193.53   475.9 2198.36
   520.5  2213.9   537.5 2221.64   548.5  2224.8   592.5 2244.55   604.7 2248.41
#Mann= 3 ,-1,0
       0      .1       0   266.6    .045       0     325      .1       0
Bank Sta=266.6,325
XS Rating Curve= 0 ,0
Exp/Cntr(USF)=0,0
Exp/Cntr=0.3,0.1

Type RM Length L Ch R = 1 ,51170   ,193.1,208,213.5
XS GIS Cut Line= 4
2211849.36970376660856.0903746382212157.60629908660919.805370242
 2212344.6881609660897.2109424862212473.20083043 660895.88803834
#Sta/Elev= 30
       0 2204.69    19.2  2195.8    68.2  2177.7    96.8 2162.04   113.1 2158.74
   133.6 2157.44   223.4 2156.68   272.4 2158.28     301 2157.45   321.4 2160.03
   345.5 2157.09   365.7 2155.97   376.22154.172   401.8 2152.97   409.92154.181
     414  2155.7   426.1 2156.85   430.2 2158.21   438.2  2162.4   458.4 2176.15
   470.4 2181.41   490.6 2187.85   498.6 2188.88   510.6 2194.26   518.7 2195.71
   526.7 2199.01   563.3  2209.1   598.7 2223.36   610.7 2225.73   631.7 2232.04
#Mann= 5 ,-1,0
       0      .1       0     200     .06       0     300      .1       0
   376.2    .045       0   409.9      .1       0
Bank Sta=376.2,409.9
XS Rating Curve= 0 ,0
Exp/Cntr(USF)=0,0
Exp/Cntr=0.3,0.1

Type RM Length L Ch R = 1 ,50962   ,210,210.8,208.9
XS GIS Cut Line= 3
2211829.10671656660993.7963562242212134.28441409661076.643460384
2212354.80602899 661180.57782806
#Sta/Elev= 30
       0 2204.03    40.5 2189.93    54.2 2183.56    65.4  2177.6    81.9 2164.72
    90.2  2159.1   102.7 2154.06   106.8 2153.28     140 2153.93   156.5 2152.52
   197.6 2153.48   210.4 2151.86   226.7 2152.65   247.7 2150.93   289.2 2154.68
     303 2155.15   340.4 2153.62   354.12150.495   360.1 2149.45   381.2 2148.69
   390.8 2150.51   397.9 2154.05   411.2 2165.08     420 2174.24   424.4 2177.14
   477.3 2195.84   495.4 2201.29   521.7 2211.66   530.6 2212.39     560 2225.23
#Mann= 3 ,-1,0
       0      .1       0   354.1    .045       0   390.8      .1       0
Bank Sta=354.1,390.8
XS Rating Curve= 0 ,0
Exp/Cntr(USF)=0,0
Exp/Cntr=0.3,0.1

Type RM Length L Ch R = 1 ,50751   ,263.3,268.3,269.7
XS GIS Cut Line= 2
2211808.16166896 661179.142909482212278.70165655661353.956136473
#Sta/Elev= 30
       0 2183.82    38.4 2175.86      47 2173.35    68.3 2164.92    81.1    2159
    93.9 2154.74   115.2 2146.59   119.5 2145.45   123.8 2145.08   129.2 2145.39
   141.6 2149.33     175 2150.85   226.2 2150.38   247.8 2151.25   260.3 2149.63
   272.3 2149.06   280.52146.747   285.9 2145.56   290.2 2145.34   298.7 2145.25
   308.9 2146.26   325.2  2149.1   328.6 2150.99   337.1 2158.53   342.8 2162.35
   388.3 2182.62   413.9 2193.09   477.9  2216.2     495 2224.12     502 2225.66
#Mann= 3 ,-1,0
       0      .1       0   280.5    .045       0   308.9      .1       0
Bank Sta=280.5,308.9
XS Rating Curve= 0 ,0
Exp/Cntr(USF)=0,0
Exp/Cntr=0.3,0.1

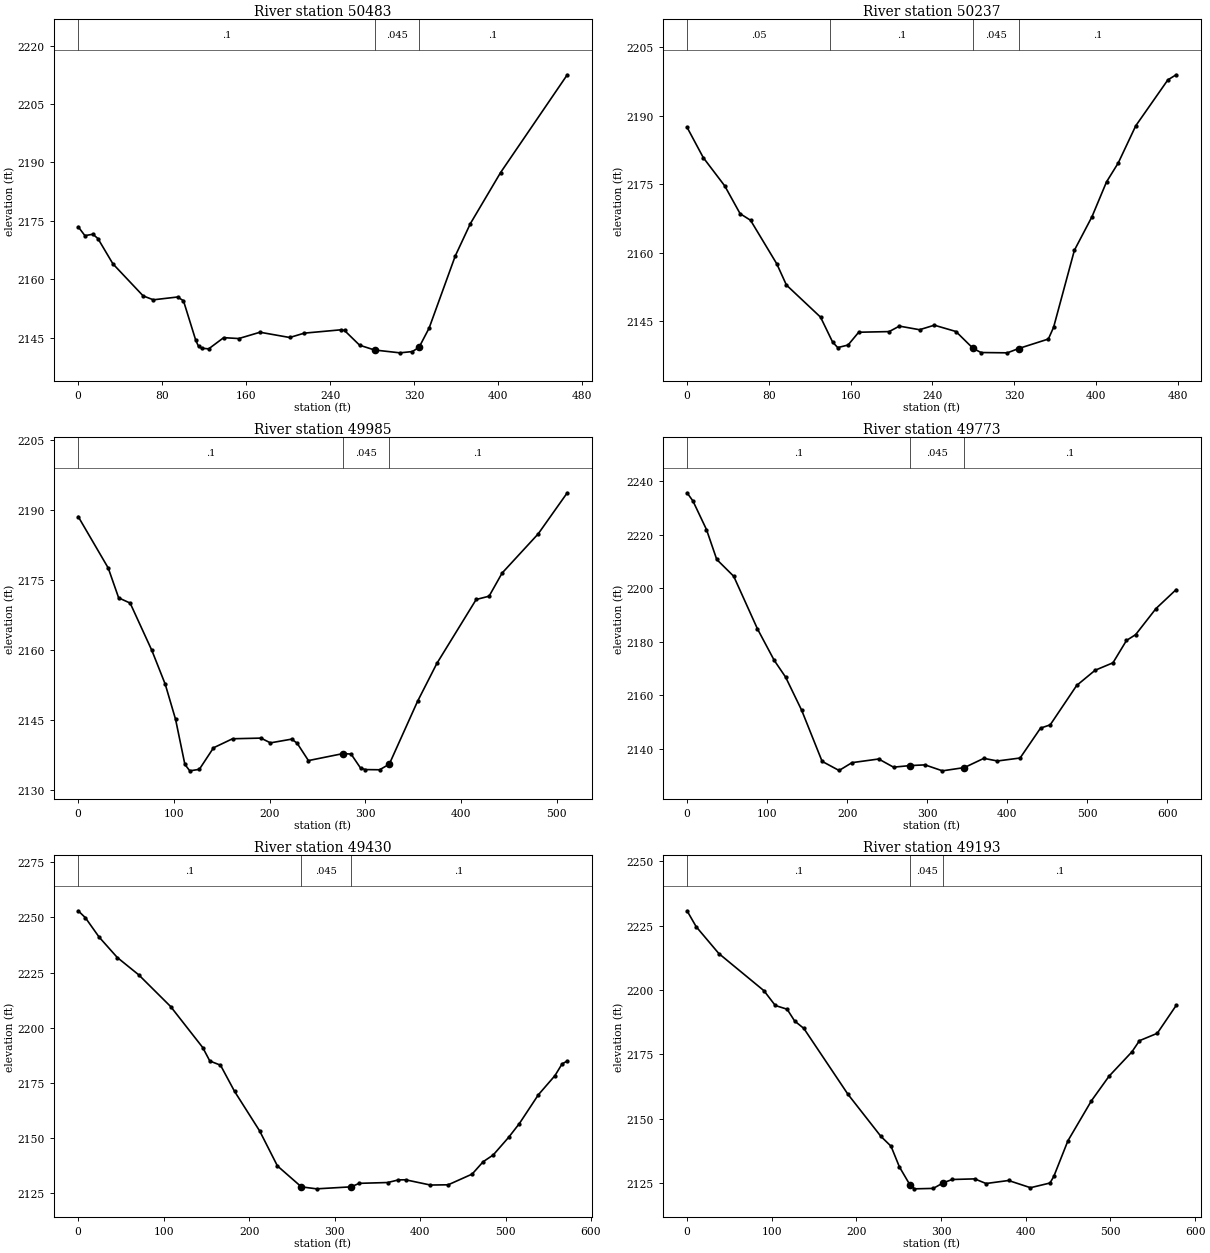
Type RM Length L Ch R = 1 ,50483   ,242.7,245.9,244.5
XS GIS Cut Line= 2
2211696.52701292661337.6565536872212085.20179739661594.633234702
#Sta/Elev= 30
       0 2173.49     6.4 2171.21      14 2171.57    18.8 2170.46    33.1 2163.96
    61.9 2155.73    71.6 2154.73    94.7 2155.45   100.3 2154.48     112 2144.33
   114.7 2142.74   117.8  2142.3   124.3 2142.13   138.6 2145.01     153 2144.78
   173.2  2146.4   201.5 2145.05   215.4 2146.17   250.5 2147.03   253.7 2146.85
   268.1 2143.07   282.3 2141.84   306.5 2141.11   318.3 2141.44   324.7 2142.52
   334.3 2147.47   359.2 2165.99   373.6  2174.3   402.4 2187.42   465.9 2212.52
#Mann= 3 ,-1,0
       0      .1       0   282.3    .045       0   324.7      .1       0
Bank Sta=282.3,324.7
XS Rating Curve= 0 ,0
Exp/Cntr(USF)=0,0
Exp/Cntr=0.3,0.1

Type RM Length L Ch R = 1 ,50237   ,251.4,251.9,251.3
XS GIS Cut Line= 2
2211542.82877494661495.5341298612211923.64540576661785.069444394
#Sta/Elev= 30
       0 2187.47    15.9 2180.82    36.9 2174.63    51.9 2168.56    62.1 2167.12
    87.8 2157.57    97.2 2152.94   130.6 2145.91   142.4 2140.45   147.4 2139.25
   157.5 2139.81   167.9 2142.61   197.7 2142.75   207.7 2143.95   227.4 2143.16
   241.9 2144.15     263 2142.77   279.9 2139.05   287.6 2138.17   313.3  2138.1
   324.42139.047   353.4 2141.12   358.5 2143.66   378.9 2160.56   396.1  2167.9
   410.3 2175.51   421.8 2179.67   438.9 2187.79   470.3 2197.84   478.4 2198.96
#Mann= 4 ,-1,0
       0     .05       0     140      .1       0   279.9    .045       0
   324.4      .1       0
Bank Sta=279.9,324.4
XS Rating Curve= 0 ,0
Exp/Cntr(USF)=0,0
Exp/Cntr=0.3,0.1

Type RM Length L Ch R = 1 ,49985   ,207.2,212.2,215
XS GIS Cut Line= 2
 2211414.0756494 661715.428729622211826.38660526662017.409880745
#Sta/Elev= 30
       0 2188.66    31.4 2177.62    42.3 2171.22    54.3  2170.1      77 2159.94
      91 2152.68   101.8 2145.14   111.5  2135.5   116.6 2134.12   126.6 2134.44
   141.4 2139.06   161.3    2141     191 2141.14   200.9 2140.12   223.1 2140.92
   228.8 2140.05   240.6 2136.32   276.92137.826   285.2 2137.71   295.1 2134.71
   300.1 2134.39     315 2134.35   325.12135.549   354.6 2149.01   374.8 2157.15
   415.9 2170.87   429.4 2171.58     443 2176.54   480.7 2184.94   511.1 2193.76
#Mann= 3 ,-1,0
       0      .1       0   276.9    .045       0   325.1      .1       0
Bank Sta=276.9,325.1
XS Rating Curve= 0 ,0
Exp/Cntr(USF)=0,0
Exp/Cntr=0.3,0.1

Type RM Length L Ch R = 1 ,49773   ,356.3,342.5,325
XS GIS Cut Line= 3
  2211237.241881661916.9729601182211465.29357525661998.045658284
2211728.34003212662256.598346355
#Sta/Elev= 30
       0 2235.75     7.4 2232.66    24.3 2221.98    37.1  2210.8    58.3 2204.51
      88  2184.8   108.9 2173.05   123.1 2166.79   143.2 2154.36   168.7 2135.27
   189.9 2131.85     206 2134.78   239.4 2136.15   257.9 2133.09   278.72133.692
   297.2 2133.95     319 2131.72   346.42132.942   370.7 2136.39   387.7 2135.41
     416 2136.52   441.5 2147.69   453.6 2148.92   486.7 2163.67   509.7 2169.35
     532 2172.14   548.9  2180.5   560.3 2182.67   585.7 2192.42   610.9 2199.52
#Mann= 3 ,-1,0
       0      .1       0   278.7    .045       0   346.4      .1       0
Bank Sta=278.7,346.4
XS Rating Curve= 0 ,0
Exp/Cntr(USF)=0,0
Exp/Cntr=0.3,0.1

Type RM Length L Ch R = 1 ,49430   ,234.1,237.1,242.1
XS GIS Cut Line= 2
2211068.16060638662242.8272350052211618.03899145 662401.12915277
#Sta/Elev= 30
       0    2253     8.4 2249.87    24.5 2241.08    45.8 2231.83    70.8 2224.01
   108.2 2209.63   145.7 2191.09     154 2184.99   166.5 2183.09   182.9 2171.27
   212.3 2153.33   233.1 2137.48   261.1 2128.01   278.9 2127.11   319.32128.014
   328.8  2129.6   362.1 2129.97   374.6 2131.15     383 2131.21   412.1 2128.83
   432.9 2128.94   460.9 2133.79   473.8 2139.39   485.6 2142.46   503.7 2150.47
   516.2 2156.69   538.4 2169.71   557.8 2178.37   566.1 2183.66   572.2 2184.99
#Mann= 3 ,-1,0
       0      .1       0   261.1    .045       0   319.3      .1       0
Bank Sta=261.1,319.3
XS Rating Curve= 0 ,0
Exp/Cntr(USF)=0,0
Exp/Cntr=0.3,0.1

Type RM Length L Ch R = 1 ,49193   ,208.9,210.7,213.3
XS GIS Cut Line= 2
2211010.44484591662421.0448717632211530.23881734662672.876903662
#Sta/Elev= 30
       0 2230.78    10.8 2224.59    37.5 2214.18    90.8 2199.73   104.2 2193.99
   118.2 2192.53   127.1 2187.94   137.9 2185.09     190  2159.5   228.9 2143.15
   240.9 2139.31   250.8 2131.27   263.32124.253   268.6 2122.75   290.8 2122.92
   302.62125.096   313.1 2126.38   339.7 2126.62   353.1 2124.82   379.7 2125.99
   405.6 2123.19   428.6 2125.01   433.1 2127.55   449.8 2141.42   477.6 2156.98
   498.4 2166.52   525.4 2175.98   534.3 2180.31   555.3 2183.17   577.6 2193.98
#Mann= 3 ,-1,0
       0      .1       0   263.3    .045       0   302.6      .1       0
Bank Sta=263.3,302.6
XS Rating Curve= 0 ,0
Exp/Cntr(USF)=0,0
Exp/Cntr=0.3,0.1

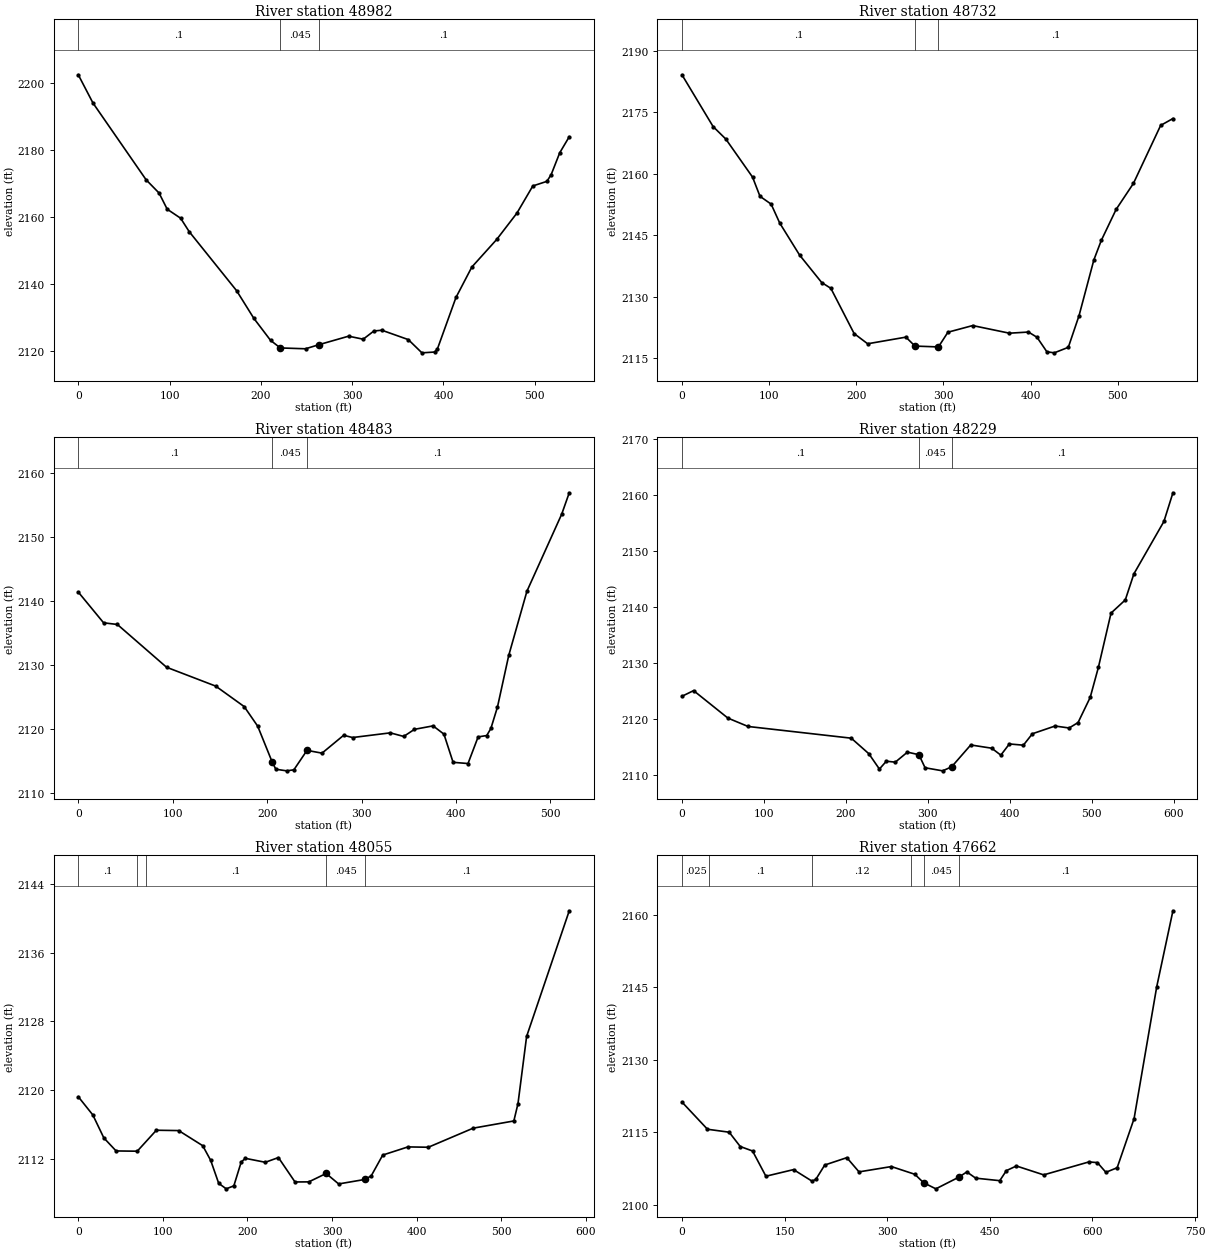
Type RM Length L Ch R = 1 ,48982   ,247.4,250,252.4
XS GIS Cut Line= 2
2210953.20664363662597.9059627672211408.94740415662883.395716755
#Sta/Elev= 30
       0 2202.37    16.1 2193.94    74.3 2171.03    88.5 2167.07    97.4 2162.25
   112.1 2159.56   121.5 2155.55   173.4 2137.94   192.3 2129.68   210.6 2123.11
   221.32120.843   248.9 2120.59   263.72121.825   296.1 2124.35   312.1 2123.45
   323.8  2125.9   332.5 2126.13   361.5 2123.33   376.4 2119.38   390.4 2119.62
   393.4 2120.55   413.7  2135.9   431.1 2144.99   458.3 2153.21   480.5 2161.09
   497.9 2169.19   513.3 2170.56     518 2172.58   527.4  2179.1   537.8 2183.88
#Mann= 3 ,-1,0
       0      .1       0   221.3    .045       0   263.7      .1       0
Bank Sta=221.3,263.7
XS Rating Curve= 0 ,0
Exp/Cntr(USF)=0,0
Exp/Cntr=0.3,0.1

Type RM Length L Ch R = 1 ,48732   ,248.6,249,240.3
XS GIS Cut Line= 3
2210791.99492514662743.7041634982210843.25161036662782.368387742
2211221.90292775663107.329375973
#Sta/Elev= 30
       0  2184.1    35.7 2171.48    50.3 2168.43      81 2159.14    89.5 2154.47
   102.3 2152.56   112.2 2147.93   134.9 2140.15   160.3 2133.44   170.8 2132.03
   197.5    2121     213 2118.51   256.9 2120.13   267.32117.948   294.22117.744
   305.1 2121.33   333.5 2122.95   375.6 2121.09   397.5 2121.37   407.3 2120.09
   418.6 2116.56   427.1  2116.3   443.2 2117.65   455.5 2125.37   472.5 2138.96
     481  2143.7     498 2151.26   517.9 2157.62   549.1 2171.75   563.2 2173.43
#Mann= 3 ,-1,0
       0      .1       0   267.3    .045       0   294.2      .1       0
Bank Sta=267.3,294.2
XS Rating Curve= 0 ,0
Exp/Cntr(USF)=0,0
Exp/Cntr=0.3,0.1

Type RM Length L Ch R = 1 ,48483   ,255.7,254.1,247.8
XS GIS Cut Line= 3
2210641.40438241662946.4311235482210922.78610822 663131.42924259
2211060.89593066663251.644439752
#Sta/Elev= 30
       0  2141.4    26.8  2136.6    41.4 2136.34    93.5 2129.66   145.5 2126.72
   175.7 2123.52     190 2120.46   205.42114.838   209.2 2113.74   220.6 2113.49
   228.3 2113.65   242.22116.687   258.1 2116.25     281 2119.04   290.5 2118.69
   330.4 2119.42   344.6 2118.86     356 2119.97   375.7 2120.51   387.2 2119.22
   396.9 2114.82   412.7 2114.63   423.4 2118.79   432.5    2119   436.9  2120.1
   443.9 2123.46   455.8  2131.5   475.1 2141.54   511.9 2153.56   519.9  2156.9
#Mann= 3 ,-1,0
       0      .1       0   205.4    .045       0   242.2      .1       0
Bank Sta=205.4,242.2
XS Rating Curve= 0 ,0
Exp/Cntr(USF)=0,0
Exp/Cntr=0.3,0.1

Type RM Length L Ch R = 1 ,48229   ,166.3,174.1,174.5
XS GIS Cut Line= 3
2210517.81249288663103.7267542982210628.34729779663257.685115594
2211010.43677555663404.456617257
#Sta/Elev= 30
       0 2124.11    14.2 2125.12      56 2120.22    80.6 2118.72   206.5 2116.63
   227.9 2113.86   240.8 2111.12   249.3 2112.52   260.2 2112.35     275 2114.14
     2892113.677   296.5 2111.35   317.9  2110.8   328.92111.516   352.2 2115.42
   377.8 2114.84   388.9  2113.6   399.3  2115.6   416.4 2115.38   427.4 2117.42
     455  2118.8   472.2 2118.45   483.1 2119.42   497.9 2123.91   507.9 2129.28
   523.3 2138.96   540.7 2141.31   551.2 2145.97   587.8 2155.32   598.8 2160.44
#Mann= 3 ,-1,0
       0      .1       0     289    .045       0   328.9      .1       0
Bank Sta=289,328.9
XS Rating Curve= 0 ,0
Exp/Cntr(USF)=0,0
Exp/Cntr=0.3,0.1

Type RM Length L Ch R = 1 ,48055   ,384.7,393.1,388.9
XS GIS Cut Line= 3
 2210431.0443711663192.7008338182210542.62179212663370.108933232
2210850.51851038663576.736186121
#Sta/Elev= 30
       0 2119.22    17.2  2117.1    30.2 2114.43    44.7 2112.91    69.7 2112.88
    92.3 2115.32   118.7 2115.28   147.1 2113.52   156.5 2111.82     166 2109.14
   174.9  2108.5   183.9 2108.85   192.6 2111.62   197.5 2112.05   221.1 2111.59
   236.6 2112.14   256.2  2109.3   272.5 2109.31     2932110.287   307.8 2109.07
   338.92109.595   346.3 2110.01   359.9 2112.43   389.7 2113.38   413.8 2113.34
   466.8 2115.56   514.9  2116.4   519.8 2118.42     530 2126.24   580.4 2140.86
#Mann= 5 ,-1,0
       0      .1       0      70     .06       0      80      .1       0
     293    .045       0   338.9      .1       0
Bank Sta=293,338.9
XS Rating Curve= 0 ,0
Exp/Cntr(USF)=0,0
Exp/Cntr=0.3,0.1

Type RM Length L Ch R = 1 ,47662   ,196.6,187.5,179.7
XS GIS Cut Line= 4
2210151.23966688663373.8562524722210348.58591437663593.640237715
2210491.15706345663738.6908850352210703.12258425663792.885224078
#Sta/Elev= 30
       0 2121.29    37.3 2115.66      69 2115.05    85.2 2112.09   103.2 2111.16
   122.7 2105.94   163.1 2107.31     190 2104.93   195.6 2105.27   208.7 2108.26
     241 2109.78   258.8 2106.84   306.1 2107.94   340.4 2106.34   353.1  2104.6
   371.1 2103.33   404.32105.718   416.4 2106.83   429.3 2105.54   464.5 2105.02
   474.2  2107.1   488.8 2108.06   528.7 2106.22   594.8  2108.9   607.2 2108.76
   619.6 2106.75   636.1  2107.7   660.8 2117.85   693.9 2145.14   717.6 2160.87
#Mann= 6 ,-1,0
       0    .025       0      40      .1       0     190     .12       0
  335.38      .1       0   353.1    .045       0   404.3      .1       0
Bank Sta=353.1,404.3
XS Rating Curve= 0 ,0
Exp/Cntr(USF)=0,0
Exp/Cntr=0.3,0.1

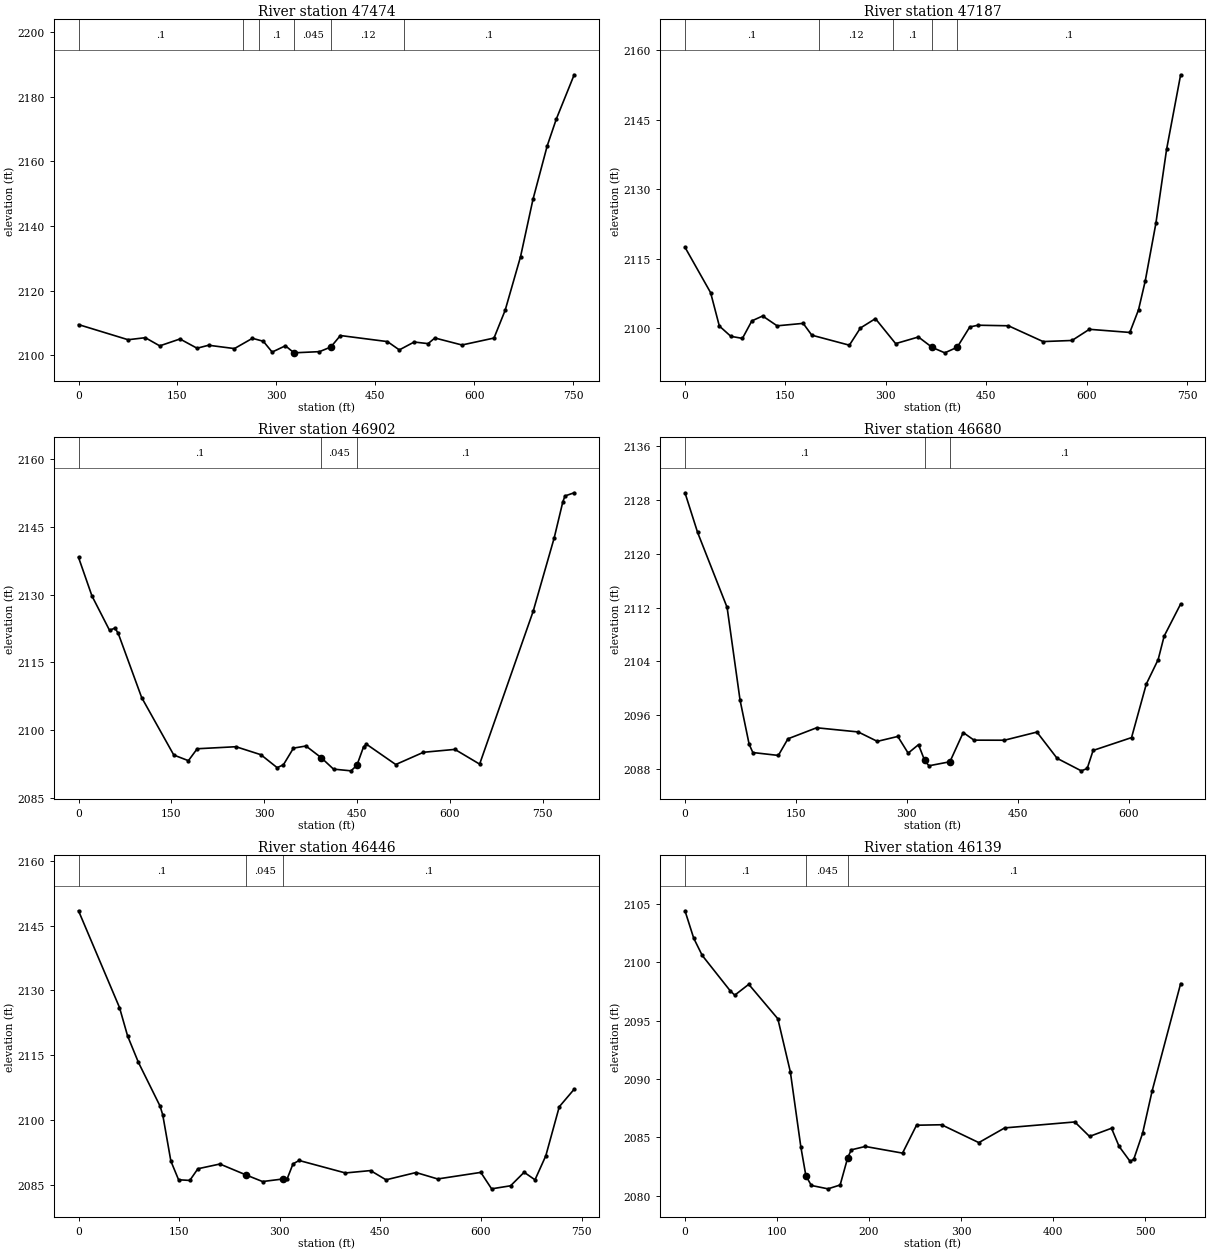
Type RM Length L Ch R = 1 ,47474   ,281.3,287,280.8
XS GIS Cut Line= 3
2209951.21373224663632.1506583122210202.62137487663741.246533089
2210628.68319533663957.466905845
#Sta/Elev= 30
       0 2109.46    75.2 2104.77   101.3  2105.4   123.2 2102.87   153.9    2105
   179.8 2102.14   197.3 2103.06   236.5 2102.03   263.8 2105.21   280.3 2104.29
   293.7 2100.95   313.8 2102.89   326.9 2100.71   327.62100.722   365.5 2101.08
   382.72102.511   397.2 2106.07   468.6 2104.19   486.6 2101.62   509.1 2104.06
   530.2 2103.56   540.5 2105.31   581.6 2103.14   630.2 2105.29   647.1 2113.87
   670.5 2130.52   689.3 2148.21   710.9 2164.79   724.7  2173.1   751.8 2186.81
#Mann= 6 ,-1,0
       0      .1       0     250     .12       0  274.06      .1       0
   327.6    .045       0   382.7     .12       0  494.06      .1       0
Bank Sta=327.6,382.7
XS Rating Curve= 0 ,0
Exp/Cntr(USF)=0,0
Exp/Cntr=0.3,0.1

Type RM Length L Ch R = 1 ,47187   ,281.1,284.9,273.2
XS GIS Cut Line= 2
 2209792.6732906663878.5970824852210478.52977758664157.091460579
#Sta/Elev= 30
       0 2117.52    38.3 2107.72    51.3 2100.53    68.5  2098.3    85.8 2097.86
    99.9 2101.64     116 2102.69   137.6 2100.57   176.5  2101.1   189.4 2098.55
   245.5 2096.39     262  2100.1   284.4 2102.12   314.6 2096.73   348.6 2098.16
   369.22095.908     388 2094.74   406.52095.943   425.3 2100.32   437.6  2100.7
     483 2100.58   534.8 2097.17     578 2097.41   603.9 2099.82   664.3 2099.14
   677.3 2104.02   687.3 2110.22   703.2 2122.65   719.2 2138.62   740.2 2154.74
#Mann= 5 ,-1,0
       0      .1       0     200     .12       0     310      .1       0
   369.2    .045       0   406.5      .1       0
Bank Sta=369.2,406.5
XS Rating Curve= 0 ,0
Exp/Cntr(USF)=0,0
Exp/Cntr=0.3,0.1

Type RM Length L Ch R = 1 ,46902   ,210.3,222.4,228.4
XS GIS Cut Line= 4
2209721.75137058664130.4646182392209918.65663552664253.899027893
2210145.80452411664288.3790189172210457.89640928 664419.46313303
#Sta/Elev= 30
       0 2138.27    21.7 2129.73    50.1 2122.12    58.9 2122.62    64.2 2121.42
     102 2107.23   153.9  2094.5   177.5 2093.25   191.7 2095.89   254.3 2096.34
   294.6 2094.57   320.9  2091.7     331 2092.35   347.2 2096.03   367.4  2096.5
   391.92093.925   411.9 2091.38   440.2    2091   449.7 2092.24   460.5 2096.35
   465.1  2096.9   512.4  2092.4   557.2 2095.11   607.9 2095.75   647.9 2092.49
   734.4 2126.34   768.4 2142.61   782.3 2150.57   785.8 2151.87   800.6 2152.57
#Mann= 3 ,-1,0
       0      .1       0   391.9    .045       0   449.7      .1       0
Bank Sta=391.9,449.7
XS Rating Curve= 0 ,0
Exp/Cntr(USF)=0,0
Exp/Cntr=0.3,0.1

Type RM Length L Ch R = 1 ,46680   ,236.3,233.8,233.1
XS GIS Cut Line= 4
2209723.16133394664347.8825104512209967.37368779 664447.20175977
2210108.36291698664532.1568081312210350.57518252664537.579470793
#Sta/Elev= 30
       0 2129.05    17.1 2123.15      57 2112.01    74.5 2098.24    86.8 2091.68
    91.8 2090.45   126.3 2090.02   139.3 2092.49   178.1 2094.13   234.3 2093.51
   260.2 2092.11   287.9 2092.84   301.9 2090.36   315.9 2091.62   324.22089.279
     330 2088.48   358.4 2089.08   376.4 2093.42     391 2092.29   432.1 2092.28
   476.1 2093.49   503.4 2089.59   536.1 2087.73   544.1 2088.08   552.1 2090.76
   604.1 2092.67   624.1 2100.64   640.1 2104.26   648.2 2107.75   670.5 2112.52
#Mann= 3 ,-1,0
       0      .1       0   324.2    .045       0   358.4      .1       0
Bank Sta=324.2,358.4
XS Rating Curve= 0 ,0
Exp/Cntr(USF)=0,0
Exp/Cntr=0.3,0.1

Type RM Length L Ch R = 1 ,46446   ,340.8,307.2,287.3
XS GIS Cut Line= 4
2209639.55675106664675.0598929442209843.35477823664649.661772751
2209987.32647189664726.9347156752210354.15586461664777.167558209
#Sta/Elev= 30
       0 2148.46    61.1 2126.05    73.2 2119.45    89.3 2113.34   121.6  2103.2
   125.6 2101.17   137.7 2090.47   149.2 2086.14   165.9 2085.99     178 2088.69
   210.8 2089.79   249.72087.265   274.4 2085.73   304.92086.326   310.7 2086.21
   319.8 2089.82   328.9 2090.61   397.9 2087.72   435.4 2088.27   458.5 2086.13
   503.2 2087.82   535.5 2086.33   599.8 2087.85   615.9 2084.04   644.2 2084.75
   664.4 2087.88   680.6 2086.13   696.7 2091.69   716.8 2103.06     739 2107.12
#Mann= 3 ,-1,0
       0      .1       0   249.7    .045       0   304.9      .1       0
Bank Sta=249.7,304.9
XS Rating Curve= 0 ,0
Exp/Cntr(USF)=0,0
Exp/Cntr=0.3,0.1

Type RM Length L Ch R = 1 ,46139   ,226.2,224.9,223.3
XS GIS Cut Line= 3
2209841.41988387664999.0332277462210053.57071517664834.319849408
2210322.95227986664815.897692743
#Sta/Elev= 30
       0 2104.42     9.5 2102.07    18.7  2100.6    49.1 2097.57    54.1 2097.19
    69.3 2098.12   100.9 2095.17   114.5 2090.62   125.9 2084.19   131.42081.715
   137.3 2080.89   155.4  2080.6   168.6 2080.93   176.82083.259   180.7 2083.94
   195.9 2084.23   236.4 2083.66   251.6 2086.05   278.8 2086.09   319.3 2084.56
   347.4 2085.82   423.6 2086.33   439.6 2085.09   463.5 2085.79   471.7 2084.24
   483.7 2082.95   487.7 2083.14   497.3 2085.37   507.7 2089.01   538.6 2098.18
#Mann= 3 ,-1,0
       0      .1       0   131.4    .045       0   176.8      .1       0
Bank Sta=131.4,176.8
XS Rating Curve= 0 ,0
Exp/Cntr(USF)=0,0
Exp/Cntr=0.3,0.1

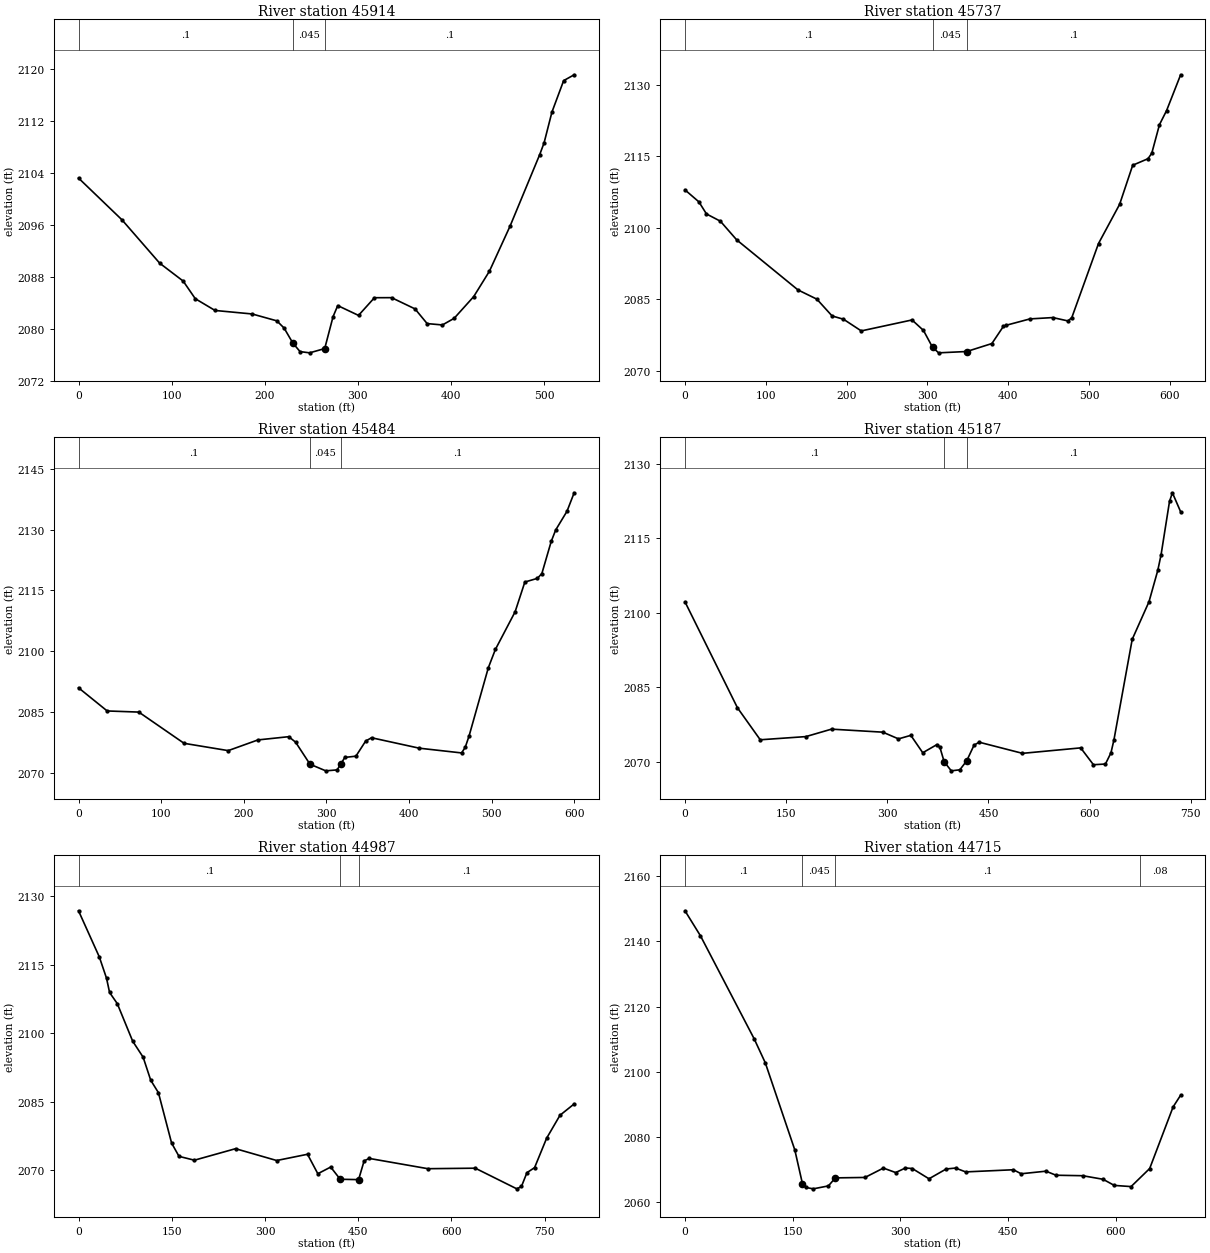
Type RM Length L Ch R = 1 ,45914   ,175.4,177.2,178.7
XS GIS Cut Line= 3
2209942.80495294665189.2399491322210199.83916309664993.210693924
2210398.87693707664929.448266621
#Sta/Elev= 30
       0 2103.15    46.7 2096.72    87.2 2090.05   112.4  2087.3   125.4 2084.59
   146.6 2082.78   186.5 2082.24     213 2081.18   220.8 2080.07   230.12077.781
   237.9 2076.45   248.2 2076.26   264.42076.918   273.4 2081.84   278.4 2083.53
   300.7 2082.02   317.8 2084.74   336.2 2084.75   361.4 2083.02   374.4 2080.76
   390.8 2080.55   403.4 2081.57   424.4 2084.91   441.3 2088.82   463.5 2095.77
   495.3 2106.76     500 2108.57   508.4 2113.29     521 2118.14   532.3 2119.04
#Mann= 3 ,-1,0
       0      .1       0   230.1    .045       0   264.4      .1       0
Bank Sta=230.1,264.4
XS Rating Curve= 0 ,0
Exp/Cntr(USF)=0,0
Exp/Cntr=0.3,0.1

Type RM Length L Ch R = 1 ,45737   ,251.9,253.2,254.2
XS GIS Cut Line= 2
2209953.54789076665362.933967559 2210474.5156572665039.517443258
#Sta/Elev= 30
       0 2107.94    17.2 2105.43    26.6 2102.89    43.8 2101.37      64 2097.45
   139.8 2086.95   163.2 2085.01     182 2081.49   196.1  2080.8   218.1 2078.35
   280.9 2080.65     295 2078.46   306.3 2074.91   313.8 2073.75   348.6 2074.03
   379.7  2075.7   393.9  2079.3   397.7 2079.55   426.8 2080.87   455.1 2081.15
   473.9 2080.44   478.6 2081.16   511.6 2096.69   537.7  2104.9   553.9 2113.11
   572.8 2114.48   577.5 2115.63     587 2121.62   595.8 2124.57   613.2 2132.09
#Mann= 3 ,-1,0
       0      .1       0   306.3    .045       0   348.6      .1       0
Bank Sta=306.3,348.6
XS Rating Curve= 0 ,0
Exp/Cntr(USF)=0,0
Exp/Cntr=0.3,0.1

Type RM Length L Ch R = 1 ,45484   ,292.5,296.3,298
XS GIS Cut Line= 2
2210101.73545633665548.2949600892210627.82247893665259.794622735
#Sta/Elev= 30
       0 2090.98    34.7 2085.26      73 2084.98   127.8 2077.27   181.2 2075.47
   217.2 2078.11   254.5 2078.91   262.8 2077.55   280.22072.117   299.3 2070.48
     313 2070.71   317.52072.129   322.3 2073.79   335.8  2074.1   347.6 2077.83
   354.7 2078.65   412.5 2076.07   463.7  2074.9   468.1 2076.27   472.7 2079.03
   496.1 2095.93   504.6 2100.43   528.5 2109.73   540.3 2117.08   555.5 2117.99
   560.9 2119.18   572.2 2127.09   577.6 2129.92   591.3 2134.54     600 2139.11
#Mann= 3 ,-1,0
       0      .1       0   280.2    .045       0   317.5      .1       0
Bank Sta=280.2,317.5
XS Rating Curve= 0 ,0
Exp/Cntr(USF)=0,0
Exp/Cntr=0.3,0.1

Type RM Length L Ch R = 1 ,45187   ,198.9,200.3,201.1
XS GIS Cut Line= 3
2210130.55692564665785.6020684042210568.37048861665635.803179745
 2210819.3773952665530.387784057
#Sta/Elev= 30
       0 2102.23    77.8 2080.91   111.6 2074.47   179.3 2075.11   217.3 2076.61
   293.4    2076   316.6 2074.65   334.9 2075.36   352.6 2071.86   373.7 2073.51
     378 2072.97   384.3 2070.07   394.9 2068.22   407.6 2068.43   417.82070.245
   428.7  2073.4   436.3 2073.98   500.5 2071.74   586.8 2072.84   605.7 2069.45
   623.5 2069.59   631.7 2071.85   636.1 2074.45   663.2 2094.68   688.1 2102.25
   701.1 2108.55     706  2111.7   718.5 2122.43   722.8 2124.17     735 2120.35
#Mann= 3 ,-1,0
       0      .1       0   384.3    .045       0   417.8      .1       0
Bank Sta=384.3,417.8
XS Rating Curve= 0 ,0
Exp/Cntr(USF)=0,0
Exp/Cntr=0.3,0.1

Type RM Length L Ch R = 1 ,44987   ,290.5,272.5,258.3
XS GIS Cut Line= 3
2210151.83202641665955.8935439112210629.62020217665829.776638572
2210926.51694593665766.961176681
#Sta/Elev= 30
       0 2126.85    33.5 2116.74    45.1 2112.07      50 2108.96    62.4 2106.52
    87.2 2098.29     104 2094.79   116.2 2089.75   128.6 2087.02   149.8 2075.99
   161.7 2073.08   186.5 2072.24   252.7 2074.76   318.9 2072.17   368.5 2073.54
   385.1 2069.28   405.8 2070.74   421.12068.065   450.72067.987   459.6 2072.09
   467.8 2072.63   562.2 2070.38   638.5 2070.49   705.3 2065.97   712.8 2066.49
   721.6 2069.51   733.9 2070.61   753.3 2077.06   774.8 2082.08   797.6 2084.56
#Mann= 3 ,-1,0
       0      .1       0   421.1    .045       0   450.7      .1       0
Bank Sta=421.1,450.7
XS Rating Curve= 0 ,0
Exp/Cntr(USF)=0,0
Exp/Cntr=0.3,0.1

Type RM Length L Ch R = 1 ,44715   ,270.8,270.4,268.8
XS GIS Cut Line= 4
2210487.34719617 666241.250782452210543.58781182666178.782133265
2210681.16277193666008.0686791112211013.16683277665809.833290892
#Sta/Elev= 30
       0 2149.37    21.6 2141.68    96.4  2110.1   111.8 2102.79   152.9 2076.09
   163.52065.771   168.3 2064.59   178.6 2064.17   199.7 2065.07   209.32067.526
   250.6 2067.66   276.2 2070.53   293.3 2069.16   306.8 2070.55   316.4  2070.4
   339.7 2067.25   363.6 2070.25   376.7 2070.54   390.7 2069.36   457.2 2070.02
     468 2068.79   502.5 2069.58   516.5 2068.34   553.7 2068.19     582  2067.1
   597.6 2065.22     621 2064.86   646.9 2070.39   679.5 2089.26     690 2092.86
#Mann= 4 ,-1,0
       0      .1       0   163.5    .045       0   209.3      .1       0
   633.3     .08       0
Bank Sta=163.5,209.3
XS Rating Curve= 0 ,0
Exp/Cntr(USF)=0,0
Exp/Cntr=0.3,0.1