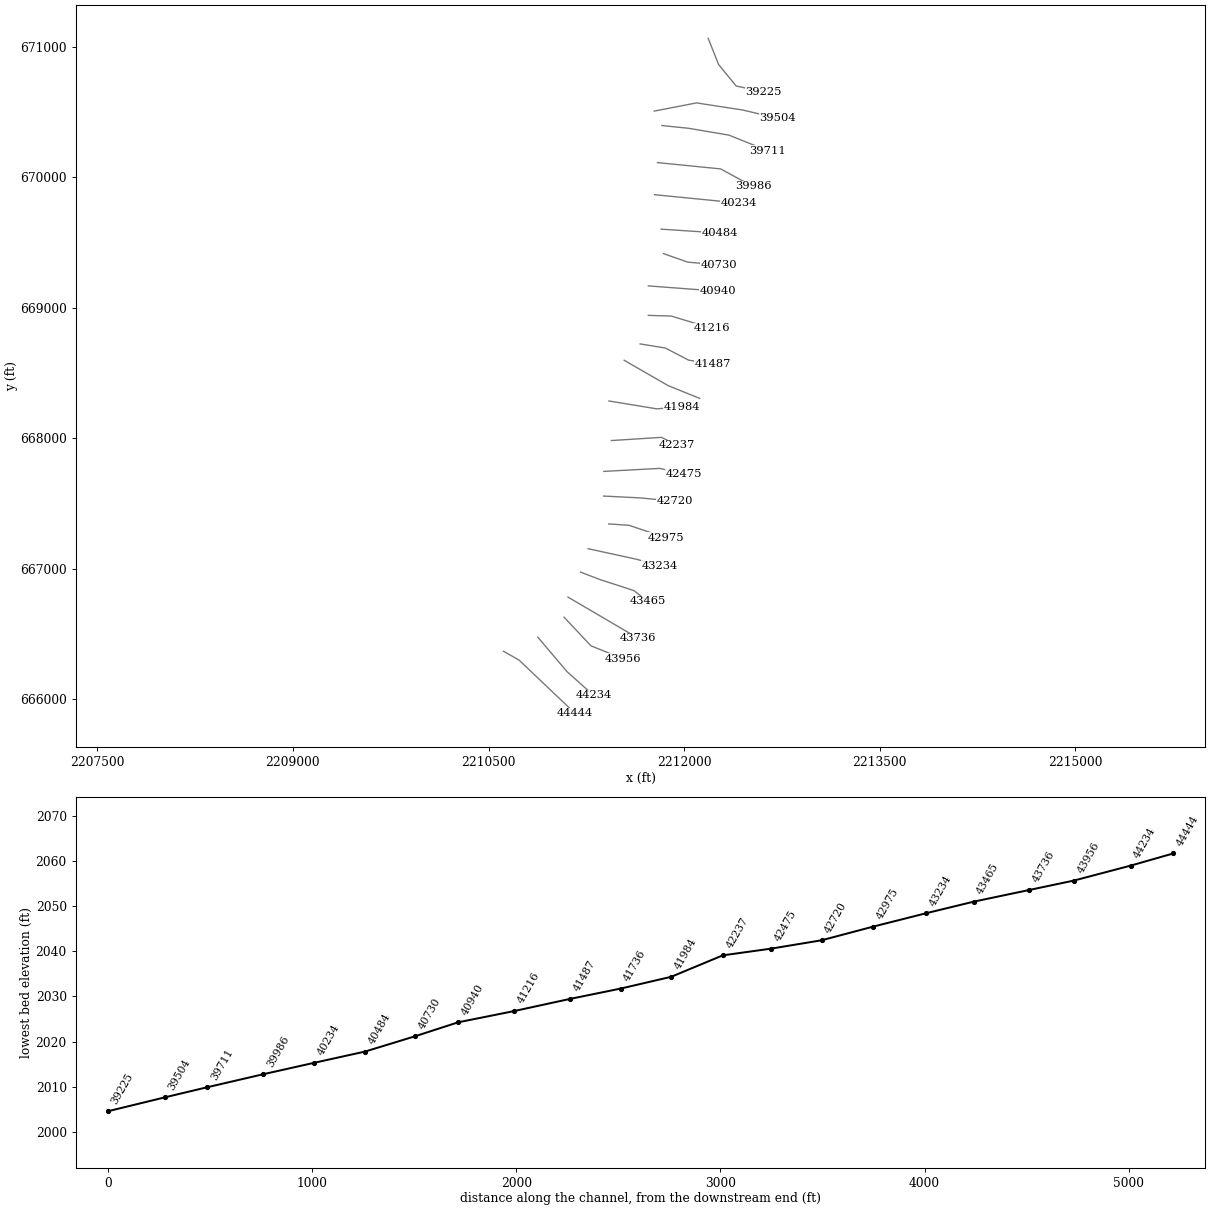
HEC-RAS study RFMIDDLERV.prj: RFMIDDLERV

--- RFMIDDLERV.g01 (geometry) --- (continued)

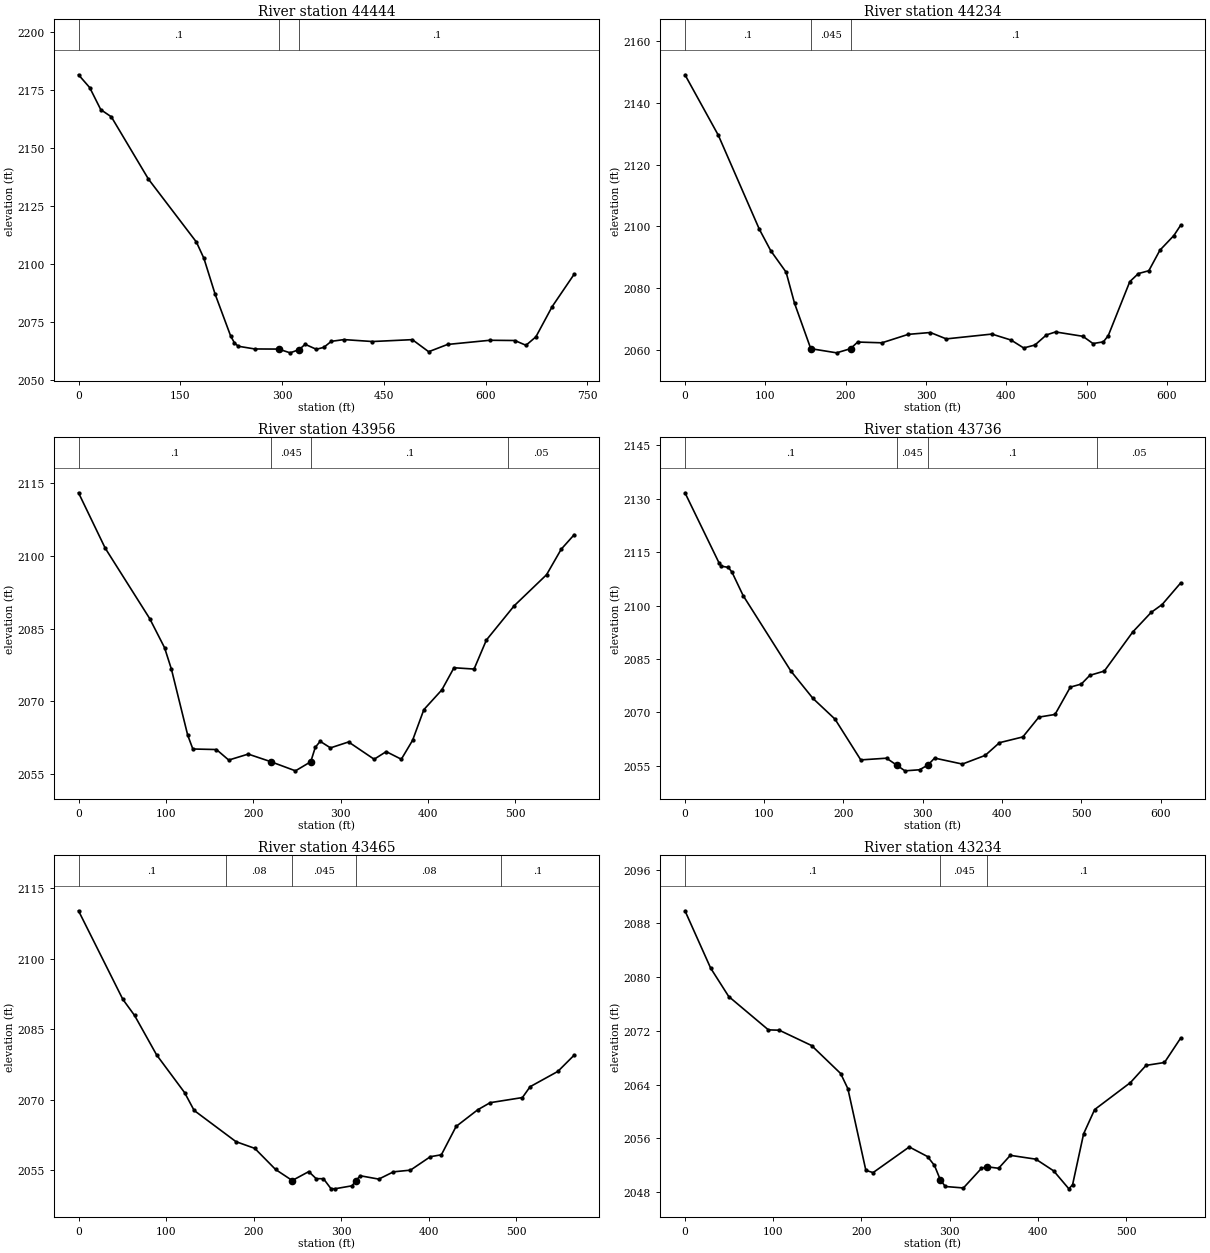
Type RM Length L Ch R = 1 ,44444   ,212.1,209.8,206.9
XS GIS Cut Line= 4
2210614.39832391666365.2938322952210733.21504695666298.140801383
2210922.10446298666118.2891564482211163.66646812665888.914806979
#Sta/Elev= 30
       0 2181.42    16.5  2175.9    32.8 2166.41    48.4 2163.31   103.1 2136.49
   173.7 2109.42   184.8 2102.39   201.3 2086.98   224.1 2069.05   229.8 2065.99
   235.4 2064.56   259.7 2063.39   294.9 2063.34   311.8 2061.72   325.32063.132
   333.9  2065.4   350.4 2063.26   361.5 2064.08   372.5 2066.67   391.1 2067.42
   433.2 2066.59   491.9  2067.4     516  2062.2   543.8 2065.33   606.1 2067.13
   642.9 2067.03   659.4 2064.97     674 2068.61     698 2081.63   730.4 2095.57
#Mann= 3 ,-1,0
       0      .1       0   294.9    .045       0   325.3      .1       0
Bank Sta=294.9,325.3
XS Rating Curve= 0 ,0
Exp/Cntr(USF)=0,0
Exp/Cntr=0.3,0.1

Type RM Length L Ch R = 1 ,44234   ,276.2,278.3,278.2
XS GIS Cut Line= 3
2210877.71703641666473.2656961652211101.80857777666208.723895931
2211303.38570961666028.458363432
#Sta/Elev= 30
       0 2149.12    41.5 2129.53    92.6 2099.05   106.8  2092.1   125.9 2085.15
   136.4 2075.07   156.62060.365   188.8 2059.01   206.1 2060.36     215 2062.51
   245.2 2062.26     278    2065   305.5  2065.6   325.3 2063.53   382.1 2065.09
     406 2063.15   421.7 2060.59   435.7 2061.54     450 2064.82   461.4 2065.78
   495.4 2064.37     508 2062.02   520.9 2062.57     527 2064.59   553.8 2082.08
   564.5  2084.7   577.5 2085.62   591.3 2092.27   608.7 2097.03   617.1 2100.35
#Mann= 3 ,-1,0
       0      .1       0   156.6    .045       0   206.1      .1       0
Bank Sta=156.6,206.1
XS Rating Curve= 0 ,0
Exp/Cntr(USF)=0,0
Exp/Cntr=0.3,0.1

Type RM Length L Ch R = 1 ,43956   ,211.3,220.3,224.6
XS GIS Cut Line= 3
2211078.52884425666626.7053125462211285.16656598666406.948547088
2211531.75266643666307.644642384
#Sta/Elev= 30
       0 2112.98    30.5 2101.59    81.5 2087.06    98.5 2081.07   106.4 2076.62
     125 2063.05   130.9 2060.19   157.9 2060.08     172 2057.91   194.3 2059.14
   219.92057.592   248.4 2055.69   265.92057.562   271.1 2060.54   276.7 2061.77
   288.5 2060.42   309.2 2061.64   338.5 2058.08   352.3 2059.65   369.6 2058.08
   382.5 2061.98   395.4  2068.3     416 2072.37   429.9 2076.93   452.9 2076.66
     467 2082.64   498.9 2089.71   535.9  2096.1   552.7 2101.36   567.5 2104.34
#Mann= 4 ,-1,0
       0      .1       0   219.9    .045       0   265.9      .1       0
  491.65     .05       0
Bank Sta=219.9,265.9
XS Rating Curve= 0 ,0
Exp/Cntr(USF)=0,0
Exp/Cntr=0.3,0.1

Type RM Length L Ch R = 1 ,43736   ,261.9,270.8,275.2
XS GIS Cut Line= 2
 2211108.8283286666780.8443403932211648.29062964 666464.42634253
#Sta/Elev= 30
       0 2131.66    43.1 2111.91      46 2111.06    54.9 2110.69    59.5 2109.29
    73.4 2102.79   133.7 2081.59   161.5 2073.92   189.3 2068.11   221.8 2056.66
   254.3 2057.14     2672055.221   277.5 2053.59     296 2053.89   306.52055.221
     315 2057.17     350 2055.49   378.8 2057.93   396.8 2061.49   426.3 2063.11
   446.5 2068.67   466.9 2069.42   486.2 2077.09   500.1 2077.96   510.8  2080.4
   529.1  2081.6     565 2092.58   588.2 2098.07   602.1 2100.29   625.4 2106.33
#Mann= 4 ,-1,0
       0      .1       0     267    .045       0   306.5      .1       0
     520     .05       0
Bank Sta=267,306.5
XS Rating Curve= 0 ,0
Exp/Cntr(USF)=0,0
Exp/Cntr=0.3,0.1

Type RM Length L Ch R = 1 ,43465   ,232.8,230.6,234.5
XS GIS Cut Line= 4
2211204.94273764666972.601781679 2211352.7552846666915.810707515
2211613.84644977666831.0118675432211718.83792956666749.342682444
#Sta/Elev= 30
       0  2110.2    50.6 2091.35      64 2087.92    89.2 2079.51   121.1  2071.5
     132  2067.7   179.8 2061.05   201.2 2059.63     225 2055.13     2442052.782
   262.9 2054.68   271.3 2053.18   279.7 2053.16   288.1 2051.08   292.3 2051.01
   312.4 2051.66   316.62052.777   321.8 2053.79   342.8 2053.08   359.6 2054.63
     379 2054.99   401.7 2057.85   414.3 2058.26   431.1 2064.29   455.8 2067.84
     470 2069.35   506.8 2070.44   515.6 2072.75   547.3 2076.01   565.9 2079.47
#Mann= 5 ,-1,0
       0      .1       0  168.35     .08       0     244    .045       0
   316.6     .08       0  482.86      .1       0
Bank Sta=244,316.6
XS Rating Curve= 0 ,0
Exp/Cntr(USF)=0,0
Exp/Cntr=0.3,0.1

Type RM Length L Ch R = 1 ,43234   ,250.7,259.6,247.6
XS GIS Cut Line= 3
2211263.74677445667152.0065277032211636.77660465667070.598895442
2211809.80425717667020.167278642
#Sta/Elev= 30
       0 2089.89    29.1 2081.35    49.6 2077.12    94.6 2072.15   106.9  2072.1
   143.5 2069.82   176.5 2065.65   184.7 2063.39   205.1 2051.22   213.3 2050.89
   254.3 2054.71     275 2053.28   282.9 2051.95   289.42049.854   295.1 2048.82
   315.7  2048.6   336.2 2051.53   342.5 2051.76   355.6 2051.53   368.9 2053.46
   397.8 2052.89     418 2051.15   435.3 2048.47   439.5 2049.09     452 2056.67
   464.5 2060.28   505.1  2064.3   522.8 2066.86   543.7 2067.29     562 2070.92
#Mann= 3 ,-1,0
       0      .1       0   289.4    .045       0   342.5      .1       0
Bank Sta=289.4,342.5
XS Rating Curve= 0 ,0
Exp/Cntr(USF)=0,0
Exp/Cntr=0.3,0.1

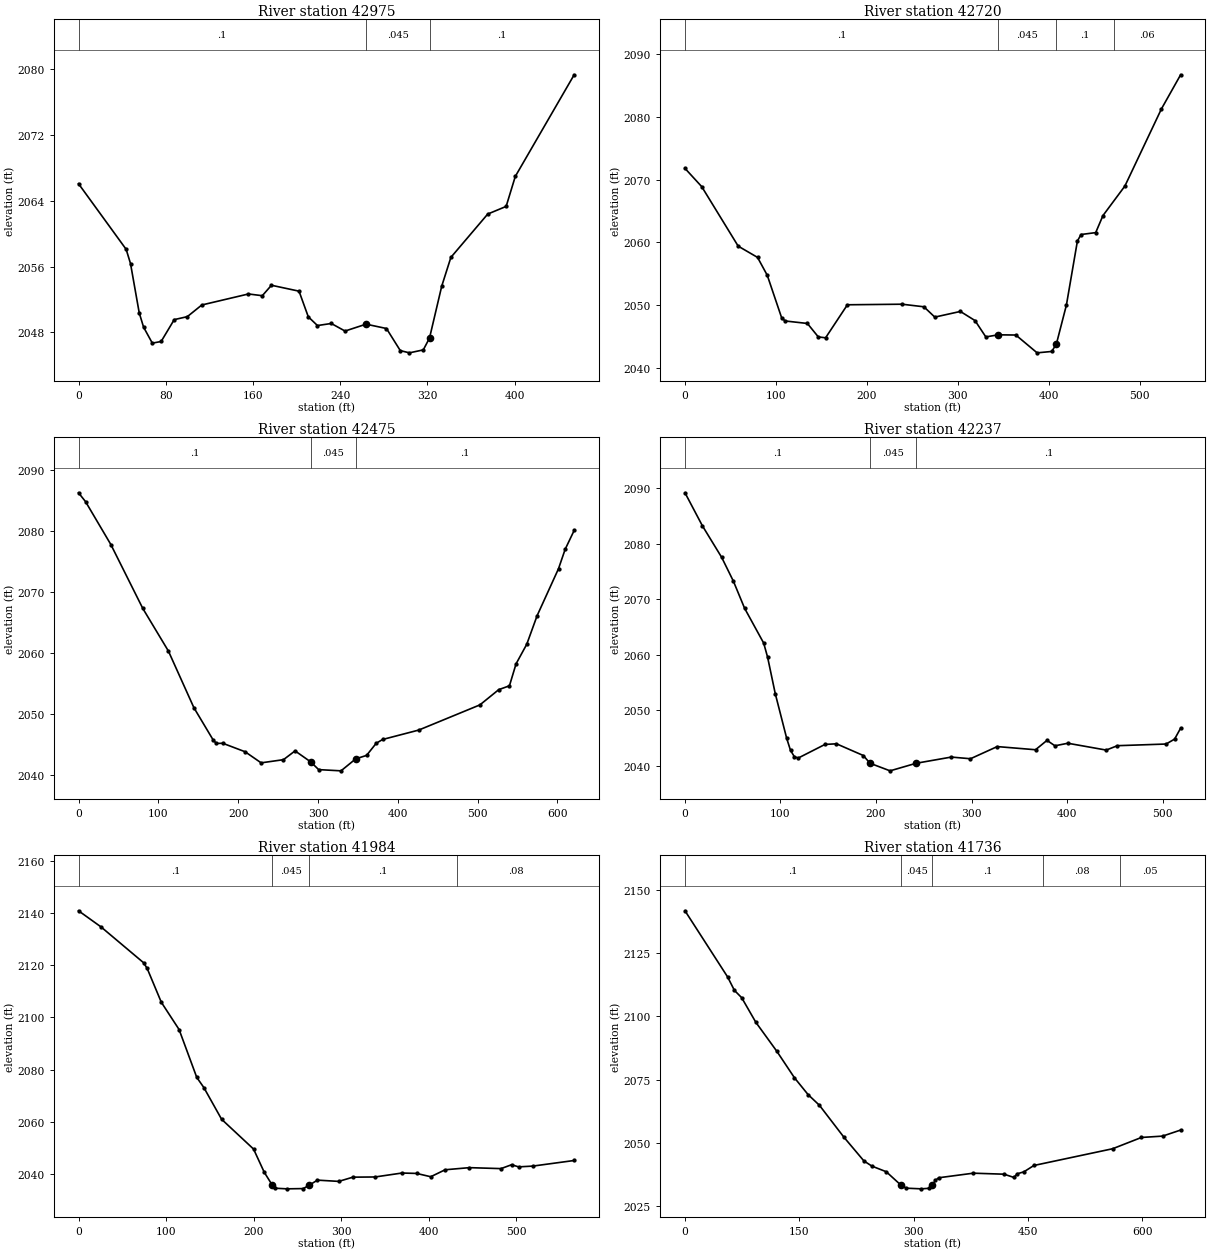
Type RM Length L Ch R = 1 ,42975   ,244.8,254.5,258.7
XS GIS Cut Line= 3
2211420.59464999667342.2277112452211577.00692196667331.482058266
2211859.39422206667236.434625549
#Sta/Elev= 30
       0 2066.07    43.7 2058.09    47.7 2056.36    55.7 2050.36    59.7 2048.62
    67.7 2046.68    75.8 2046.88    87.8 2049.54    99.8  2049.9   113.1 2051.32
   155.9 2052.66   168.6 2052.45     177 2053.72   202.3    2053   210.8 2049.88
   219.2 2048.82   231.9 2049.07   244.5 2048.15   263.82048.987   282.5 2048.46
   295.2 2045.77   303.6  2045.5   316.3 2045.86     3222047.299   333.2 2053.61
   341.6 2057.11   375.4 2062.38   392.3 2063.31   400.7 2066.96   454.7 2079.32
#Mann= 3 ,-1,0
       0      .1       0   263.8    .045       0     322      .1       0
Bank Sta=263.8,322
XS Rating Curve= 0 ,0
Exp/Cntr(USF)=0,0
Exp/Cntr=0.3,0.1

Type RM Length L Ch R = 1 ,42720   ,234,245.5,245.4
XS GIS Cut Line= 3
2211381.78475522667555.9122532132211662.97323487667541.802180679
2211925.18017426667516.139373845
#Sta/Elev= 30
       0 2071.77    18.4 2068.87    58.5 2059.41    79.8 2057.62    90.5 2054.77
   106.5 2047.93   110.5 2047.51   134.6 2047.12   146.6 2044.98   154.6 2044.84
   178.6 2050.09   238.7 2050.18   262.7 2049.77   274.7 2048.13   302.8 2049.03
   318.9 2047.58   330.8 2044.98   344.42045.315   363.8 2045.28   387.2 2042.45
   403.3 2042.67   408.42043.865   419.4 2050.04   431.5 2060.23   435.5 2061.26
   451.6 2061.56   459.6 2064.27   483.7 2068.96   523.9 2081.23     545 2086.65
#Mann= 4 ,-1,0
       0      .1       0   344.4    .045       0   408.4      .1       0
  471.54     .06       0
Bank Sta=344.4,408.4
XS Rating Curve= 0 ,0
Exp/Cntr(USF)=0,0
Exp/Cntr=0.3,0.1

Type RM Length L Ch R = 1 ,42475   ,236.9,238.1,238.5
XS GIS Cut Line= 3
2211383.75302611667745.0621274112211812.54505508667768.158653561
2211999.21303822667724.861536397
#Sta/Elev= 30
       0 2086.19     8.8 2084.74    40.5 2077.71    80.5 2067.24   112.6 2060.25
   144.6 2050.95   168.7 2045.67   172.7  2045.1   180.7 2045.13   208.7 2043.74
   228.8 2041.92   256.8 2042.44   271.3 2043.88   290.72042.098   300.9 2040.81
   328.9 2040.61   347.32042.574   360.9 2043.14     373 2045.13     381 2045.75
   426.2 2047.29   502.9 2051.42   526.5 2053.92   539.9 2054.55   548.2 2058.15
   561.6 2061.36   574.6 2066.05   601.4 2073.75   609.7 2076.92     621 2080.02
#Mann= 3 ,-1,0
       0      .1       0   290.7    .045       0   347.3      .1       0
Bank Sta=290.7,347.3
XS Rating Curve= 0 ,0
Exp/Cntr(USF)=0,0
Exp/Cntr=0.3,0.1

Type RM Length L Ch R = 1 ,42237   ,257.4,252.8,247.7
XS GIS Cut Line= 3
 2211441.8971773667981.6845294592211825.82169373668006.086511435
2211945.78259898667945.979146423
#Sta/Elev= 30
       0  2089.2    18.3 2083.23    38.4 2077.57    50.7 2073.27    62.4  2068.4
    82.4 2062.12    86.5 2059.58    94.5 2053.03   106.5 2044.95   110.5 2042.79
   114.5 2041.66   118.5 2041.41   146.6 2043.87   158.6 2043.98   186.7 2041.87
   193.72040.477   214.7 2039.11     2422040.474   278.8 2041.59   298.9 2041.29
   326.9 2043.48     367 2042.91     379  2044.6   387.3 2043.62   400.8 2044.08
     441 2042.85   452.7 2043.64   503.7 2043.94   512.6 2044.83   518.9  2046.8
#Mann= 3 ,-1,0
       0      .1       0   193.7    .045       0     242      .1       0
Bank Sta=193.7,242
XS Rating Curve= 0 ,0
Exp/Cntr(USF)=0,0
Exp/Cntr=0.3,0.1

Type RM Length L Ch R = 1 ,41984   ,255.6,247.7,241.1
XS GIS Cut Line= 3
2211422.83162417668285.2030205412211790.66890803668224.649954156
2211983.41047816668242.127298155
#Sta/Elev= 30
       0 2140.77    25.7  2134.6    74.3  2120.9    78.4 2118.74    94.6 2105.76
   114.9 2095.33   135.1    2077   143.2 2073.11   163.5 2060.97     200 2049.57
   212.2  2040.7   221.52035.699   224.3  2034.6   237.9 2034.35   256.8 2034.45
   263.32035.698     273 2037.68   297.3  2037.2   313.5 2038.82   338.8 2038.89
   369.5  2040.4   386.3 2040.25   402.4 2038.98   418.9 2041.65   446.6 2042.46
   482.7 2042.09   494.8 2043.58   502.8 2042.76   518.9 2043.05   566.3  2045.2
#Mann= 4 ,-1,0
       0      .1       0   221.5    .045       0   263.3      .1       0
  432.79     .08       0
Bank Sta=221.5,263.3
XS Rating Curve= 0 ,0
Exp/Cntr(USF)=0,0
Exp/Cntr=0.3,0.1

Type RM Length L Ch R = 1 ,41736   ,247,248.9,248.6
XS GIS Cut Line= 3
2211539.68940423668597.2001076162211877.81067487 668402.54354545
  2212118.874177668304.953266335
#Sta/Elev= 30
       0 2141.86    55.9 2115.67    64.8 2110.36    74.4 2107.43    92.9 2097.72
   120.6 2086.17   143.6 2075.73   161.5 2069.06   176.4 2064.82   208.3 2052.26
   234.7  2042.8   245.2 2040.74     264 2038.52   283.22033.236   290.4    2032
   309.8 2031.74   319.7 2031.94   324.62033.215   328.4  2035.1   332.9 2036.13
   378.2 2037.94   418.6 2037.54   431.5 2036.25     436 2037.72   444.5 2038.46
   457.7 2040.99     561 2047.62   598.8 2052.09   626.5 2052.62   650.2 2055.02
#Mann= 5 ,-1,0
       0      .1       0   283.2    .045       0   324.6      .1       0
  470.15     .08       0  570.15     .05       0
Bank Sta=283.2,324.6
XS Rating Curve= 0 ,0
Exp/Cntr(USF)=0,0
Exp/Cntr=0.3,0.1

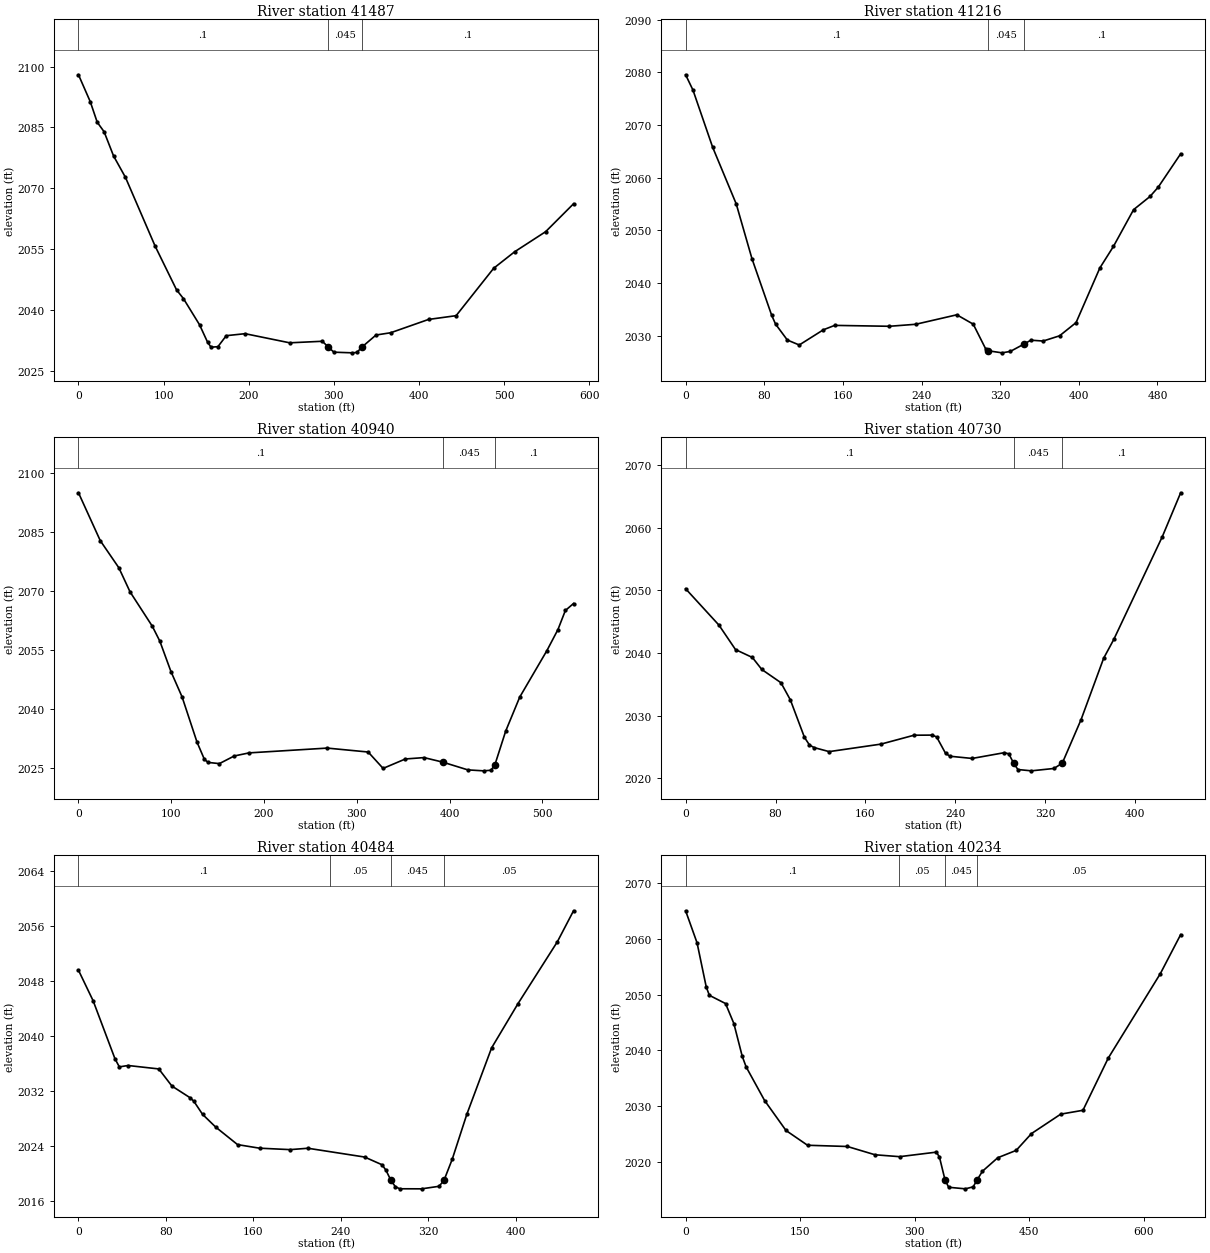
Type RM Length L Ch R = 1 ,41487   ,266.5,270.9,273.9
XS GIS Cut Line= 5
2211662.47990369 668722.834009762211855.58343501668691.217965462
2211993.15839512668619.9199934332212035.33466026668597.827664072
 2212216.6884376668571.365041978
#Sta/Elev= 30
       0 2097.96    13.9  2091.3      22 2086.27    30.1 2083.92    41.2 2077.96
    55.2 2072.67      90 2055.75   115.2 2044.96   123.3  2042.8   142.2 2036.36
   151.7 2032.03   155.7 2030.83   163.8 2030.96   173.6 2033.67   195.7 2034.16
   248.1 2031.91   286.4 2032.29   293.22030.922     300  2029.6   321.8 2029.44
     327 2029.54   333.62030.983   349.5 2033.83   366.7 2034.39   411.2 2037.67
   443.6  2038.6   487.7 2050.28   512.3 2054.34   548.7 2059.29   581.5 2066.17
#Mann= 3 ,-1,0
       0      .1       0   293.2    .045       0   333.6      .1       0
Bank Sta=293.2,333.6
XS Rating Curve= 0 ,0
Exp/Cntr(USF)=0,0
Exp/Cntr=0.3,0.1

Type RM Length L Ch R = 1 ,41216   ,263.5,276.1,279
XS GIS Cut Line= 3
2211724.67168318668941.8122382632211900.71168056668936.635946734
2212214.02107877668841.237251766
#Sta/Elev= 30
       0 2079.54     7.5 2076.63    27.5 2065.79    51.5 2055.03    67.5 2044.64
    87.5 2033.92    91.5 2032.22   103.5  2029.2   115.6 2028.26   140.1 2031.14
   151.6 2031.98   207.3 2031.81   234.1 2032.19   275.9 2033.99   292.6 2032.21
   305.2 2027.54   307.72027.165   321.9 2026.77   330.3 2027.04   344.12028.419
   351.2 2029.17   363.7 2029.01   380.4    2030   397.2 2032.51   421.4 2042.88
   435.2 2046.96   455.7 2053.94   472.4 2056.44   480.8 2058.22   503.6 2064.54
#Mann= 3 ,-1,0
       0      .1       0   307.7    .045       0   344.1      .1       0
Bank Sta=307.7,344.1
XS Rating Curve= 0 ,0
Exp/Cntr(USF)=0,0
Exp/Cntr=0.3,0.1

Type RM Length L Ch R = 1 ,40940   ,205.9,210.6,207
XS GIS Cut Line= 2
2211724.75528351669167.9432905432212256.96598837669127.781843925
#Sta/Elev= 30
       0 2095.03    23.5 2082.84    43.5 2075.95    55.6 2069.81    79.6 2061.06
    87.7 2057.27    99.7 2049.52   111.7 2043.07   127.8 2031.56   135.8 2027.15
   139.8  2026.4   151.9  2026.1   167.9 2028.04   183.9 2028.83   268.2 2030.05
   312.3 2029.05   328.4 2024.88   352.4 2027.28   372.5 2027.63   392.5 2026.49
   419.8  2024.5   436.7 2024.26   444.7 2024.41   448.92025.793   460.6  2034.4
   475.7 2043.03   504.9 2054.82   516.9 2060.22   524.9 2065.07   533.7 2066.85
#Mann= 3 ,-1,0
       0      .1       0   392.5    .045       0   448.9      .1       0
Bank Sta=392.5,448.9
XS Rating Curve= 0 ,0
Exp/Cntr(USF)=0,0
Exp/Cntr=0.3,0.1

Type RM Length L Ch R = 1 ,40730   ,245.1,245.6,244.9
XS GIS Cut Line= 3
2211840.14177519669415.8122590762212028.48298011669350.031669097
2212268.48601272669328.943536525
#Sta/Elev= 30
       0 2050.26    29.7 2044.44    44.4 2040.54    59.4 2039.28    67.8 2037.36
    84.8 2035.25    93.2  2032.5   105.7 2026.53   110.2 2025.29   114.4 2024.88
   127.7 2024.24   173.8 2025.44   203.2 2026.86   219.3 2026.88   223.3 2026.59
   231.3 2023.95   235.3  2023.5   254.9 2023.15   283.5 2024.07   287.5 2023.89
   291.82022.399   295.6 2021.38   307.6 2021.17   327.7 2021.55   335.12022.402
   351.8 2029.35   371.9 2039.16   380.9 2042.16   424.1 2058.59   440.4 2065.59
#Mann= 3 ,-1,0
       0      .1       0   291.8    .045       0   335.1      .1       0
Bank Sta=291.8,335.1
XS Rating Curve= 0 ,0
Exp/Cntr(USF)=0,0
Exp/Cntr=0.3,0.1

Type RM Length L Ch R = 1 ,40484   ,249.7,249.9,248.8
XS GIS Cut Line= 2
2211822.84674822669603.2010642562212274.92127491669573.440935199
#Sta/Elev= 30
       0  2049.6    13.4 2045.16    33.4 2036.71    37.4 2035.53    45.4 2035.73
    73.5 2035.23    85.5 2032.74   102.2 2031.03   105.6 2030.52   113.6 2028.61
   125.6 2026.76   145.6 2024.21   165.7 2023.69   193.7 2023.48     210 2023.68
   261.9  2022.4   277.9 2021.27   281.5 2020.46     2862018.987     290 2018.09
     294 2017.78     314 2017.77     330 2018.14   334.52018.995   342.1 2022.09
   355.4 2028.61   378.1 2038.29   402.2 2044.72   438.3 2053.75   453.1 2058.26
#Mann= 4 ,-1,0
       0      .1       0     230     .05       0     286    .045       0
   334.5     .05       0
Bank Sta=286,334.5
XS Rating Curve= 0 ,0
Exp/Cntr(USF)=0,0
Exp/Cntr=0.3,0.1

Type RM Length L Ch R = 1 ,40234   ,247.5,248,247.2
XS GIS Cut Line= 2
2211773.26459067669867.418843097 2212418.5981653669803.609086853
#Sta/Elev= 30
       0 2064.97      15 2059.24      27 2051.37    31.1 2049.86    52.3 2048.39
    63.2 2044.82    74.2 2038.95    79.3 2037.06   103.5 2031.05   131.5  2025.7
   159.7 2023.06   211.9 2022.84   248.1 2021.36   280.3 2021.02   328.5 2021.83
   332.5 2020.96   339.8 2016.88   344.6 2015.55   366.5 2015.27   376.7 2015.63
   381.82016.849   388.8 2018.41   408.9 2020.83     433 2022.14   453.1 2025.15
   491.4 2028.62   520.5 2029.31   553.6 2038.63   621.9 2053.74   648.5 2060.71
#Mann= 4 ,-1,0
       0      .1       0     280     .05       0   339.8    .045       0
   381.8     .05       0
Bank Sta=339.8,381.8
XS Rating Curve= 0 ,0
Exp/Cntr(USF)=0,0
Exp/Cntr=0.3,0.1

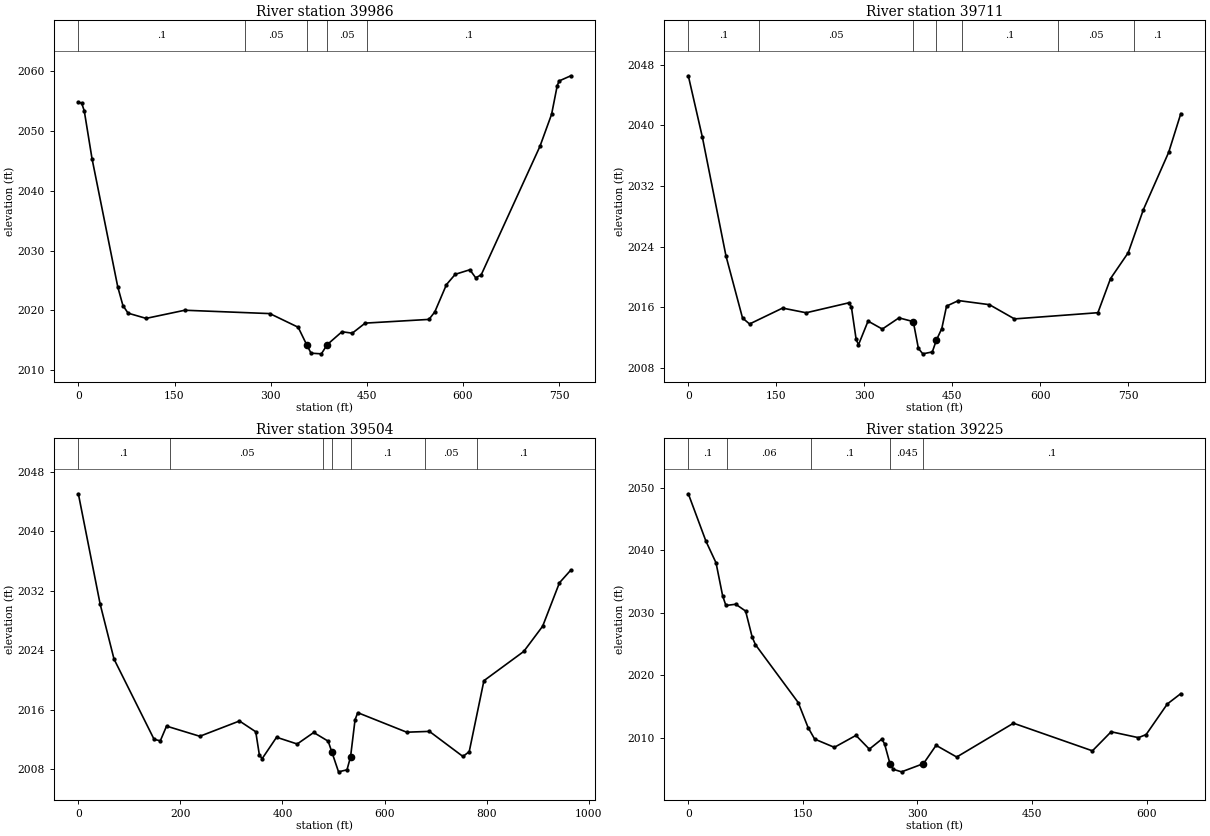
Type RM Length L Ch R = 1 ,39986   ,275.5,274.9,273.7
XS GIS Cut Line= 3
 2211794.9845138670113.7683535752212279.43926084670065.258382805
2212526.52777157 669930.81372727
#Sta/Elev= 30
       0 2054.78     5.2  2054.6     9.2 2053.33    21.3 2045.36    61.5 2023.92
    69.5 2020.82    77.6 2019.54   105.7 2018.67     166 2020.03   298.7 2019.47
   342.9 2017.19   356.1 2014.28     363 2012.86   379.1 2012.75   388.22014.289
   411.2 2016.44   427.3  2016.2   447.4 2017.88   546.9  2018.5     556 2019.75
   574.2 2024.31   587.9 2026.03   610.7 2026.79   619.8 2025.45   628.4 2025.94
     720 2047.39   738.2 2052.75     747 2057.54     750 2058.32   768.2 2059.18
#Mann= 5 ,-1,0
       0      .1       0     260     .05       0   356.1    .045       0
   388.2     .05       0     450      .1       0
Bank Sta=356.1,388.2
XS Rating Curve= 0 ,0
Exp/Cntr(USF)=0,0
Exp/Cntr=0.3,0.1

Type RM Length L Ch R = 1 ,39711   ,206.5,207.1,207
XS GIS Cut Line= 4
2211828.30458097670397.9777668942212033.98757839670376.861112424
2212342.54735997670324.5161494782212639.31598517670205.452510164
#Sta/Elev= 30
       0 2046.56      24 2038.44    64.2 2022.78    92.4 2014.59   104.4  2013.8
   160.7  2015.9   200.9 2015.28   273.9  2016.6     278 2016.04   286.1 2011.76
   290.1 2011.06   306.4 2014.18   330.7 2013.13   359.1 2014.61   383.52014.111
   392.2 2010.58   399.7 2009.86   415.9 2010.11     4232011.691   432.1  2013.2
   440.2 2016.16   460.5 2016.89   513.3 2016.35     556 2014.47   698.2 2015.29
   719.7 2019.79   749.9 2023.21   775.8 2028.91   818.9 2036.47   839.5 2041.56
#Mann= 7 ,-1,0
       0      .1       0     120     .05       0   383.5    .045       0
     423     .05       0  466.76      .1       0  629.73     .05       0
  759.73      .1       0
Bank Sta=383.5,423
XS Rating Curve= 0 ,0
Exp/Cntr(USF)=0,0
Exp/Cntr=0.3,0.1

Type RM Length L Ch R = 1 ,39504   ,289.2,279.3,256.6
XS GIS Cut Line= 4
2211770.51920912 670508.876522642212094.41389928670571.625372726
2212451.03309128670516.5254117312212717.90762277670453.299436163
#Sta/Elev= 30
       0 2045.08    42.6 2030.25    69.9 2022.81   148.4    2012   160.6  2011.8
   172.8 2013.78     238 2012.41   315.7 2014.47   347.6 2013.02   354.6 2009.94
     360 2009.38   388.4 2012.28   428.8 2011.37   461.2 2012.92   489.5 2011.75
   496.52010.341   509.8 2007.62   526.4 2007.89   533.42009.652   542.2 2014.64
   547.5 2015.59   643.4 2012.96   687.9 2013.07   753.6 2009.69   765.9 2010.34
   794.7  2019.9   872.8 2023.84   909.8 2027.24   942.7 2033.09     965  2034.8
#Mann= 7 ,-1,0
       0      .1       0     180     .05       0  479.92      .1       0
   496.5    .045       0   533.4      .1       0  679.92     .05       0
  780.77      .1       0
Bank Sta=496.5,533.4
XS Rating Curve= 0 ,0
Exp/Cntr(USF)=0,0
Exp/Cntr=0.3,0.1

Type RM Length L Ch R = 1 ,39225   ,361.7,361.8,341.8
XS GIS Cut Line= 4
2212183.92322558671066.8862992132212263.51205812670866.383663368
2212398.20085167670701.0837803822212609.41736882670656.697700691
#Sta/Elev= 30
       0 2049.02    23.1 2041.43    36.3 2037.97    44.9 2032.72    49.2 2031.15
    62.1 2031.35      75 2030.26    83.6  2026.1    87.9 2024.88   143.9 2015.62
   156.8 2011.63   165.4 2009.78   191.2 2008.46   219.5 2010.37     237 2008.17
   253.4 2009.78   256.9 2009.03     2642005.859   268.2 2004.95   279.2 2004.54
   307.92005.853   324.4 2008.78   351.4 2006.91   425.7 2012.32   529.1  2007.9
   553.6 2010.95   589.3 2010.01   599.4  2010.5   627.2  2015.4   644.8 2017.05
#Mann= 5 ,-1,0
       0      .1       0      50     .06       0     160      .1       0
     264    .045       0   307.9      .1       0
Bank Sta=264,307.9
XS Rating Curve= 0 ,0
Exp/Cntr(USF)=0,0
Exp/Cntr=0.3,0.1