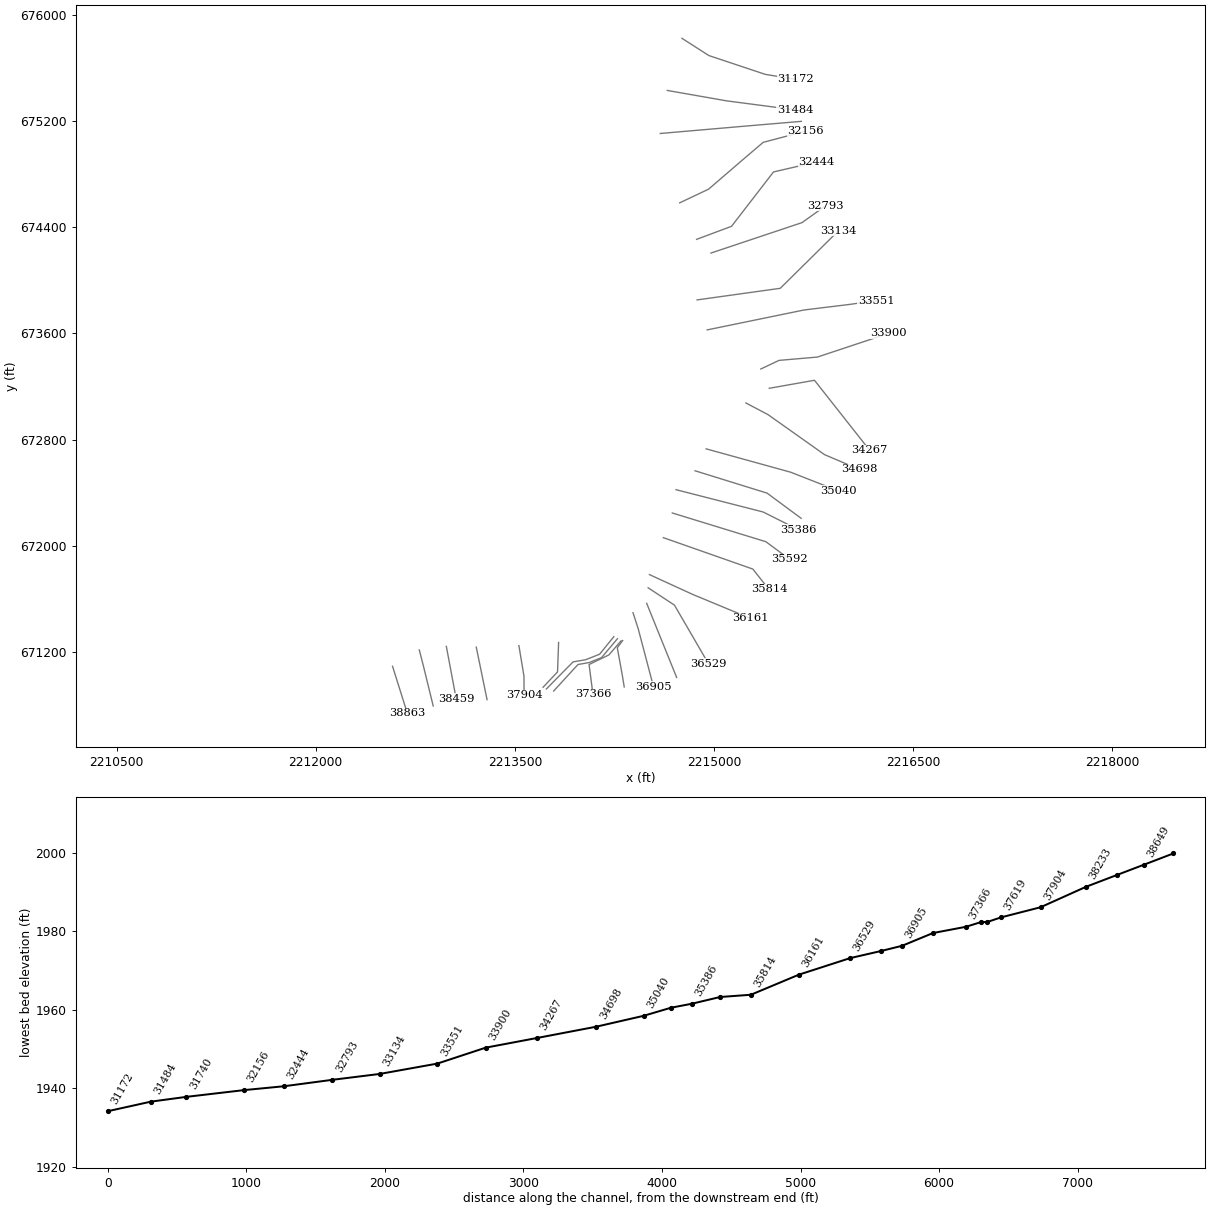
HEC-RAS study RFMIDDLERV.prj: RFMIDDLERV

--- RFMIDDLERV.g01 (geometry) --- (continued)

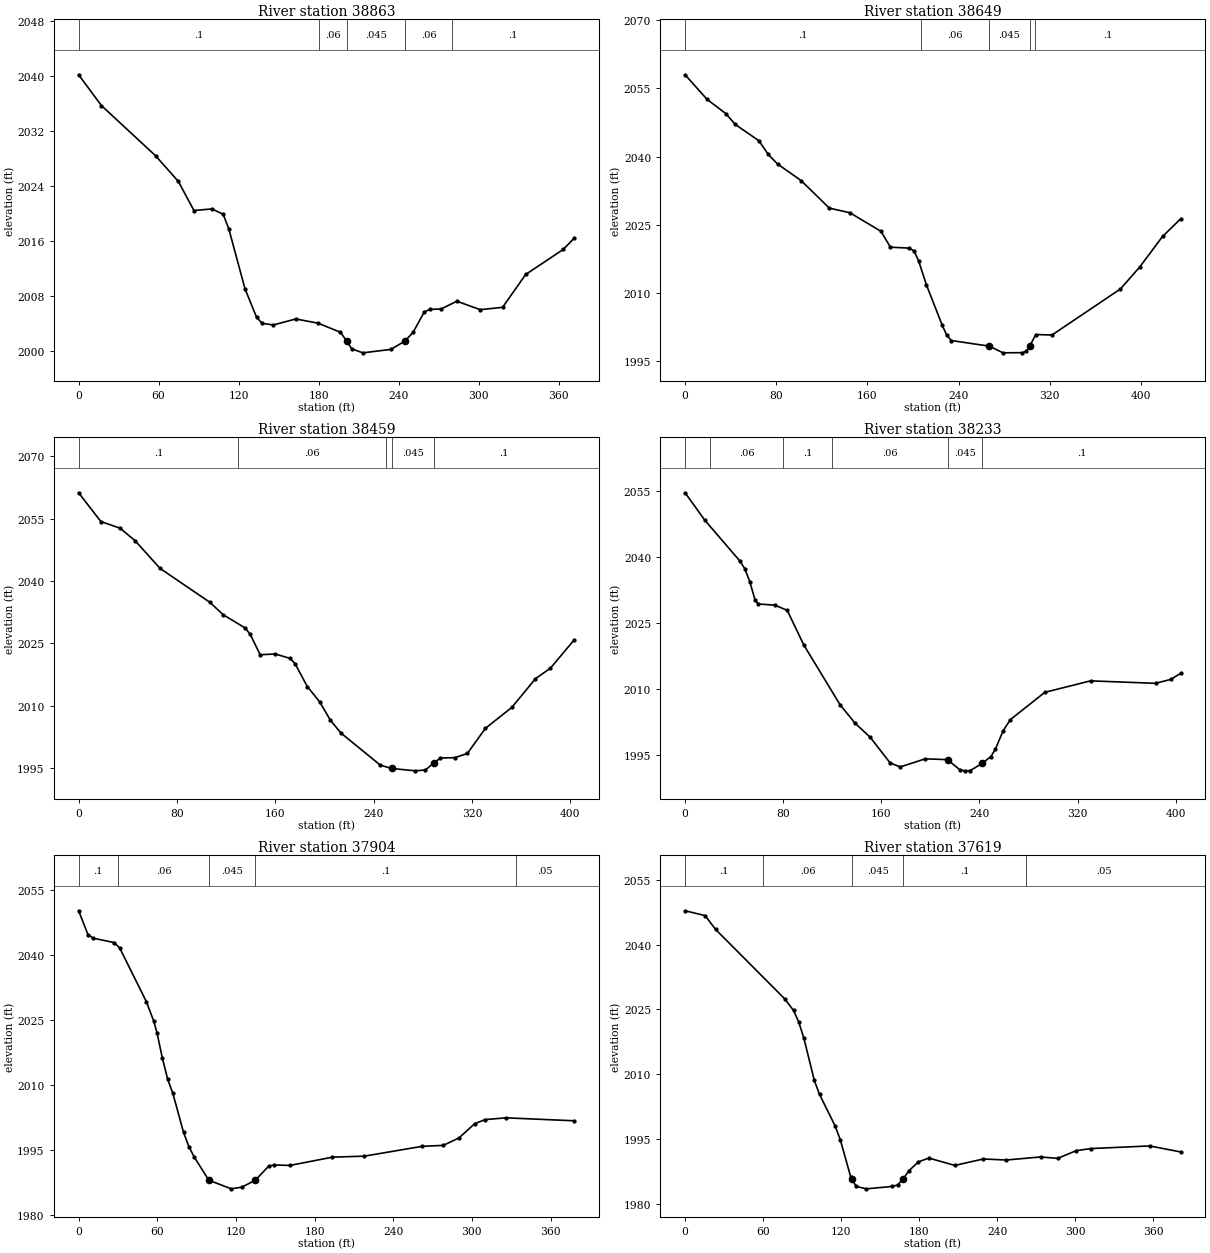
Type RM Length L Ch R = 1 ,38863   ,214.3,214,211.9
XS GIS Cut Line= 2
2212579.03038278671092.549162734 2212690.6078038670737.980913728
#Sta/Elev= 30
       0 2040.23    17.1 2035.75    57.8 2028.43    74.8 2024.71    86.5 2020.48
     100 2020.71   108.4 2019.94   112.6 2017.83   124.8 2009.08   133.5 2004.93
   137.7 2004.06   146.1 2003.83   162.9  2004.7   179.7 2004.08   196.4 2002.76
   201.12001.473   204.8 2000.36   213.2 1999.77   234.2 2000.27   244.82001.487
   250.9 2002.76   259.3 2005.72   263.5 2006.09   271.9 2006.15   283.7 2007.28
   301.3 2006.05     318 2006.39   335.3 2011.17   363.6 2014.83   371.7 2016.45
#Mann= 5 ,-1,0
       0      .1       0     180     .06       0   201.1    .045       0
   244.8     .06       0     280      .1       0
Bank Sta=201.1,244.8
XS Rating Curve= 0 ,0
Exp/Cntr(USF)=0,0
Exp/Cntr=0.3,0.1

Type RM Length L Ch R = 1 ,38649   ,189.9,190.5,189.4
XS GIS Cut Line= 3
2212780.35207365671215.8161337362212809.62371955671102.467155713
2212885.24841602670793.769624236
#Sta/Elev= 30
       0 2057.97    19.2 2052.59    35.8 2049.43      44 2047.06    64.7 2043.49
      73 2040.47    81.2 2038.36   101.9 2034.71   126.6 2028.67   144.6 2027.66
   171.9 2023.58   180.2 2020.09   196.6 2019.89   200.8 2019.29   204.9 2017.11
   211.8 2011.81   225.5 2003.04   229.6 2000.77   233.7 1999.58     2671998.348
     279 1996.88   295.9 1996.92   299.6 1997.22   302.41998.344   307.8  2000.9
     322  2000.8     382  2010.9     399 2015.74     419 2022.44   434.9 2026.32
#Mann= 5 ,-1,0
       0      .1       0  207.07     .06       0     267    .045       0
   302.4     .06       0  307.07      .1       0
Bank Sta=267,302.4
XS Rating Curve= 0 ,0
Exp/Cntr(USF)=0,0
Exp/Cntr=0.3,0.1

Type RM Length L Ch R = 1 ,38459   ,225.3,225.7,225.6
XS GIS Cut Line= 2
 2212984.1941271671242.3790208022213058.65175163670846.242660579
#Sta/Elev= 30
       0 2061.26    18.1 2054.34    33.8 2052.72      46  2049.7    66.3 2043.04
   106.8 2034.88   117.5 2031.92   135.5 2028.71   139.6 2027.16   147.7 2022.27
     160 2022.45   172.2 2021.37   176.2 2020.04     186 2014.62   196.3 2010.84
   204.7 2006.54   213.4 2003.42   245.4 1995.69   254.61994.897   273.9 1994.32
   282.1 1994.53   288.91996.216   294.3 1997.41   305.9 1997.49   316.2  1998.5
   330.9 2004.55   352.4  2009.6   371.6  2016.5   383.8 2019.04   403.1 2025.84
#Mann= 5 ,-1,0
       0      .1       0     130     .06       0     250      .1       0
   254.6    .045       0   288.9      .1       0
Bank Sta=254.6,288.9
XS Rating Curve= 0 ,0
Exp/Cntr(USF)=0,0
Exp/Cntr=0.3,0.1

Type RM Length L Ch R = 1 ,38233   ,326.4,328.8,324
XS GIS Cut Line= 2
 2213209.6362515671236.9697079892213290.97619142670841.115333708
#Sta/Elev= 30
       0 2054.63    16.1 2048.37    44.7 2039.08    48.8 2037.28    52.9 2034.24
      57 2030.27    59.6 2029.29    73.3 2029.03    83.3 2027.83    96.8 2019.96
   126.4 2006.33   138.6 2002.13   150.9 1998.95   167.2 1993.08   175.4 1992.17
   195.8 1994.01     2141993.834   224.4 1991.43   228.5 1991.28   232.5 1991.34
   242.41993.002   249.3 1994.51     253  1996.2   259.4 2000.43   265.2 2002.94
   293.3 2009.16   330.6 2011.78   383.6 2011.22   395.9  2012.1   404.1 2013.48
#Mann= 6 ,-1,0
       0      .1       0      20     .06       0      80      .1       0
     120     .06       0     214    .045       0   242.4      .1       0
Bank Sta=214,242.4
XS Rating Curve= 0 ,0
Exp/Cntr(USF)=0,0
Exp/Cntr=0.3,0.1

Type RM Length L Ch R = 1 ,37904   ,284.2,285.3,277.2
XS GIS Cut Line= 3
2213530.78120717671248.1395224922213569.12506478671017.509318342
2213569.57120916670873.269067472
#Sta/Elev= 30
       0 2050.13     7.1 2044.65    11.1 2043.82    27.3 2042.79    31.4 2041.52
    51.7 2029.17    57.3  2024.7    59.8    2022    63.8 2016.27    67.9 2011.35
    71.9 2008.03      80 1999.09    84.1 1995.79    88.2 1993.38    99.31988.042
   116.5 1986.06   124.6 1986.46   134.81988.052   144.9 1991.27     149 1991.57
   161.1 1991.45   193.6 1993.36   217.9 1993.59   262.1 1995.86   278.1 1996.07
   290.1 1997.78   302.1 2001.07   310.1 2002.02   326.1 2002.42     378 2001.74
#Mann= 5 ,-1,0
       0      .1       0      30     .06       0    99.3    .045       0
   134.8      .1       0   333.8     .05       0
Bank Sta=99.3,134.8
XS Rating Curve= 0 ,0
Exp/Cntr(USF)=0,0
Exp/Cntr=0.3,0.1

Type RM Length L Ch R = 1 ,37619   ,114.6,100.7,84.5
XS GIS Cut Line= 3
2213829.93143065671272.5415044682213821.79743666671050.212335352
2213712.92812232670934.706342728
#Sta/Elev= 30
       0 2047.83    15.4 2046.72    23.4 2043.53    76.5 2027.49    83.4 2024.76
    87.4 2022.11    91.4  2018.3    99.4 2008.58   103.4 2005.33   115.4 1998.04
   119.4 1994.82   127.4 1986.25   128.31985.776   131.5 1984.05   139.5 1983.48
   159.5 1984.04   163.5 1984.39   167.81985.797     172 1987.62   179.5 1989.73
   187.5  1990.6   207.5  1988.9   229.4 1990.39     247 1990.15   273.4 1990.86
   286.6 1990.53   300.9 1992.32   312.1  1992.8   357.4 1993.41   381.2 1992.02
#Mann= 5 ,-1,0
       0      .1       0      60     .06       0   128.3    .045       0
   167.8      .1       0  262.48     .05       0
Bank Sta=128.3,167.8
XS Rating Curve= 0 ,0
Exp/Cntr(USF)=0,0
Exp/Cntr=0.3,0.1

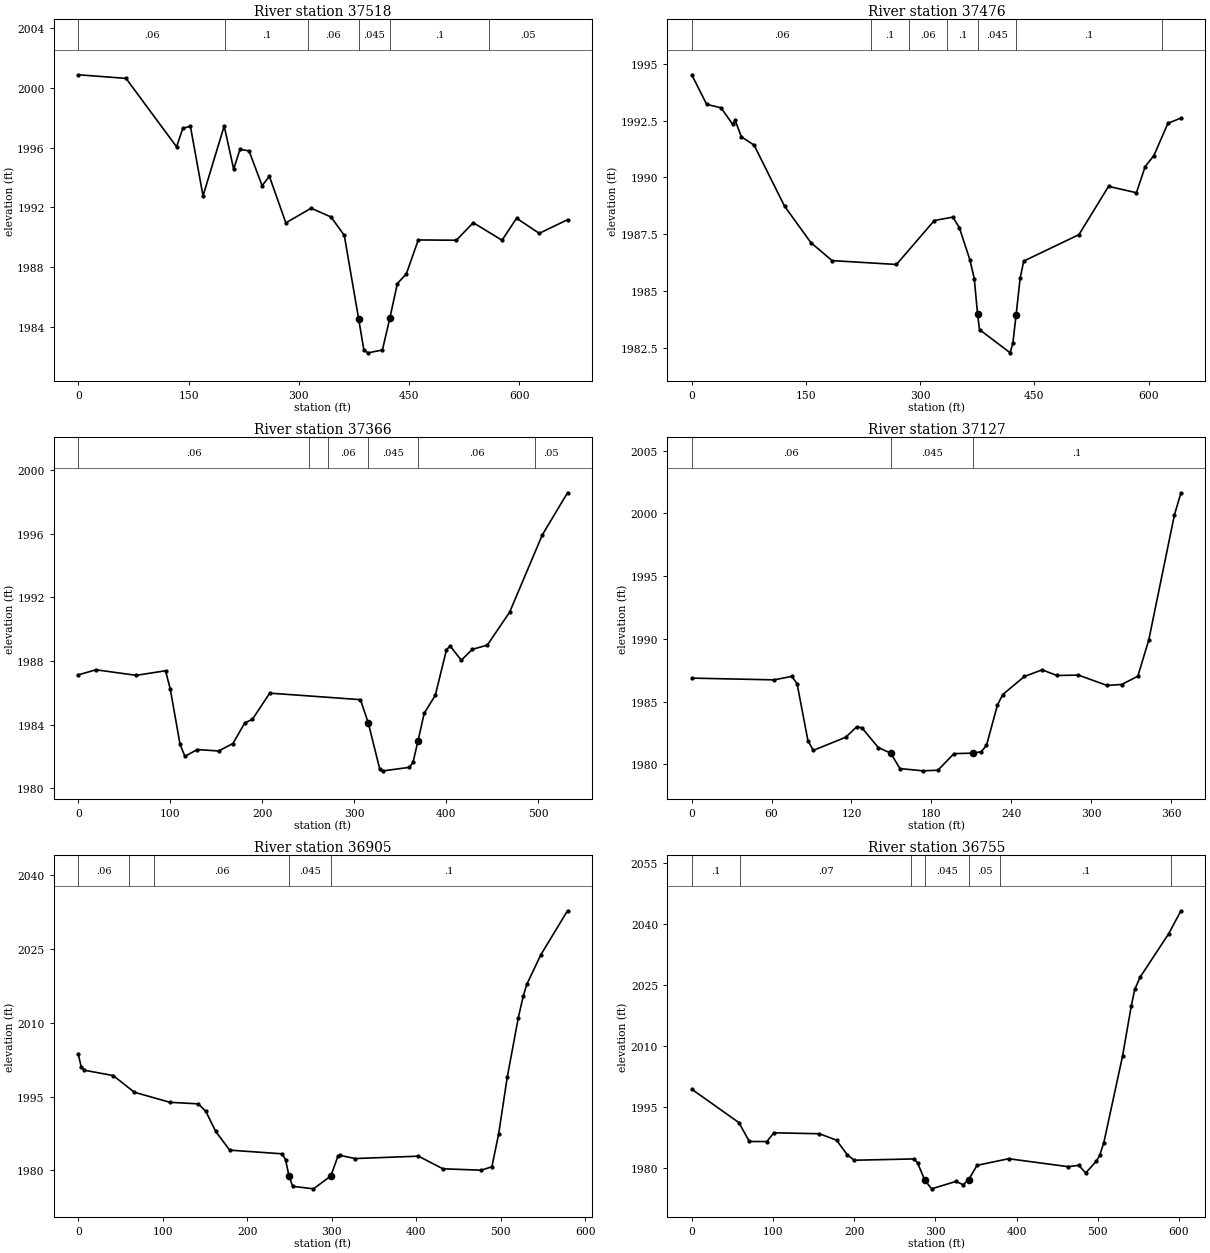
Type RM Length L Ch R = 1 ,37518   ,41.9,42,42.3
XS GIS Cut Line= 6
2214245.77735461671315.5793704572214138.89667356671183.808667786
2214034.21217088671142.0812786062213939.04444117671125.975970502
2213868.76673308671054.9662029512213737.72808987670921.731381361
#Sta/Elev= 30
       0 2000.86    64.9 2000.62   133.7 1996.05   142.2 1997.28   152.5 1997.43
   169.7 1992.77   198.5 1997.44   211.4 1994.56     220 1995.88   232.3 1995.78
   250.1 1993.45     260 1994.08   282.4 1990.97   316.9 1991.95   343.9 1991.36
   361.9 1990.14   381.41984.577   388.6 1982.47   394.3 1982.29   413.8 1982.48
   423.9  1984.6   434.1 1986.91   446.5 1987.58   462.6 1989.83   514.4 1989.81
   537.4 1990.98   576.6 1989.81   596.4 1991.28   627.2 1990.27   665.7 1991.18
#Mann= 6 ,-1,0
       0     .06       0  199.67      .1       0  312.36     .06       0
   381.4    .045       0   423.9      .1       0  558.79     .05       0
Bank Sta=381.4,423.9
XS Rating Curve= 0 ,0
Exp/Cntr(USF)=0,0
Exp/Cntr=0.3,0.1

Type RM Length L Ch R = 1 ,37476   ,88.9,109.8,133.2
XS GIS Cut Line= 6
 2214272.8635546671300.2061218122214153.53786274671158.186586711
2214060.56631141671120.8515542872213976.37947359671106.210365101
2213944.90091684671072.5356299742213792.63254931670906.358132716
#Sta/Elev= 30
       0 1994.51    19.6 1993.21    38.4 1993.06    53.7 1992.34      57 1992.51
    65.1 1991.79    81.9 1991.42   121.9 1988.74   156.5 1987.14   184.3 1986.35
   268.9 1986.18   318.6 1988.11   342.9 1988.26   351.5  1987.8   365.3 1986.39
   371.1 1985.56   375.51983.984     378 1983.32   418.3  1982.3   421.8 1982.73
   426.11983.979   431.4 1985.59   436.1 1986.33   508.6 1987.49   547.5 1989.61
   584.1 1989.33   595.6 1990.48     607 1990.96   625.5 1992.38   642.6 1992.61
#Mann= 7 ,-1,0
       0     .06       0  235.49      .1       0  285.49     .06       0
  335.68      .1       0   375.5    .045       0   426.1      .1       0
  617.23     .05       0
Bank Sta=375.5,426.1
XS Rating Curve= 0 ,0
Exp/Cntr(USF)=0,0
Exp/Cntr=0.3,0.1

Type RM Length L Ch R = 1 ,37366   ,237,238.9,238.9
XS GIS Cut Line= 4
2214300.75846775671284.869916871 2214208.5732025671178.224217864
2214059.44997931671105.9220490462214088.37084684670882.689102819
#Sta/Elev= 30
       0 1987.13    19.2 1987.45      63  1987.1    94.8 1987.39     100 1986.23
   110.6 1982.75   115.9    1982   129.3 1982.43   152.5 1982.34   168.1 1982.81
     181 1984.11   189.2 1984.33   208.1 1985.98   306.7 1985.57   315.31984.085
   327.6 1981.22   331.6 1981.09   359.9 1981.31   363.9 1981.64   369.21982.963
     376 1984.71   388.1 1985.85   400.2 1988.71   404.2 1988.95   416.3 1988.05
   428.4 1988.74   444.6    1989   468.9 1991.08   504.4 1995.94   531.8 1998.59
#Mann= 6 ,-1,0
       0     .06       0  250.97      .1       0  270.97     .06       0
   315.3    .045       0   369.2     .06       0  496.69     .05       0
Bank Sta=315.3,369.2
XS Rating Curve= 0 ,0
Exp/Cntr(USF)=0,0
Exp/Cntr=0.3,0.1

Type RM Length L Ch R = 1 ,37127   ,217.3,222,224.3
XS GIS Cut Line= 4
2214312.62059811671286.4572172622214271.99380861671232.952942873
2214309.93013175671024.3031655722214324.14275207670937.169456488
#Sta/Elev= 30
       0 1986.88    61.9 1986.74    75.1 1987.02    79.1 1986.44    87.3 1981.89
    91.3 1981.12   115.7 1982.17   123.9    1983   127.9 1982.91   140.1 1981.35
   149.51980.896   156.4 1979.67   173.8 1979.49   184.9 1979.54     197 1980.86
   211.41980.902   217.4 1981.01   221.4 1981.51   229.6 1984.72   233.6 1985.57
   249.9 1987.01   263.2 1987.54   274.3 1987.09   290.5 1987.12   311.8  1986.3
   322.9 1986.37   335.1 1987.03   343.3 1989.91   362.6 1999.89   367.5 2001.65
#Mann= 3 ,-1,0
       0     .06       0   149.5    .045       0   211.4      .1       0
Bank Sta=149.5,211.4
XS Rating Curve= 0 ,0
Exp/Cntr(USF)=0,0
Exp/Cntr=0.3,0.1

Type RM Length L Ch R = 1 ,36905   ,147.5,150,154
XS GIS Cut Line= 3
2214390.29342487671496.3583064122214428.86339756671377.893390272
2214544.70294805670938.615707544
#Sta/Elev= 30
       0 2003.59     3.3 2001.12     7.2 2000.36    41.2 1999.28    66.4 1995.88
   108.5 1993.84   141.9 1993.53   150.8 1992.02   162.6 1987.92   179.1 1984.12
   241.2 1983.37   245.3 1982.11   249.31978.865   253.6 1976.77   278.3 1976.25
   298.81978.862   307.3 1982.92   310.1 1983.04   327.6 1982.41   402.5 1982.89
   431.4 1980.33   476.9 1980.04   489.4 1980.74   497.4 1987.41   507.6 1998.96
   520.7 2011.08   526.6  2015.5   530.7 2017.82   547.3 2023.83   578.9 2032.78
#Mann= 5 ,-1,0
       0     .06       0      60      .1       0      90     .06       0
   249.3    .045       0   298.8      .1       0
Bank Sta=249.3,298.8
XS Rating Curve= 0 ,0
Exp/Cntr(USF)=0,0
Exp/Cntr=0.3,0.1

Type RM Length L Ch R = 1 ,36755   ,223.4,226.5,228.5
XS GIS Cut Line= 2
2214493.36361254671566.9253958422214719.12375276671008.385042603
#Sta/Elev= 30
       0 1999.39      58  1991.2    70.9 1986.56    92.5 1986.54   101.1 1988.69
   157.2 1988.46   178.3 1986.88   191.7 1983.24   200.3 1981.96   273.7 1982.28
     278 1981.36   286.71977.176   295.3 1974.94   325.5 1976.77   334.1 1975.95
     3411977.204   351.3 1980.71   390.2 1982.33   463.5 1980.38   476.5 1980.71
   485.1 1978.84   498.2 1981.72   502.4 1983.17   507.4 1986.26   530.5 2007.54
   541.2  2019.8   545.5 2023.87   551.9 2026.81   587.3 2037.55   602.4 2043.17
#Mann= 7 ,-1,0
       0      .1       0      60     .07       0     270     .05       0
   286.7    .045       0     341     .05       0     380      .1       0
     590     .06       0
Bank Sta=286.7,341
XS Rating Curve= 0 ,0
Exp/Cntr(USF)=0,0
Exp/Cntr=0.3,0.1

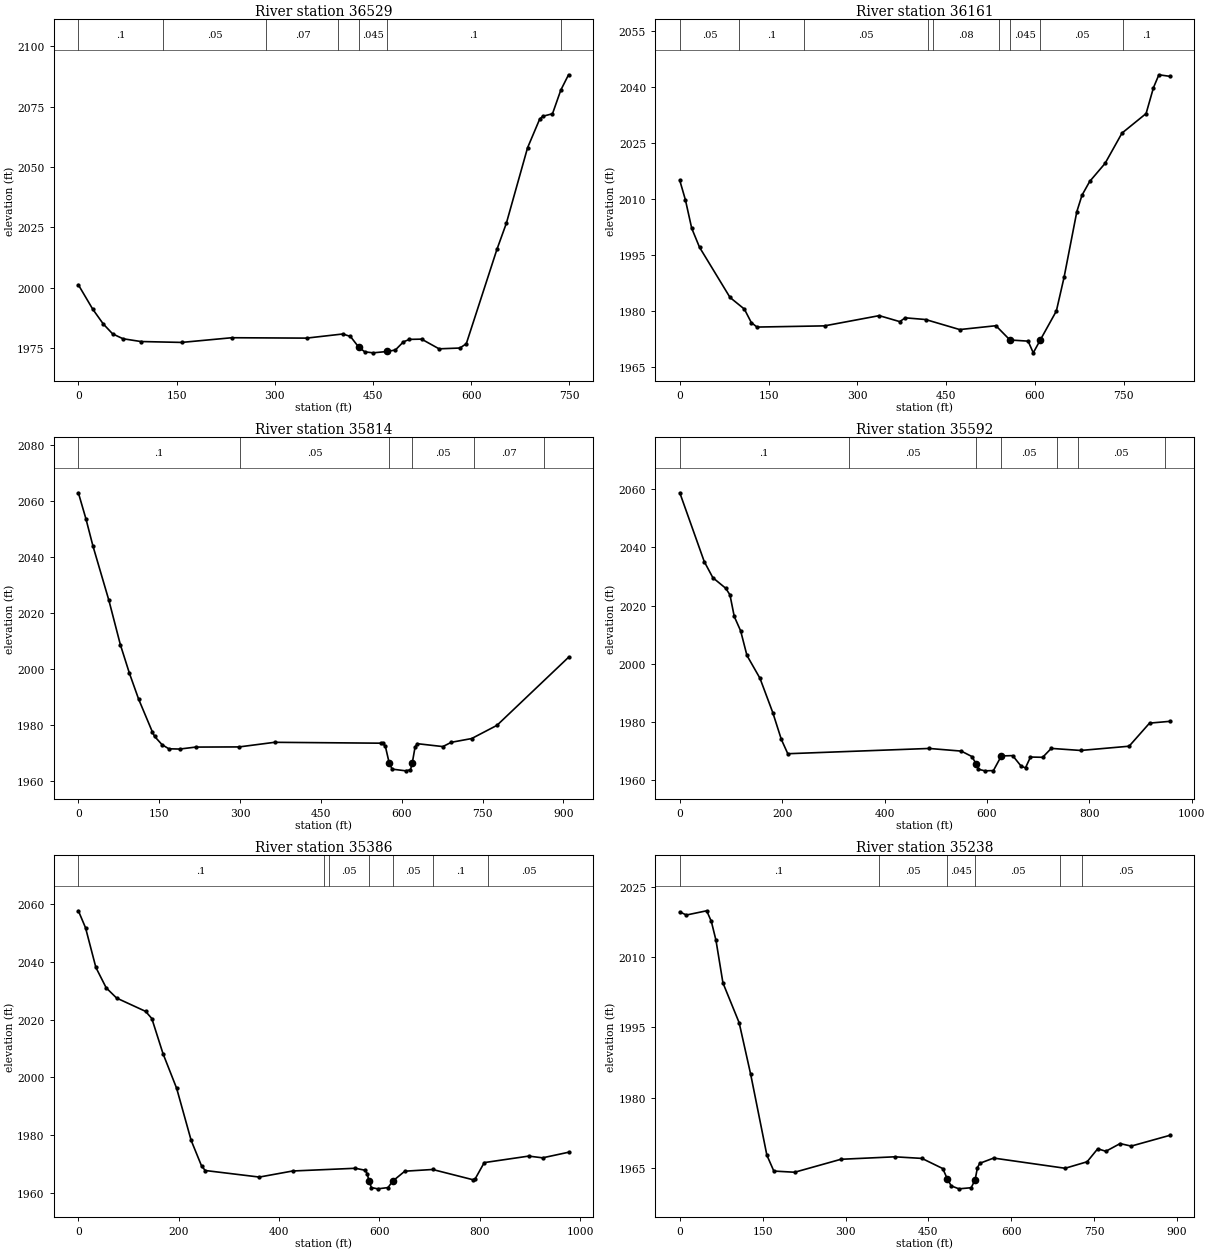
Type RM Length L Ch R = 1 ,36529   ,328.2,368.2,367.7
XS GIS Cut Line= 3
2214504.37940439671683.884277919 2214702.6670553671553.300792342
2214959.53821185671110.974999814
#Sta/Elev= 30
       0 2001.24      22 1991.15    38.1 1985.03    52.4 1980.94    68.2 1978.93
    95.5 1977.78   157.8 1977.41   234.4 1979.35   348.6 1979.19   404.1  1980.9
   415.7 1979.87   428.61975.364   437.6 1973.52   450.3  1973.1   472.31973.673
   484.4 1974.29   496.6 1977.64   505.8 1978.67   524.4 1978.77   551.1 1974.76
   582.9 1975.09   592.7 1976.86   639.5 2015.89   653.9  2026.7   686.3 2057.93
   704.7 2069.71   709.4 2070.95   724.4 2072.01   737.1 2081.79   748.9 2088.13
#Mann= 7 ,-1,0
       0      .1       0     130     .05       0  287.42     .07       0
  397.42     .05       0   428.6    .045       0   472.3      .1       0
  737.42     .06       0
Bank Sta=428.6,472.3
XS Rating Curve= 0 ,0
Exp/Cntr(USF)=0,0
Exp/Cntr=0.3,0.1

Type RM Length L Ch R = 1 ,36161   ,344.5,347.1,347.4
XS GIS Cut Line= 3
 2214513.9046605 671783.505203342214839.88221607671634.129510063
2215273.39451672671454.153351774
#Sta/Elev= 30
       0 2015.05     9.5 2009.84    20.1 2002.27    33.3 1997.17    84.9 1983.72
   109.1 1980.61   120.8 1977.01   130.4  1975.8   244.5 1976.12   336.9 1978.86
   371.5 1977.26   380.9 1978.27   415.2 1977.82   472.8 1975.13     534 1976.16
   557.71972.343   588.4 1972.03   597.1  1968.9     6091972.351   636.1 1980.09
   649.1 1989.09   670.7 2006.71   679.4 2011.09   692.4 2014.78   718.4 2019.62
     747 2027.73   787.7 2032.96   800.2 2039.92   809.3 2043.34     828 2042.92
#Mann= 9 ,-1,0
       0     .05       0     100      .1       0     210     .05       0
  418.57     .06       0  428.57     .08       0  538.57     .05       0
   557.7    .045       0     609     .05       0  748.57      .1       0
Bank Sta=557.7,609
XS Rating Curve= 0 ,0
Exp/Cntr(USF)=0,0
Exp/Cntr=0.3,0.1

Type RM Length L Ch R = 1 ,35814   ,220.8,221.5,223
XS GIS Cut Line= 3
2214618.70687082 672061.689585362215292.86719472671825.144980412
2215413.97116426671672.340602678
#Sta/Elev= 30
       0 2062.81    14.1 2053.49      27 2043.89    56.7 2024.45    77.9 2008.72
    94.8 1998.49   111.8 1989.32   137.2 1977.69   141.4 1976.05   155.3 1973.09
   167.9 1971.63   188.1 1971.54   217.7 1972.24   298.3  1972.3     364 1973.94
   561.1 1973.63   565.4 1973.54   569.6 1972.48   576.81966.488   582.3 1964.38
   607.7 1963.78   616.2 1964.18   619.41966.483   624.7 1972.27   628.9 1973.45
   676.2 1972.42   691.9 1973.94   729.7 1975.28   776.6 1979.98   909.4 2004.22
#Mann= 6 ,-1,0
       0      .1       0     300     .05       0   576.8    .045       0
   619.4     .05       0  734.45     .07       0  864.45     .05       0
Bank Sta=576.8,619.4
XS Rating Curve= 0 ,0
Exp/Cntr(USF)=0,0
Exp/Cntr=0.3,0.1

Type RM Length L Ch R = 1 ,35592   ,205.3,206.1,207.7
XS GIS Cut Line= 3
2214686.46604785 672247.436145542215391.63534867672030.975948768
2215568.21106709671899.844070275
#Sta/Elev= 30
       0 2058.73    47.8 2035.08    64.6 2029.56    89.7 2025.93      98 2023.67
   106.4 2016.24   118.9 2011.29   131.2 2002.85   156.6 1995.02   181.7 1983.21
   198.4    1974     211 1969.09   487.2  1970.9   549.9 1969.99   570.8 1968.11
   579.41965.434   583.4 1963.76   595.9 1963.21   612.7  1963.3   628.21968.327
   650.3 1968.44   667.1 1964.77   675.4 1964.25   685.1 1967.95   708.9 1967.86
   725.7 1970.92   783.2 1970.21   877.8 1971.67   917.7  1979.6   957.6 1980.22
#Mann= 7 ,-1,0
       0      .1       0     330     .05       0   579.4    .045       0
   628.2     .05       0  737.64      .1       0  777.64     .05       0
  947.64     .06       0
Bank Sta=579.4,628.2
XS Rating Curve= 0 ,0
Exp/Cntr(USF)=0,0
Exp/Cntr=0.3,0.1

Type RM Length L Ch R = 1 ,35386   ,149.4,148.5,147.1
XS GIS Cut Line= 3
2214714.36824349672423.0170455222215370.23034516672255.117634984
2215638.32346194672120.838094044
#Sta/Elev= 30
       0 2057.62    14.3 2051.74    34.9 2038.03    55.5 2030.97    76.2 2027.45
     134 2022.84   146.4 2020.37   168.7 2008.22   195.9 1996.23   224.8 1978.23
   245.5 1969.41   252.8 1967.82   360.7 1965.55   427.1 1967.65     552 1968.59
   571.7  1967.9   575.8 1966.68   579.11964.205   584.1 1961.92   596.4 1961.48
   617.1 1961.91   626.61964.161   650.6 1967.58     706 1968.17   786.6 1964.62
     791 1964.98   808.9 1970.55   897.5  1972.8   925.2  1972.2   976.9 1974.13
#Mann= 7 ,-1,0
       0      .1       0     490     .06       0     500     .05       0
   579.1    .045       0   626.6     .05       0  707.01      .1       0
  817.01     .05       0
Bank Sta=579.1,626.6
XS Rating Curve= 0 ,0
Exp/Cntr(USF)=0,0
Exp/Cntr=0.3,0.1

Type RM Length L Ch R = 1 ,35238   ,197,197.4,198.6
XS GIS Cut Line= 3
2214857.62778707672565.4606694962215400.31424362672397.085065352
2215656.67501421672207.487775705
#Sta/Elev= 30
       0 2019.72    11.8 2019.04    48.7 2019.95    57.1 2017.67    65.5 2013.63
    78.1 2004.52   107.4 1996.02   128.3 1984.97   157.6 1967.68   170.2 1964.28
   207.9 1964.03   291.6  1966.8     389 1967.33   438.2 1966.99   475.9 1964.82
   484.51962.523   491.3 1961.11   505.2 1960.48   527.4 1960.72   534.6 1962.47
   538.7 1965.02   542.9 1965.94     568 1967.06   697.4 1964.88   737.2 1966.27
   756.4 1969.05   771.1 1968.51   796.9 1970.16   816.9 1969.62   887.1 1971.93
#Mann= 6 ,-1,0
       0      .1       0     360     .05       0   484.5    .045       0
   534.6     .05       0  688.21      .1       0  728.21     .05       0
Bank Sta=484.5,534.6
XS Rating Curve= 0 ,0
Exp/Cntr(USF)=0,0
Exp/Cntr=0.3,0.1

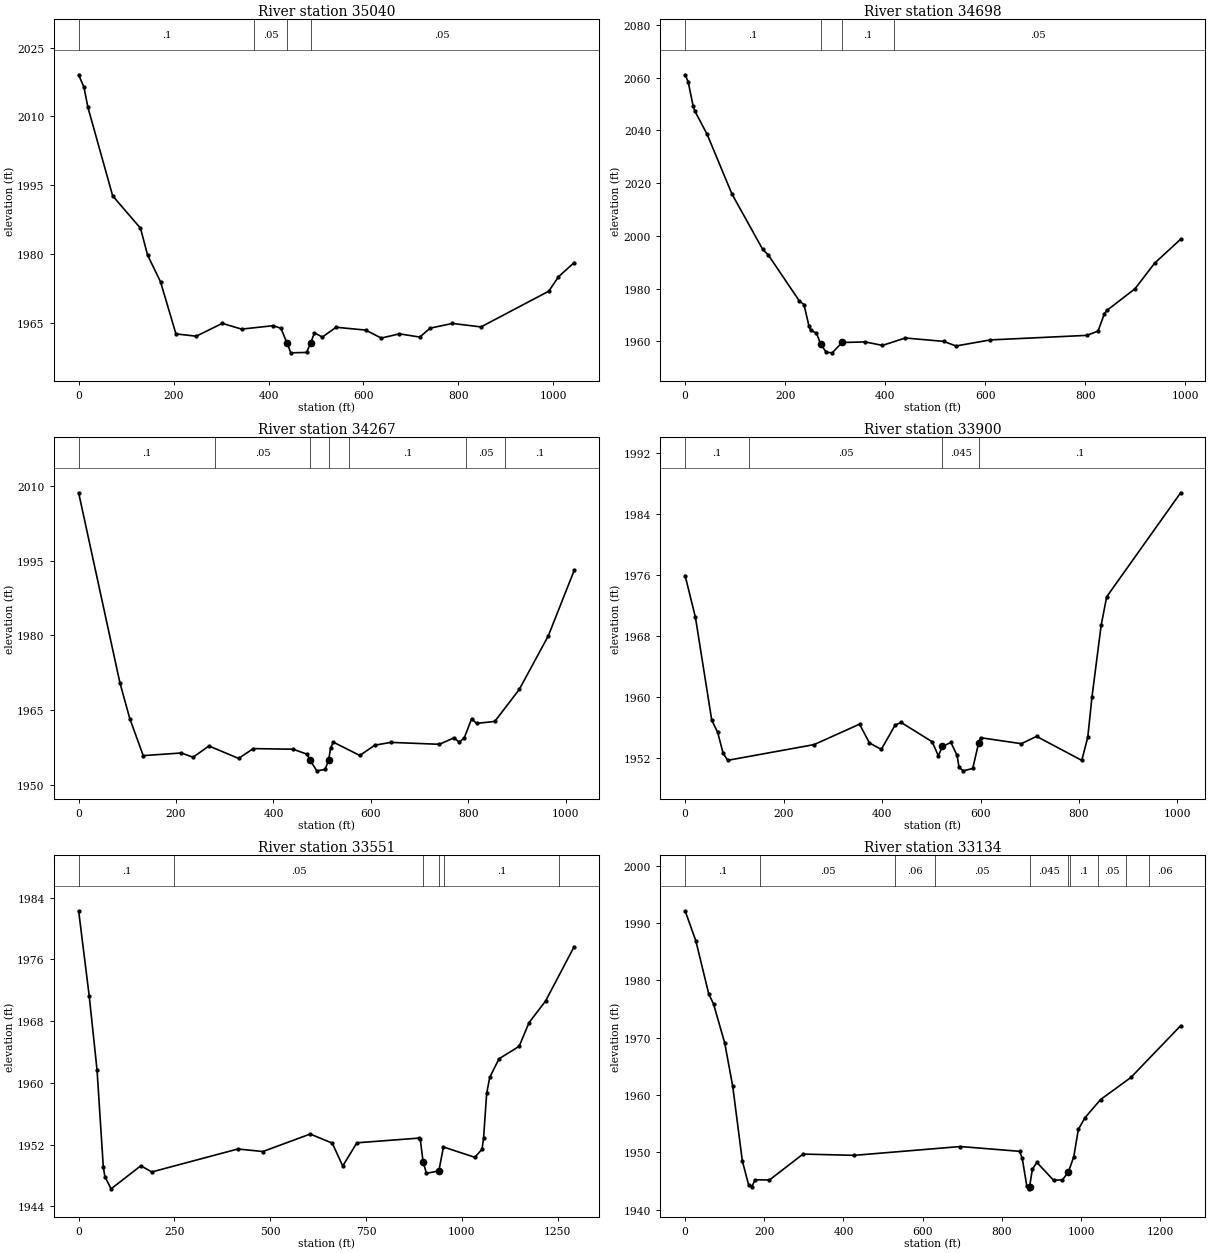
Type RM Length L Ch R = 1 ,35040   ,347.9,341.8,332.7
XS GIS Cut Line= 3
 2214941.3707641672730.6247032732215578.63009154672554.489494098
2215934.97450784672414.706382695
#Sta/Elev= 30
       0 2019.06    11.2 2016.36    19.5 2011.98    71.7 1992.65   130.3  1985.6
   145.3 1979.73   172.5 1973.91     205 1962.55   247.8 1962.05   302.6 1964.85
   343.2 1963.59   409.6 1964.34   426.2 1963.78   439.21960.492     447 1958.42
   480.2 1958.51   488.5 1960.52   496.8 1962.77   513.4 1961.86   542.4    1964
   604.7 1963.38   637.5 1961.64   675.7 1962.56   718.7 1961.86   740.5  1963.8
   787.4 1964.83   847.6 1964.07   990.5 1971.87  1010.8    1975  1043.9 1978.11
#Mann= 4 ,-1,0
       0      .1       0     370     .05       0   439.2    .045       0
   488.5     .05       0
Bank Sta=439.2,488.5
XS Rating Curve= 0 ,0
Exp/Cntr(USF)=0,0
Exp/Cntr=0.3,0.1

Type RM Length L Ch R = 1 ,34698   ,434,431,420.3
XS GIS Cut Line= 4
 2215241.2005565673076.0170147512215407.53110772672988.299649975
2215832.68512775672687.2906037952216092.01339489672576.741789207
#Sta/Elev= 30
       0 2061.07     6.1 2058.45    16.1 2049.18    19.1 2047.45    44.1 2038.49
    93.8 2015.82   155.3 1994.84   166.2  1992.8     228 1975.44   237.8 1973.92
   247.6 1965.89     251 1964.23   262.7 1963.11   270.81959.096     282 1955.88
     294 1955.65   314.1 1959.57     360 1959.79   394.7 1958.47   440.4 1961.28
   517.2 1959.99   541.7 1958.25   610.3 1960.55   804.1 1962.28   825.8 1963.94
   838.2 1970.36   843.2 1971.71   899.7 1979.95   938.8 1989.62   990.9 1998.74
#Mann= 4 ,-1,0
       0      .1       0   270.8    .045       0   314.1      .1       0
  418.04     .05       0
Bank Sta=270.8,314.1
XS Rating Curve= 0 ,0
Exp/Cntr(USF)=0,0
Exp/Cntr=0.3,0.1

Type RM Length L Ch R = 1 ,34267   ,327.7,367.2,389.7
XS GIS Cut Line= 3
  2215416.788187 673186.822166182215757.36872698673247.170794116
2216173.01550987672719.852325116
#Sta/Elev= 30
       0 2008.67    84.7 1970.48     105 1963.26   132.6 1955.81   210.6 1956.34
     235 1955.49   267.5 1957.75   328.4 1955.25   358.6 1957.22   440.1  1957.1
   468.9  1956.1     4751954.923   488.9 1952.75     506 1953.03   513.31954.939
   517.3 1957.38     523 1958.51   577.2 1955.84   608.2 1957.92   641.2 1958.47
   740.6 1958.09   770.4 1959.38   781.3 1958.54   791.5 1959.34   806.8 1963.21
     817 1962.29   854.4 1962.69   904.7 1969.14   964.3 1979.92  1017.3 1993.05
#Mann= 7 ,-1,0
       0      .1       0     280     .05       0     475    .045       0
   513.3     .05       0  555.89      .1       0  795.89     .05       0
  875.89      .1       0
Bank Sta=475,513.3
XS Rating Curve= 0 ,0
Exp/Cntr(USF)=0,0
Exp/Cntr=0.3,0.1

Type RM Length L Ch R = 1 ,33900   ,359.1,349,343.3
XS GIS Cut Line= 4
2215353.13569249673332.1880652052215490.43099166673397.076165105
2215778.87316526673421.9430836132216315.18145335673600.046494531
#Sta/Elev= 30
       0 1975.93      21 1970.44    54.1 1956.96    66.1 1955.37    77.2 1952.62
    86.6 1951.69     262 1953.75   354.3 1956.43   374.4 1953.97   398.5 1953.12
   426.6 1956.31   438.7 1956.66   501.7 1954.13   514.4 1952.28   522.61953.505
   539.9 1954.03   552.3 1952.35   556.5 1950.76     565 1950.31   584.2 1950.62
   596.4 1954.01     600 1954.66     683 1953.87   713.9 1954.83   805.7 1951.68
   817.9 1954.73   826.3 1959.94   845.1 1969.42   856.3 1973.14  1006.5 1986.78
#Mann= 4 ,-1,0
       0      .1       0     130     .05       0   522.6    .045       0
   596.4      .1       0
Bank Sta=522.6,596.4
XS Rating Curve= 0 ,0
Exp/Cntr(USF)=0,0
Exp/Cntr=0.3,0.1

Type RM Length L Ch R = 1 ,33551   ,382.5,416.9,432.7
XS GIS Cut Line= 4
2214949.18493479673626.7338272732215678.22719325673776.608418569
2216023.67088872673818.7846837132216222.23648691673847.510431786
#Sta/Elev= 30
       0 1982.32    27.6 1971.27      48 1961.68    64.3 1949.14    68.4 1947.84
    84.7 1946.25   162.3 1949.24   190.9 1948.44   415.5 1951.42   480.8 1951.09
   604.2 1953.36   661.7 1952.18   689.1 1949.21   725.9 1952.22   887.3 1952.83
   891.3  1952.7   898.71949.776   907.4 1948.26   939.91948.579   951.8 1951.68
  1033.8 1950.34  1052.5 1951.39  1056.5 1952.82  1064.6 1958.64  1072.7 1960.72
  1096.8 1963.12  1149.4 1964.74  1175.1 1967.81  1218.1  1970.6  1292.9 1977.67
#Mann= 6 ,-1,0
       0      .1       0     250     .05       0   898.7    .045       0
   939.9     .05       0  954.29      .1       0  1252.3     .05       0
Bank Sta=898.7,939.9
XS Rating Curve= 0 ,0
Exp/Cntr(USF)=0,0
Exp/Cntr=0.3,0.1

Type RM Length L Ch R = 1 ,33134   ,358.4,340.8,324.9
XS GIS Cut Line= 3
2214873.09161555673852.5825658792215499.80678385673940.038652636
2215939.91966226674375.008049262
#Sta/Elev= 30
       0 1992.17    27.3 1986.88    59.7 1977.65    71.8  1975.9     100  1969.1
   120.3 1961.52   144.5  1948.5   160.6 1944.25   168.7 1944.01   176.8 1945.19
   213.1 1945.16   297.9 1949.68   427.2 1949.46   695.2    1951     845 1950.16
   851.6 1948.91     863 1944.13   867.7 1943.61   869.91943.889   877.1 1947.03
   888.4 1948.23   930.8  1945.1   953.1 1945.18     9681946.528   981.8 1949.24
   993.2    1954  1010.1 1956.04  1049.5 1959.21    1126 1963.06  1251.6  1972.1
#Mann= 10 ,-1,0
       0      .1       0     190     .05       0     530     .06       0
     630     .05       0   869.9    .045       0     968     .05       0
  972.79      .1       0 1042.79     .05       0 1112.79      .1       0
 1172.79     .06       0
Bank Sta=869.9,968
XS Rating Curve= 0 ,0
Exp/Cntr(USF)=0,0
Exp/Cntr=0.3,0.1

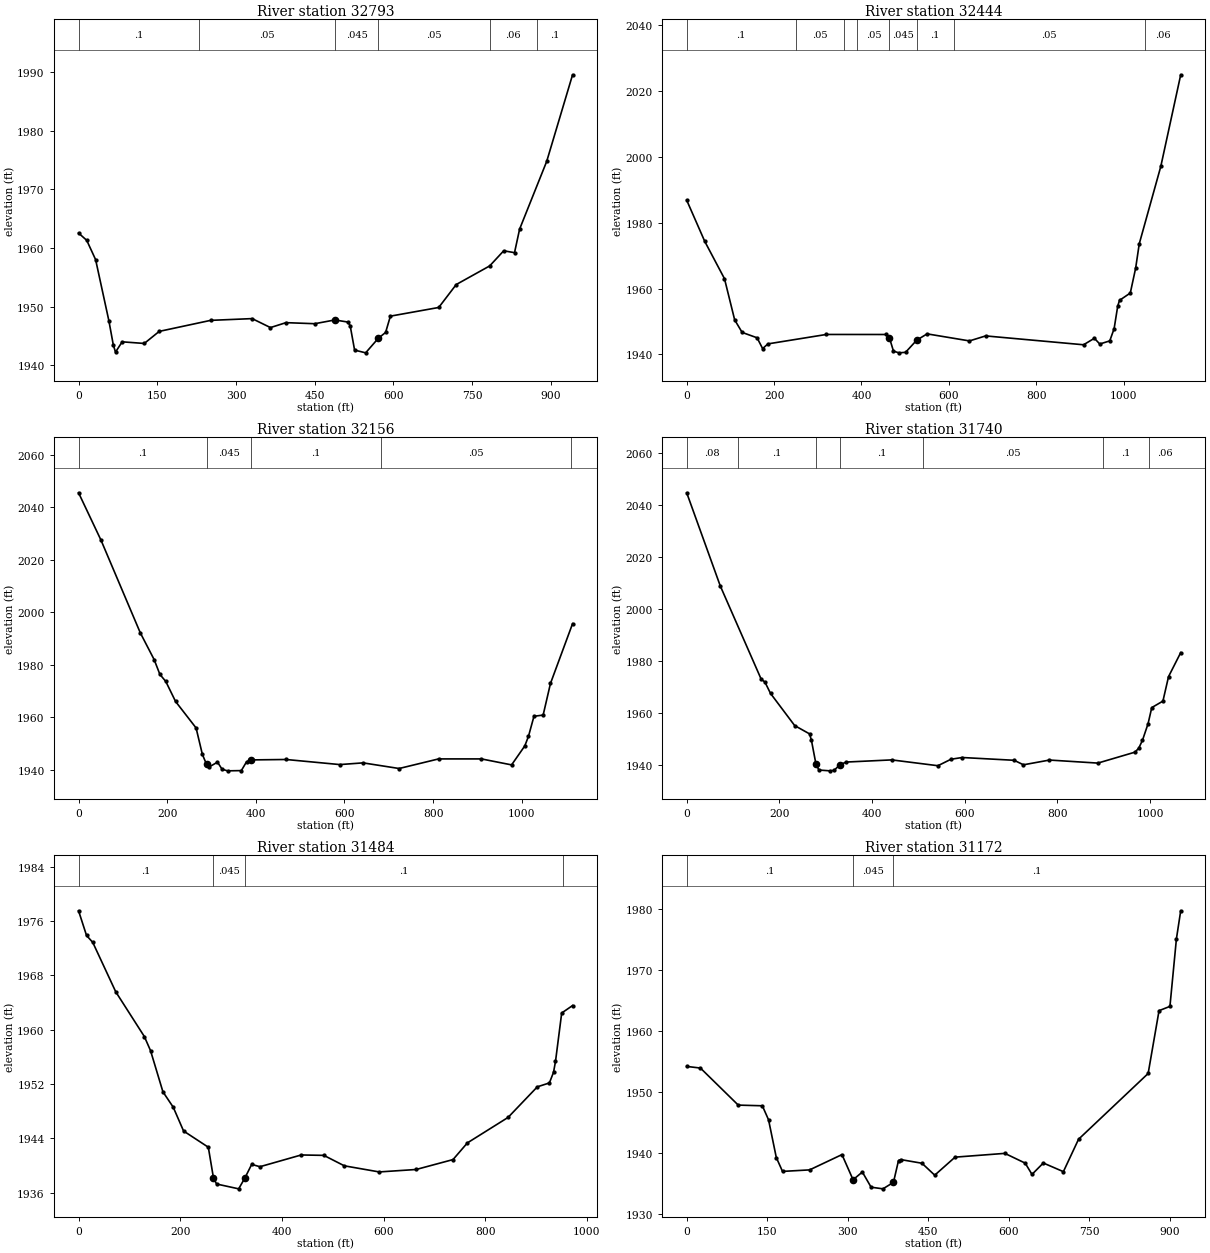
Type RM Length L Ch R = 1 ,32793   ,314.7,349.7,361.8
XS GIS Cut Line= 3
2214977.38416928674205.5284563422215663.13758854674434.725576198
2215840.75749024674561.326995496
#Sta/Elev= 30
       0 1962.56    15.6 1961.31    32.5 1958.02    57.8 1947.58    66.2 1943.47
    70.4 1942.24    83.1    1944   125.2 1943.72   153.7 1945.78   251.6 1947.66
   330.7 1947.96   365.6 1946.43   395.2 1947.27     450 1947.09   488.2 1947.73
   513.3 1947.37   517.5 1946.75   525.9 1942.59     547 1942.12   571.21944.616
     585  1945.6   594.1 1948.38   686.2 1949.86   719.5 1953.77   783.3 1956.95
     810 1959.53   830.6 1959.21   840.3 1963.23   891.9 1974.78   941.2 1989.56
#Mann= 6 ,-1,0
       0      .1       0     230     .05       0   488.2    .045       0
   571.2     .05       0  783.04     .06       0  873.04      .1       0
Bank Sta=488.2,571.2
XS Rating Curve= 0 ,0
Exp/Cntr(USF)=0,0
Exp/Cntr=0.3,0.1

Type RM Length L Ch R = 1 ,32444   ,300.1,287.3,279.6
XS GIS Cut Line= 4
2214869.34653504674308.768278204 2215132.4251536 674406.92098441
2215448.65006105674816.458159625 2215772.6509908674891.626375329
#Sta/Elev= 30
       0 1986.83    41.4  1974.3    86.5 1962.99   109.8 1950.49   126.9 1946.68
   161.1 1945.05   173.8 1941.77     186  1943.2   319.7 1946.06   455.5 1946.05
     464 1945.06   473.3    1941   485.8 1940.48     501 1940.64   526.51944.327
   550.3 1946.24   647.2  1944.1   684.3 1945.62   908.4 1942.93   933.2  1944.9
   945.5 1943.16   968.4 1944.11   978.4 1947.84   986.6 1954.66   990.7 1956.42
  1015.4 1958.64  1027.7 1966.24  1035.9 1973.59  1085.2 1997.08  1130.8 2024.91
#Mann= 8 ,-1,0
       0      .1       0     250     .05       0  360.79      .1       0
  390.79     .05       0     464    .045       0   526.5      .1       0
  610.79     .05       0 1048.21     .06       0
Bank Sta=464,526.5
XS Rating Curve= 0 ,0
Exp/Cntr(USF)=0,0
Exp/Cntr=0.3,0.1

Type RM Length L Ch R = 1 ,32156   ,444.5,416.5,395
XS GIS Cut Line= 5
2214742.30983382674583.8718651192214959.47265729674686.665147168
2215225.73742137674915.8184447512215370.97975816675039.385519341
2215692.38798015675124.365435606
#Sta/Elev= 30
       0 2045.61    50.7  2027.5   139.3 1992.17   170.6 1981.94   183.5 1976.31
   196.8 1973.62   218.9 1965.97   265.2 1955.86   279.4 1945.77   288.7 1942.01
     294 1940.91   313.5 1942.82   323.8 1940.12   336.1  1939.5   367.3 1939.59
     379 1942.94   388.41943.668   468.1 1943.83   589.5 1941.89     642 1942.54
   723.3 1940.39   812.4 1944.05     909 1944.05   977.1 1941.77  1006.9 1949.01
  1015.2 1952.67  1027.6 1960.32  1048.3 1960.78  1064.8 1972.83  1114.7 1995.67
#Mann= 5 ,-1,0
       0      .1       0   288.7    .045       0   388.4      .1       0
  681.56     .05       0 1112.25     .06       0
Bank Sta=288.7,388.4
XS Rating Curve= 0 ,0
Exp/Cntr(USF)=0,0
Exp/Cntr=0.3,0.1

Type RM Length L Ch R = 1 ,31740   ,259.6,256.2,246
XS GIS Cut Line= 3
2214595.93978236675106.2839189952215262.02389606675164.003456787
2215658.43750434675197.675655173
#Sta/Elev= 30
       0 2044.76    72.5 2008.91   160.8 1973.03   168.9 1971.93   180.9 1967.58
   233.1 1955.19   265.2    1952   269.2 1949.57   278.8 1940.58   285.3 1938.09
   309.2 1937.78     318 1937.95     3311940.156   344.4 1941.16   442.6 1941.99
   542.3 1939.75   570.4 1942.23   594.5 1942.91   706.9 1941.84   726.9  1940.1
   783.1 1941.93   887.5 1940.76   967.7 1944.97   975.8  1946.5   983.9 1949.56
   995.9  1955.9  1003.9 1962.11    1028 1964.61  1040.1 1974.02  1066.4 1983.27
#Mann= 7 ,-1,0
       0     .08       0     110      .1       0   278.8    .045       0
     331      .1       0     510     .05       0  898.58      .1       0
  998.58     .06       0
Bank Sta=278.8,331
XS Rating Curve= 0 ,0
Exp/Cntr(USF)=0,0
Exp/Cntr=0.3,0.1

Type RM Length L Ch R = 1 ,31484   ,313.1,311.9,306.1
XS GIS Cut Line= 3
2214648.69422288675430.4623063032215095.72104827675352.011696458
2215609.36411615675284.686545501
#Sta/Elev= 30
       0 1977.52    15.7 1973.88    27.9 1972.87    73.2 1965.58   129.4    1959
   141.6 1956.92     166 1950.85   186.3 1948.58   206.6 1945.08   255.3 1942.69
   265.4 1938.17   271.6 1937.27     315 1936.56   327.41938.183   340.6 1940.16
   356.9 1939.82   438.1 1941.55   482.6 1941.49   522.9 1939.95   591.5 1939.05
   664.1 1939.41   736.7 1940.87     765 1943.33     845 1947.08   902.6 1951.59
   926.3 1952.16   934.4 1953.72   938.3 1955.32   950.5 1962.46   971.9 1963.56
#Mann= 4 ,-1,0
       0      .1       0   265.4    .045       0   327.4      .1       0
  953.86     .06       0
Bank Sta=265.4,327.4
XS Rating Curve= 0 ,0
Exp/Cntr(USF)=0,0
Exp/Cntr=0.3,0.1

Type RM Length L Ch R = 1 ,31172   ,192.9,186.8,179.5
XS GIS Cut Line= 4
 2214759.2678028675823.0053415972214961.96678431675693.203608481
2215387.07675838 675551.500283792215616.05876141675514.124313642
#Sta/Elev= 30
       0 1954.21    25.6 1953.94    96.1 1947.86     141 1947.75   152.6 1945.44
     167 1939.26   178.6 1936.98   229.1 1937.23   289.4 1939.74   310.11935.614
   327.4 1936.88   343.7 1934.39   365.8 1934.12   385.41935.186   394.8 1938.77
     399 1938.92   438.5 1938.32   462.3 1936.36   500.2 1939.32     593 1939.94
   630.9 1938.34   643.6 1936.49   664.7 1938.36   702.1 1936.94   730.4 1942.26
   860.1 1953.05   880.4 1963.36   900.7 1964.06   912.8 1975.16   920.8 1979.75
#Mann= 3 ,-1,0
       0      .1       0   310.1    .045       0   385.4      .1       0
Bank Sta=310.1,385.4
XS Rating Curve= 0 ,0
Exp/Cntr(USF)=0,0
Exp/Cntr=0.3,0.1