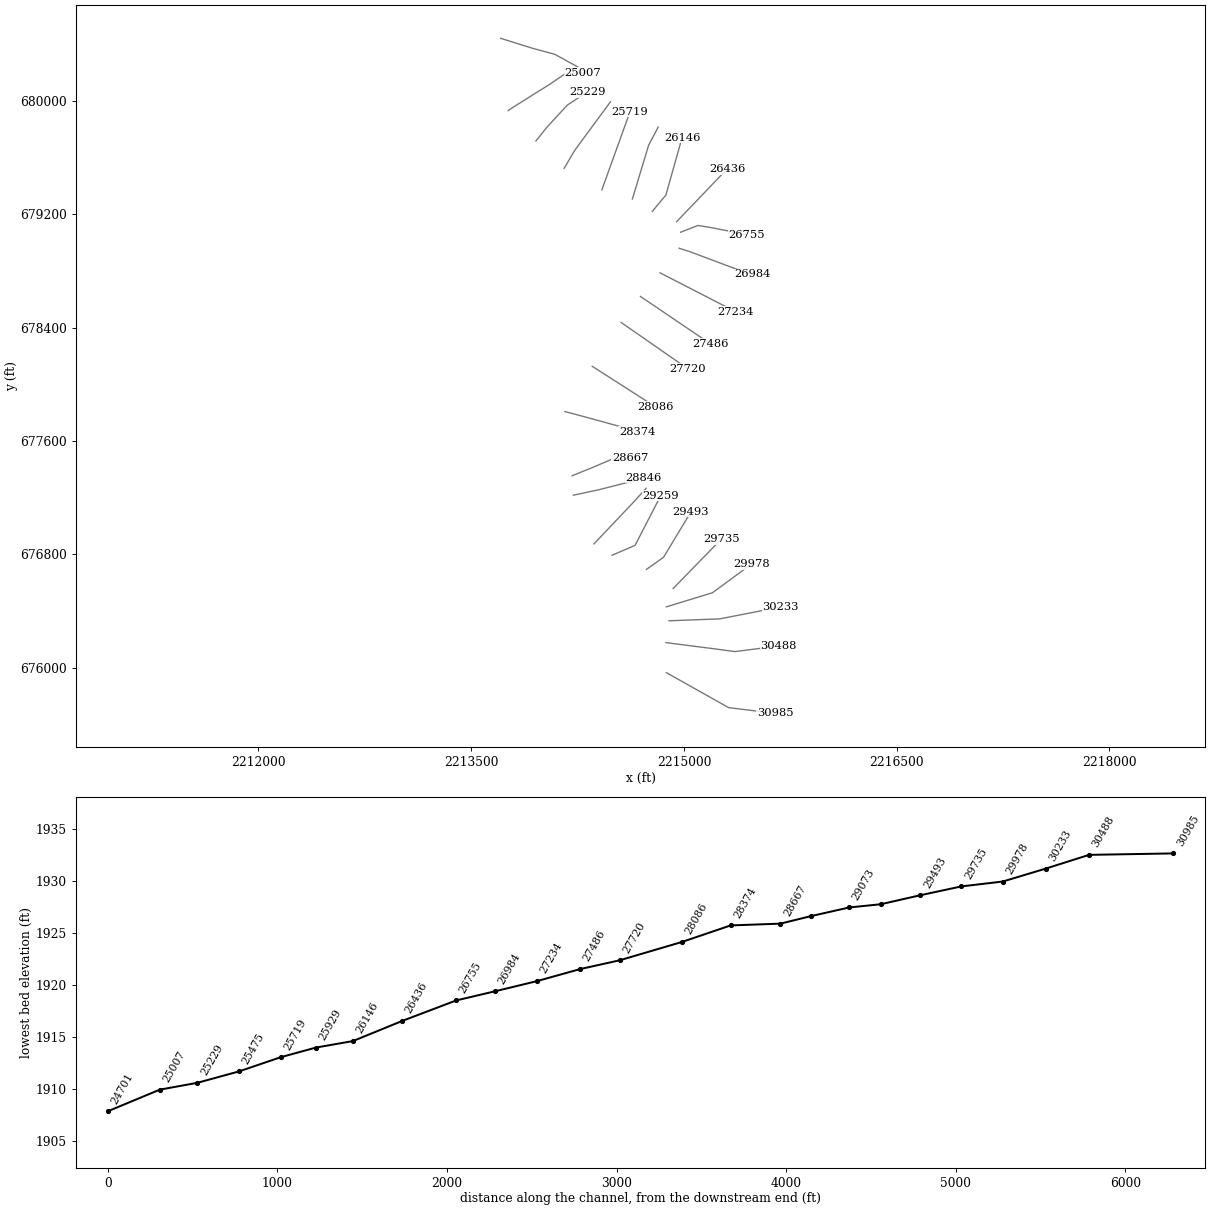
HEC-RAS study RFMIDDLERV.prj: RFMIDDLERV

--- RFMIDDLERV.g01 (geometry) --- (continued)

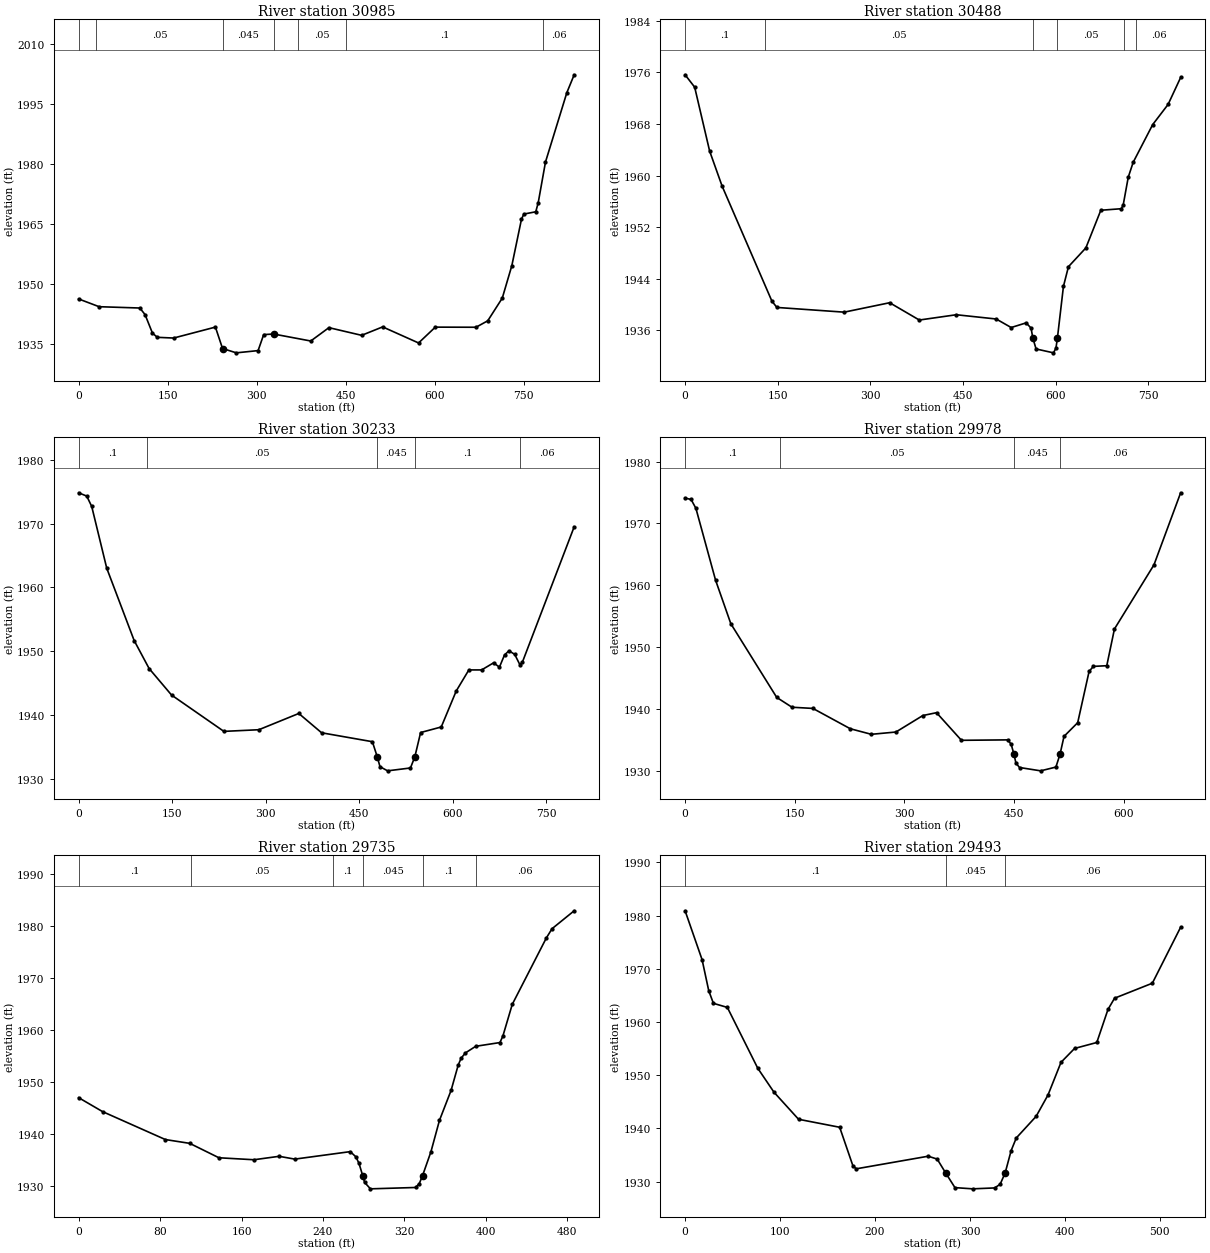
Type RM Length L Ch R = 1 ,30985   ,492.5,497.4,499.4
XS GIS Cut Line= 3
2214876.69165819675966.1019876852215315.11927043675719.570470372
2215644.37739243675679.007868079
#Sta/Elev= 30
       0 1946.16    34.5 1944.22   103.1 1943.89   111.9 1942.24   124.3 1937.63
   132.5 1936.56     160 1936.38   230.4 1939.12   242.41933.761   265.6 1932.68
   302.3 1933.24   311.7 1937.24   328.3 1937.39     391 1935.64   421.6 1938.98
   476.7 1937.06   512.1 1939.17   572.6 1935.15   600.8 1939.11   669.3 1939.08
   689.1 1940.69   713.6 1946.37   729.7 1954.49   745.9 1966.08   749.9 1967.39
     770 1967.96   774.1  1970.2   786.4 1980.42   822.4 1997.78   834.7 2002.23
#Mann= 7 ,-1,0
       0      .1       0      30     .05       0   242.4    .045       0
   328.3      .1       0     370     .05       0     450      .1       0
  782.99     .06       0
Bank Sta=242.4,328.3
XS Rating Curve= 0 ,0
Exp/Cntr(USF)=0,0
Exp/Cntr=0.3,0.1

Type RM Length L Ch R = 1 ,30488   ,253.1,254.8,255.2
XS GIS Cut Line= 4
2214872.80513597676178.311047652 2215196.6895942676136.783584548
2215359.05953677676115.0466499352215668.35214782676154.210324712
#Sta/Elev= 30
       0  1975.6    15.5 1973.68    39.7 1963.79    59.9 1958.36   140.5 1940.55
   148.6 1939.57   257.5 1938.84   331.1  1940.3   379.1 1937.62     439 1938.44
   503.6 1937.78   527.8 1936.46     552 1937.18     560 1936.37   562.81934.856
   568.1 1933.14   596.3 1932.54   600.3 1933.28   602.71934.873   612.4 1942.83
   620.5 1945.88   648.7 1948.79   672.9 1954.62   706.2 1954.86   709.2 1955.47
   717.3 1959.74   725.3 1962.05   756.9 1967.89   781.8 1971.01   802.1 1975.18
#Mann= 6 ,-1,0
       0      .1       0     130     .05       0   562.8    .045       0
   602.7     .05       0  710.35      .1       0  730.35     .06       0
Bank Sta=562.8,602.7
XS Rating Curve= 0 ,0
Exp/Cntr(USF)=0,0
Exp/Cntr=0.3,0.1

Type RM Length L Ch R = 1 ,30233   ,243.2,254.4,270.4
XS GIS Cut Line= 4
2214895.14860098676332.3492242082215252.07497526676345.678363939
2215518.62103658 676397.747827082215681.67430621676431.135405437
#Sta/Elev= 30
       0 1974.84      13 1974.32      21  1972.7    45.1 1963.01    89.1 1951.66
   113.1 1947.27   149.1 1943.11   233.1 1937.41   289.2 1937.67   353.3 1940.22
   389.9 1937.19   471.4 1935.79   479.21933.416   483.6 1931.87   495.8 1931.22
   532.5 1931.67   539.5 1933.42   548.8 1937.23   581.9  1938.1   605.9 1943.74
   626.2 1947.05   646.7 1947.05   665.8 1948.16   675.3 1947.49   683.4  1949.4
   690.6 1950.05   699.8 1949.49   707.9  1947.9     712 1948.24   795.2  1969.5
#Mann= 5 ,-1,0
       0      .1       0     110     .05       0   479.2    .045       0
   539.5      .1       0  708.76     .06       0
Bank Sta=479.2,539.5
XS Rating Curve= 0 ,0
Exp/Cntr(USF)=0,0
Exp/Cntr=0.3,0.1

Type RM Length L Ch R = 1 ,29978   ,239.6,243.8,249.6
XS GIS Cut Line= 3
2214876.31454921676430.6081938552215201.65177651676530.287569092
2215473.57513486676730.982901746
#Sta/Elev= 30
       0  1974.1     8.2 1973.88    14.8 1972.44    41.7 1960.82    62.6 1953.77
   125.4 1941.85   146.3 1940.26   174.9 1940.07   226.1 1936.78   254.9 1935.88
   288.5 1936.25   325.4 1938.92   344.1 1939.38   378.2 1934.91   441.4 1934.98
   446.2 1934.29     450 1932.69   452.8 1931.22   457.7 1930.51   486.6 1929.97
   507.5 1930.58   513.21932.689   518.6 1935.55   537.3 1937.76   552.9 1946.05
   558.7 1946.87   577.1 1946.98   587.6 1952.92   641.7  1963.3   678.2 1974.96
#Mann= 4 ,-1,0
       0      .1       0     130     .05       0     450    .045       0
   513.2     .06       0
Bank Sta=450,513.2
XS Rating Curve= 0 ,0
Exp/Cntr(USF)=0,0
Exp/Cntr=0.3,0.1

Type RM Length L Ch R = 1 ,29735   ,236.2,242.1,249.9
XS GIS Cut Line= 2
2214924.01052984676560.1236276622215263.69800593676908.725733425
#Sta/Elev= 30
       0 1947.02    23.5 1944.34    85.2 1938.97   109.1 1938.24   137.8 1935.47
   172.2 1935.09   196.9 1935.75   212.3 1935.21   266.8 1936.65   272.4 1935.63
   275.4 1934.37     2791932.037   280.9 1930.73   286.6  1929.5     331 1929.76
   334.6 1930.52   337.81932.045     346 1936.61   354.4 1942.66   365.8 1948.41
   372.8 1953.28   375.7 1954.61   379.9 1955.62     390 1956.89   413.8 1957.61
   416.7 1958.87   425.9 1964.95   459.4 1977.72     465 1979.49   486.7 1982.93
#Mann= 6 ,-1,0
       0      .1       0     110     .05       0     250      .1       0
     279    .045       0   337.8      .1       0     390     .06       0
Bank Sta=279,337.8
XS Rating Curve= 0 ,0
Exp/Cntr(USF)=0,0
Exp/Cntr=0.3,0.1

Type RM Length L Ch R = 1 ,29493   ,227.4,233.9,231.1
XS GIS Cut Line= 3
2214735.89343794676694.8301428172214856.49821295 676780.50354783
2215049.49113144677100.852169155
#Sta/Elev= 30
       0  1980.9    17.9 1971.71    24.9 1965.88    29.8 1963.51    44.5 1962.74
    76.5 1951.32    93.6 1946.81   119.5 1941.72   162.8 1940.22   176.7    1933
   180.2 1932.41     256 1934.78   265.5 1934.24   274.51931.615   284.2 1928.88
   302.8 1928.65     326 1928.82   331.8 1929.51   337.11931.651   343.4 1935.84
   348.8 1938.21   369.7 1942.27   382.2 1946.28   395.9 1952.42   410.2 1955.03
   433.6 1956.15   445.4 1962.37   452.3 1964.47   492.1 1967.29   521.9 1977.81
#Mann= 3 ,-1,0
       0      .1       0   274.5    .045       0   337.1     .06       0
Bank Sta=274.5,337.1
XS Rating Curve= 0 ,0
Exp/Cntr(USF)=0,0
Exp/Cntr=0.3,0.1

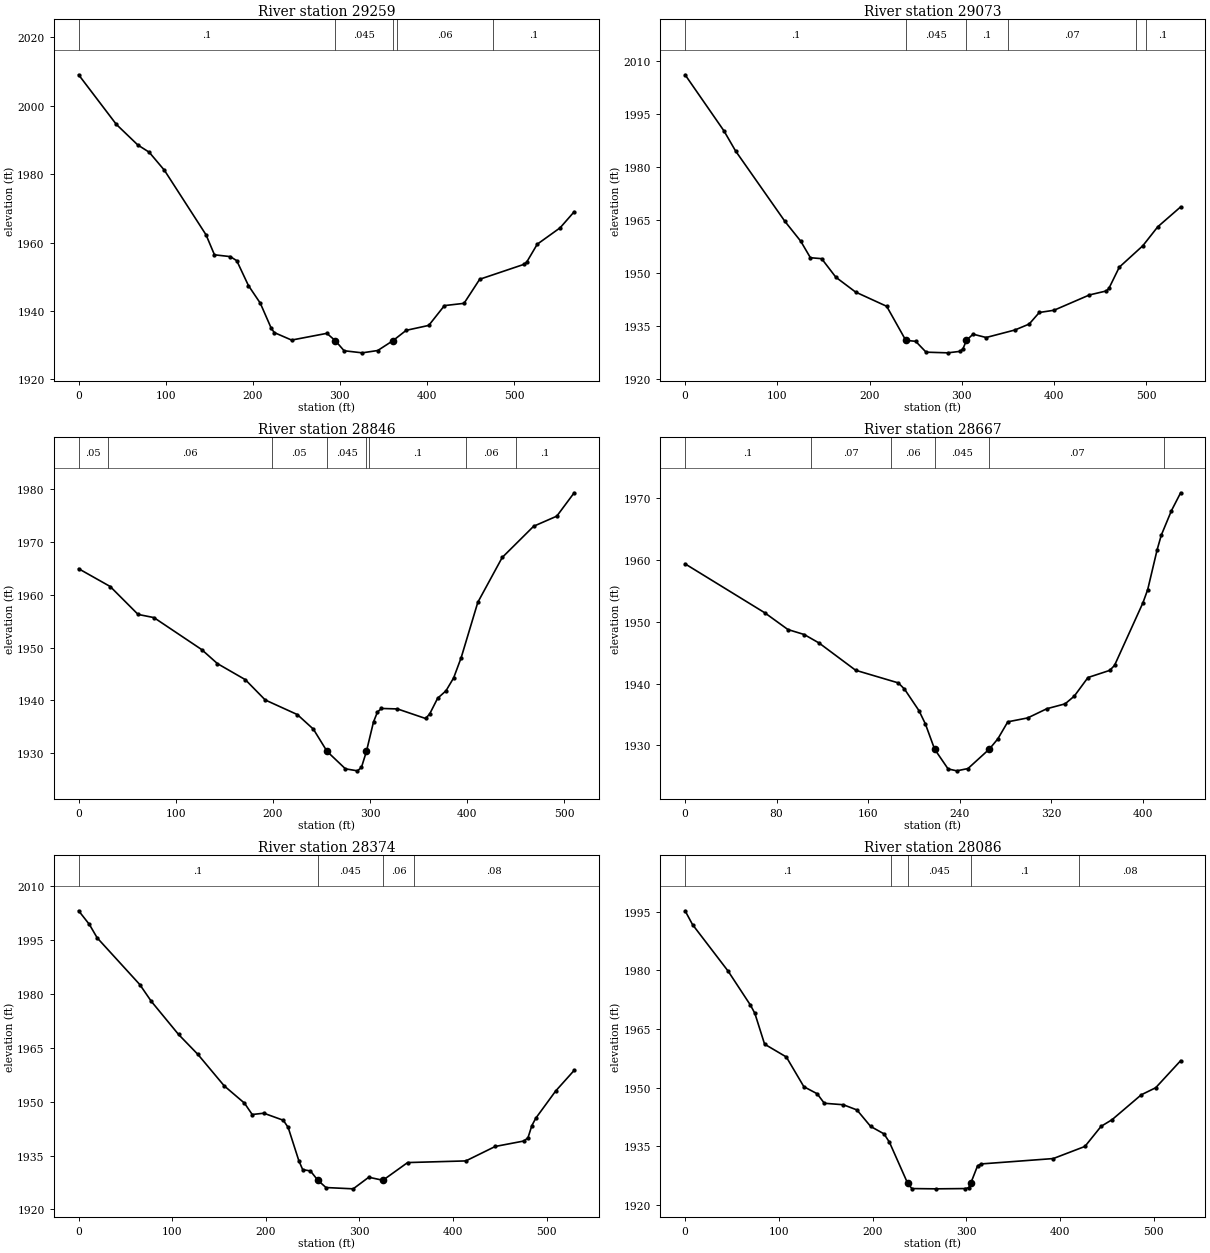
Type RM Length L Ch R = 1 ,29259   ,197.2,185.8,179.3
XS GIS Cut Line= 3
2214493.72741762 676794.723157092214655.42454254676864.251080547
2214835.59225191677213.622527624
#Sta/Elev= 30
       0 2009.07    43.3 1994.57      68 1988.54      81 1986.44    98.5 1981.16
   146.3 1962.29     156 1956.44   174.2 1955.91   181.6 1954.72     195 1947.45
   208.6 1942.31   221.3 1934.91   224.8 1933.69   244.6 1931.51   285.1 1933.48
   294.91931.299   304.9 1928.39   325.7 1927.78   343.5 1928.46   360.81931.305
   376.2 1934.36   402.1  1935.8   420.1 1941.59   442.6 1942.25   460.6 1949.29
     511 1953.61   514.6 1954.31   526.7 1959.54   552.9 1964.32   569.1 1969.02
#Mann= 5 ,-1,0
       0      .1       0   294.9    .045       0   360.8      .1       0
  366.01     .06       0  476.01      .1       0
Bank Sta=294.9,360.8
XS Rating Curve= 0 ,0
Exp/Cntr(USF)=0,0
Exp/Cntr=0.3,0.1

Type RM Length L Ch R = 1 ,29073   ,249,226.9,213
XS GIS Cut Line= 3
2214365.44073326676874.6501267972214647.06275612677171.577694386
2214732.77380656677266.472071657
#Sta/Elev= 30
       0 2006.16    42.1 1990.29    54.7 1984.61   108.2 1964.67   125.4 1959.04
   135.8 1954.39     148 1954.12   163.4 1948.87   184.8 1944.67   218.5 1940.64
   239.21931.006   249.9 1930.73   261.2 1927.66   284.6 1927.47     298 1927.89
   301.2 1928.63     3051931.028   312.1 1932.75   326.3 1931.81   357.4 1933.93
   372.9 1935.61   383.9 1938.89   399.8 1939.52   438.3 1943.86   456.5 1944.98
   459.3 1945.68   470.6 1951.71   496.1 1957.77   512.3 1963.14   537.1 1968.77
#Mann= 6 ,-1,0
       0      .1       0   239.2    .045       0     305      .1       0
     350     .07       0  489.24     .06       0  499.24      .1       0
Bank Sta=239.2,305
XS Rating Curve= 0 ,0
Exp/Cntr(USF)=0,0
Exp/Cntr=0.3,0.1

Type RM Length L Ch R = 1 ,28846   ,174.2,178.8,181.2
XS GIS Cut Line= 4
2214220.35645153677218.4419496212214395.16107779677255.634423293
2214609.63767596677310.1833846792214715.01635137677342.416861861
#Sta/Elev= 30
       0 1964.93    32.5 1961.56    61.2 1956.27    77.5 1955.67   126.6 1949.62
   142.9 1946.95   171.6 1943.91   192.1 1940.06   225.2 1937.29   241.7 1934.53
   255.81930.309   274.7 1927.01   287.1 1926.63   291.2 1927.29   296.31930.307
   303.6  1935.9   307.7 1937.79   311.8 1938.45   328.3 1938.36   357.2 1936.55
   361.4  1937.4   369.6 1940.38   378.2 1941.79   386.1 1944.24   393.9  1948.1
     411 1958.57   436.1 1967.06   468.5 1972.98   492.3 1974.89   510.2 1979.32
#Mann= 8 ,-1,0
       0     .05       0      30     .06       0  198.72     .05       0
   255.8    .045       0   296.3     .05       0  298.72      .1       0
  398.72     .06       0  450.02      .1       0
Bank Sta=255.8,296.3
XS Rating Curve= 0 ,0
Exp/Cntr(USF)=0,0
Exp/Cntr=0.3,0.1

Type RM Length L Ch R = 1 ,28667   ,308.5,293.4,270.3
XS GIS Cut Line= 4
2214211.69997047677355.3992768182214350.46916158677411.680008049
2214496.33932944677473.9416650622214621.14622863677478.386742149
#Sta/Elev= 30
       0 1959.31    69.6 1951.42    89.9 1948.71   104.1 1947.91   117.1 1946.54
   149.1 1942.14   186.4  1940.1   191.8  1939.1   204.5 1935.61   210.1 1933.46
   218.11929.416   229.9 1926.22   237.5 1925.91   247.3 1926.28     2661929.424
   273.4 1931.07   282.1 1933.82   299.5 1934.45   316.2 1935.93   332.2 1936.72
   340.2 1937.96   352.2 1940.97   371.2 1942.12   375.4 1942.92   400.2 1953.01
   404.4 1955.15   412.7 1961.62   416.3 1963.95   425.2 1967.91   433.2 1970.78
#Mann= 6 ,-1,0
       0      .1       0     110     .07       0  179.75     .06       0
   218.1    .045       0     266     .07       0  418.35     .06       0
Bank Sta=218.1,266
XS Rating Curve= 0 ,0
Exp/Cntr(USF)=0,0
Exp/Cntr=0.3,0.1

Type RM Length L Ch R = 1 ,28374   ,296.8,288,276.2
XS GIS Cut Line= 4
 2214161.0693414677808.3411101212214304.55299543677770.274018238
2214630.76104741677680.401455664 2214670.8459825677666.233505988
#Sta/Elev= 30
       0  2003.1    11.5 1999.29    19.8 1995.57    65.3 1982.58    77.7 1977.88
   106.7  1968.7   127.4 1963.14   155.5 1954.39   177.1 1949.59   185.4 1946.42
   197.8 1946.78   218.6 1944.82   223.8 1942.83   235.2 1933.57   239.3  1931.1
   247.6 1930.71   255.51928.137   264.2  1926.1   293.3 1925.74   309.9 1928.97
     3251928.123   351.4 1933.05   413.6 1933.51     445 1937.53   475.8 1939.06
     480 1939.98   484.1 1943.33   488.3 1945.39   509.5 1952.95   529.3  1958.7
#Mann= 4 ,-1,0
       0      .1       0   255.5    .045       0     325     .06       0
  358.45     .08       0
Bank Sta=255.5,325
XS Rating Curve= 0 ,0
Exp/Cntr(USF)=0,0
Exp/Cntr=0.3,0.1

Type RM Length L Ch R = 1 ,28086   ,366.8,366.2,371.1
XS GIS Cut Line= 2
2214353.50571688678127.6671224052214798.57565182677842.524824251
#Sta/Elev= 30
       0 1995.23     7.9 1991.71    45.9  1979.8    69.7 1971.11    74.4 1969.02
    84.8 1961.13     108 1957.85   126.7 1950.25   140.9 1948.45   148.5 1946.02
   168.8 1945.64   183.3 1944.31   197.9  1940.1   212.2 1938.19     218 1936.05
   237.5 1925.51   241.9 1924.21   267.2 1924.14   299.1 1924.21   302.5 1924.44
   304.61925.509     312 1930.03     316 1930.51   392.7 1931.88   426.5 1934.98
   443.8 1940.13   455.4 1941.81   486.6 1948.18     502 1949.99   528.6  1956.9
#Mann= 5 ,-1,0
       0      .1       0     220     .06       0   237.5    .045       0
   304.6      .1       0     420     .08       0
Bank Sta=237.5,304.6
XS Rating Curve= 0 ,0
Exp/Cntr(USF)=0,0
Exp/Cntr=0.3,0.1

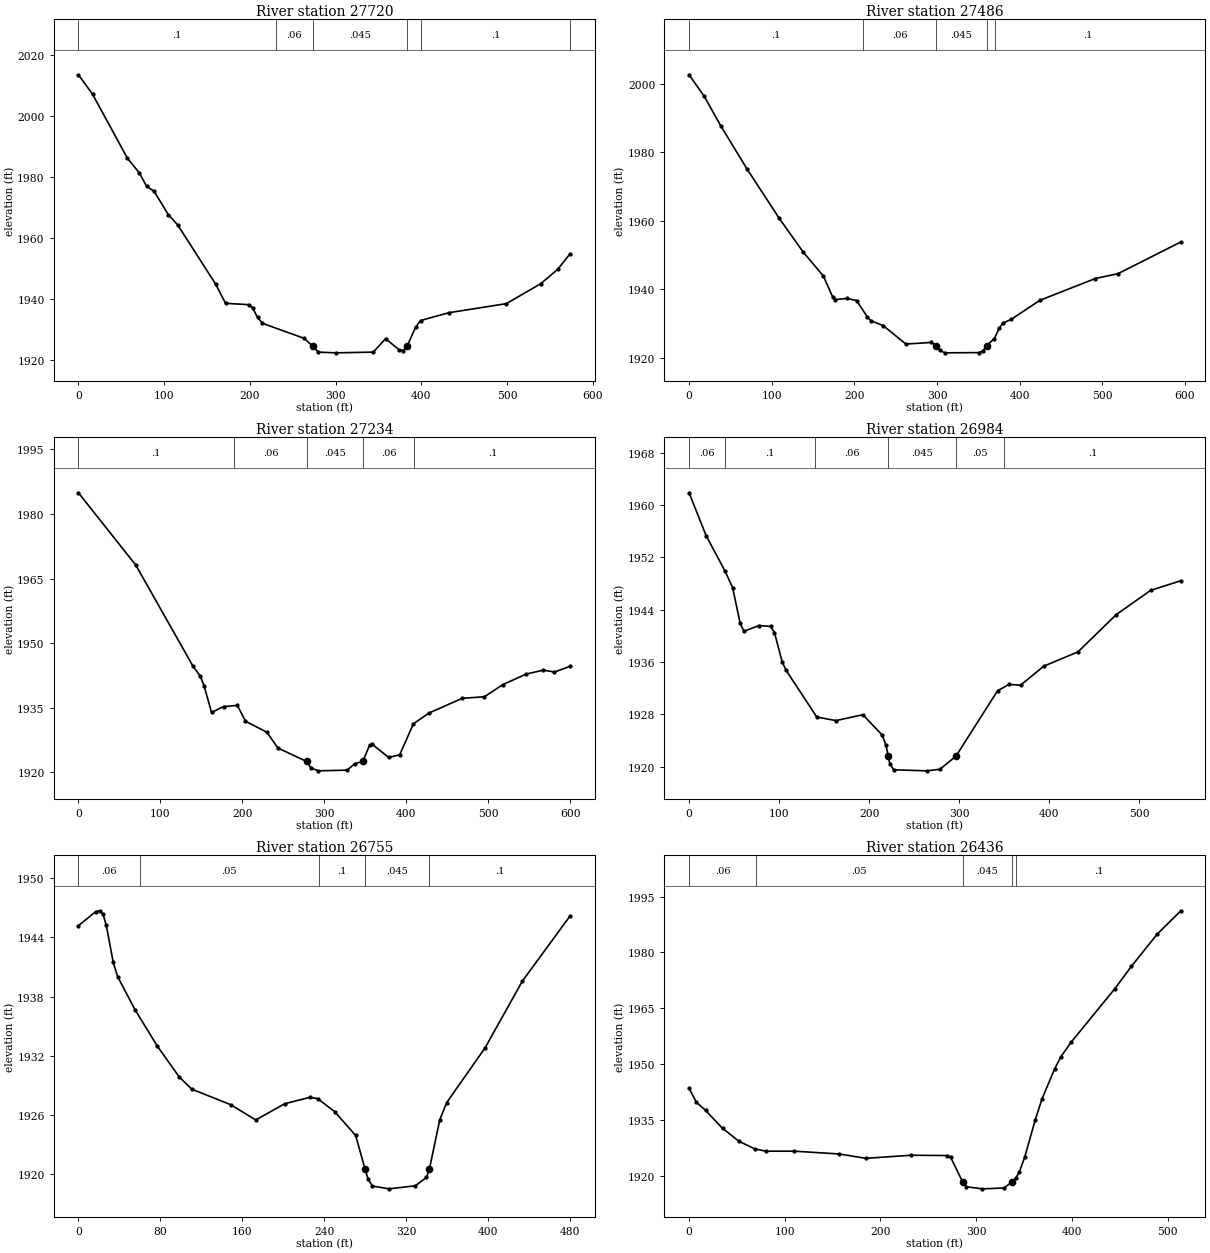
Type RM Length L Ch R = 1 ,27720   ,235.4,233.8,234.5
XS GIS Cut Line= 2
2214557.28691725678437.1105814672215028.17548868678109.452503818
#Sta/Elev= 30
       0 2013.55    16.4 2007.21    57.1  1986.2      71 1981.39    79.6 1976.94
    88.2 1975.37   104.9 1967.67   115.6 1964.38   160.1  1944.9   171.6 1938.62
   198.4 1938.18   203.2 1937.18   208.9 1933.97   214.7 1932.05   263.5 1927.12
   273.41924.505     280  1922.6   300.8 1922.38     344 1922.62   358.3 1927.03
   373.9 1923.42   378.7 1923.14   383.31924.482   393.4 1930.82   399.1 1932.98
   432.3 1935.54   499.2 1938.51   539.6  1945.1     559 1949.73   573.7 1954.92
#Mann= 6 ,-1,0
       0      .1       0     230     .06       0   273.4    .045       0
   383.3     .06       0     400      .1       0  573.67     .08       0
Bank Sta=273.4,383.3
XS Rating Curve= 0 ,0
Exp/Cntr(USF)=0,0
Exp/Cntr=0.3,0.1

Type RM Length L Ch R = 1 ,27486   ,249.2,252.1,257.5
XS GIS Cut Line= 2
2214693.73250042678620.3641371552215186.35940951678286.579371138
#Sta/Elev= 30
       0 2002.59    18.5 1996.27    38.6 1987.61    70.3 1975.08   109.2 1960.72
   138.2  1950.9   162.5 1943.94     174 1937.72   176.9 1937.06   191.3 1937.38
   202.8 1936.77   215.5 1932.07   220.1 1930.89   234.9 1929.48   262.4 1924.09
   292.9 1924.56   299.21923.667   303.6 1922.26   309.4 1921.53   350.8  1921.6
   355.7  1922.1   360.11923.662   369.4 1925.67   375.6 1928.83   379.8  1930.2
     390 1931.31   424.6 1936.85   491.7  1943.2   519.1 1944.61   595.1 1953.85
#Mann= 5 ,-1,0
       0      .1       0     210     .06       0   299.2    .045       0
   360.1     .06       0     370      .1       0
Bank Sta=299.2,360.1
XS Rating Curve= 0 ,0
Exp/Cntr(USF)=0,0
Exp/Cntr=0.3,0.1

Type RM Length L Ch R = 1 ,27234   ,246.7,249.6,254.9
XS GIS Cut Line= 2
2214831.77255437 678787.205684182215365.24404089678512.600197937
#Sta/Elev= 30
       0 1984.92    70.1 1968.09   139.9 1944.62   148.9 1942.29   153.3 1940.08
   162.4 1933.93     177 1935.29   193.9 1935.57   203.8 1931.89   229.9 1929.34
   243.4 1925.67   278.41922.556   283.9 1921.01   292.8 1920.38   327.8 1920.54
   337.4 1922.07   346.9 1922.55   355.2 1926.31   358.2 1926.58   378.4  1923.5
   391.9 1924.08   408.7  1931.3   427.8 1933.81   468.3 1937.22   495.3 1937.57
   517.8  1940.4   546.3 1942.84   567.3 1943.76   580.8 1943.31     600 1944.66
#Mann= 5 ,-1,0
       0      .1       0     190     .06       0   278.4    .045       0
   346.9     .06       0     410      .1       0
Bank Sta=278.4,346.9
XS Rating Curve= 0 ,0
Exp/Cntr(USF)=0,0
Exp/Cntr=0.3,0.1

Type RM Length L Ch R = 1 ,26984   ,223.5,228.8,234.3
XS GIS Cut Line= 4
 2214966.0816131678960.8137558262215041.99889036 678936.41177385
2215360.12843317678817.1131952982215479.96016751678775.619013489
#Sta/Elev= 30
       0 1961.85      19  1955.3      40 1949.88    48.4 1947.37    56.8  1941.9
      61  1940.7    77.8 1941.58    90.6 1941.44    94.9  1940.5   103.4 1936.07
   107.7 1934.76   141.9 1927.61   163.2 1927.06   193.1 1927.96   214.5 1924.86
   218.8 1923.28   221.21921.663     223 1920.48   227.3 1919.55   264.1 1919.39
   278.6 1919.62   296.61921.641   342.7 1931.62   355.5 1932.59   368.3 1932.47
   393.9 1935.36   432.1 1937.56   474.6 1943.25   512.7 1946.94   546.3 1948.42
#Mann= 6 ,-1,0
       0     .06       0      40      .1       0  139.74     .06       0
   221.2    .045       0   296.6     .05       0  349.74      .1       0
Bank Sta=221.2,296.6
XS Rating Curve= 0 ,0
Exp/Cntr(USF)=0,0
Exp/Cntr=0.3,0.1

Type RM Length L Ch R = 1 ,26755   ,288.5,319,346.8
XS GIS Cut Line= 4
2214976.47495224679073.6497338312215100.01559121 679121.53895918
2215190.93737606679106.3853283732215441.96056465679057.630168384
#Sta/Elev= 30
       0 1945.18    16.8  1946.6    21.1 1946.69    24.1 1946.32    27.2 1945.21
      34 1941.46    38.3 1940.01    55.4 1936.64    76.9    1933    98.3 1929.87
   110.7 1928.61   148.9 1927.03   173.2 1925.49   201.6 1927.14   225.9 1927.78
   233.6 1927.66   250.4 1926.32   270.8 1923.92   279.91920.543     283 1919.48
   287.1  1918.8   303.4 1918.51   329.1 1918.82     340 1919.67   342.91920.541
     353 1925.52   359.8 1927.26   397.1 1932.78   433.7 1939.57   480.4 1946.19
#Mann= 5 ,-1,0
       0     .06       0      60     .05       0  234.67      .1       0
   279.9    .045       0   342.9      .1       0
Bank Sta=279.9,342.9
XS Rating Curve= 0 ,0
Exp/Cntr(USF)=0,0
Exp/Cntr=0.3,0.1

Type RM Length L Ch R = 1 ,26436   ,274.1,290.7,298.9
XS GIS Cut Line= 3
2214948.22505582679147.649247076 2215018.4758103679221.258958271
2215303.26950071 679518.98400235
#Sta/Elev= 30
       0 1943.53     7.6  1939.8    17.3 1937.59      35 1932.76    52.1 1929.32
    68.5 1927.27    80.3 1926.64     110 1926.64     157 1925.89   184.7 1924.72
   231.5 1925.55   269.8 1925.47   273.2 1925.07   285.7 1918.46   289.8 1917.09
   306.5 1916.53   329.2 1916.75   337.7 1918.47   341.5 1919.45   345.2 1921.12
   350.7 1925.06   361.8 1935.13   368.8  1940.7     382 1948.76   388.6 1952.03
   399.3 1955.94   444.8 1970.25   462.2 1976.29   489.1 1984.92   513.8 1991.19
#Mann= 5 ,-1,0
       0     .06       0      70     .05       0   285.7    .045       0
   337.7     .05       0  341.75      .1       0
Bank Sta=285.7,337.7
XS Rating Curve= 0 ,0
Exp/Cntr(USF)=0,0
Exp/Cntr=0.3,0.1

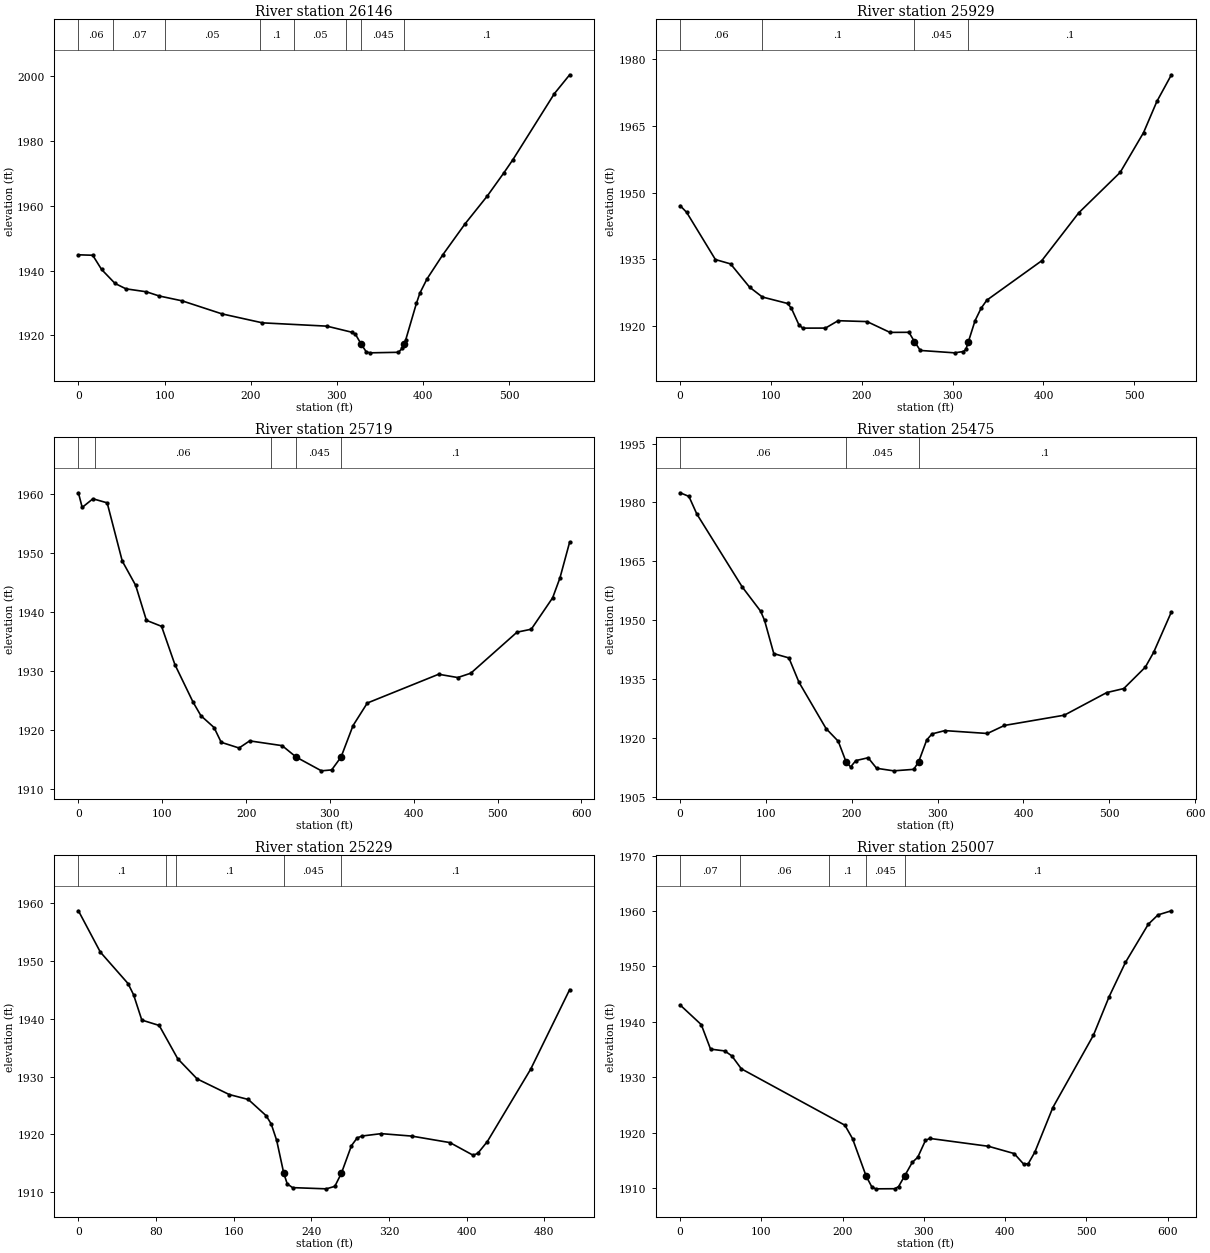
Type RM Length L Ch R = 1 ,26146   ,216.5,216.9,215.5
XS GIS Cut Line= 3
2214776.97492301679220.4258349872214872.96713766679336.417791348
2214986.75769683679740.552772356
#Sta/Elev= 30
       0 1944.89    16.6 1944.75    26.9 1940.36    42.5 1936.04    55.2 1934.37
    78.9 1933.46    93.7 1932.17   120.4 1930.66   166.7 1926.63   213.7 1923.86
   288.5 1922.84   317.6 1920.95   321.7  1920.3   328.51917.207   334.2  1914.9
   338.4 1914.59   371.6 1914.76   375.8 1915.94   377.81917.178   379.9 1918.48
   392.4 1929.84   396.5 1933.06   404.8 1937.46   422.9 1944.82   448.9 1954.45
   474.8 1963.08   494.1 1970.26   504.6 1974.34   552.6 1994.69   570.4 2000.53
#Mann= 8 ,-1,0
       0     .06       0      40     .07       0     100     .05       0
  210.56      .1       0  250.56     .05       0  310.56      .1       0
   328.5    .045       0   377.8      .1       0
Bank Sta=328.5,377.8
XS Rating Curve= 0 ,0
Exp/Cntr(USF)=0,0
Exp/Cntr=0.3,0.1

Type RM Length L Ch R = 1 ,25929   ,211.2,209.7,208.5
XS GIS Cut Line= 3
 2214636.4323352679308.0590124142214751.69487851679689.076826709
2214818.53208207679815.250763097
#Sta/Elev= 30
       0 1947.08     7.1 1945.59    38.8 1934.96    55.5 1933.98    76.4 1928.75
    90.5 1926.53   118.2 1925.08   122.4 1924.03   130.7 1920.29   134.9 1919.53
     160 1919.54   173.9  1921.2   205.8    1921     231 1918.57   251.9 1918.59
   257.9 1916.52   264.4 1914.51   302.1 1913.97   311.9 1914.27   314.6 1914.75
   317.41916.506   324.7 1921.21   331.3 1923.98   337.6 1925.81   398.1 1934.69
   438.9 1945.48   484.5 1954.57   510.2 1963.51   524.9 1970.54   540.9 1976.53
#Mann= 4 ,-1,0
       0     .06       0      90      .1       0   257.9    .045       0
   317.4      .1       0
Bank Sta=257.9,317.4
XS Rating Curve= 0 ,0
Exp/Cntr(USF)=0,0
Exp/Cntr=0.3,0.1

Type RM Length L Ch R = 1 ,25719   ,262.4,244.5,237.9
XS GIS Cut Line= 2
2214421.46397616679372.9101894052214619.94075302679924.263631675
#Sta/Elev= 30
       0 1960.27     4.5 1957.78    17.3 1959.25    34.3 1958.56    52.3 1948.67
    68.3 1944.54    81.1  1938.6    99.2 1937.58   115.1 1931.08   136.7 1924.72
   146.1  1922.4   161.8 1920.39   170.3 1917.88   191.6 1916.91   204.3 1918.12
     243 1917.31   259.81915.363   289.9 1913.03   302.1 1913.19   313.31915.375
   327.6 1920.72   344.6 1924.55   429.7 1929.44   452.5 1928.88   468.1 1929.62
   523.2 1936.59   540.2 1937.09   565.7 1942.43   574.4  1945.8     586  1951.9
#Mann= 5 ,-1,0
       0     .08       0      20     .06       0     230      .1       0
   259.8    .045       0   313.3      .1       0
Bank Sta=259.8,313.3
XS Rating Curve= 0 ,0
Exp/Cntr(USF)=0,0
Exp/Cntr=0.3,0.1

Type RM Length L Ch R = 1 ,25475   ,254.4,245.6,243.1
XS GIS Cut Line= 3
2214155.53845919679524.4275744312214230.22792175679651.552392778
2214482.03927267679993.905901338
#Sta/Elev= 30
       0 1982.46    10.2 1981.54    19.4 1977.06    72.3 1958.49    93.7 1952.33
    98.3    1950   109.1 1941.51   126.7 1940.42   138.4 1934.24     170 1922.43
   184.2  1919.2   193.31913.969   198.6 1912.66   204.7 1914.28     219    1915
   228.9 1912.32   248.8 1911.67   272.2 1912.05   277.91913.987   287.3 1919.54
   293.5 1921.08   308.4 1921.91     358 1921.18   377.9 1923.23   447.6 1925.84
     497 1931.59   516.9 1932.62     542 1938.07   551.7 1941.84   572.4 1952.14
#Mann= 3 ,-1,0
       0     .06       0   193.3    .045       0   277.9      .1       0
Bank Sta=193.3,277.9
XS Rating Curve= 0 ,0
Exp/Cntr(USF)=0,0
Exp/Cntr=0.3,0.1

Type RM Length L Ch R = 1 ,25229   ,225.7,221.9,211.4
XS GIS Cut Line= 4
2213956.42507417679717.1669517022214032.48028395679812.934056318
 2214178.7706804679971.6219439872214319.55784988680063.134826182
#Sta/Elev= 30
       0 1958.68    22.6 1951.53    51.1 1946.09    56.8 1944.16    65.3 1939.77
    83.2 1938.84   102.3 1933.08   122.3 1929.59   155.3 1926.89     175 1926.03
   193.4 1923.22   198.6 1921.79   204.2 1918.96   211.51913.275   215.1 1911.42
   220.6 1910.78   255.3 1910.57   264.1    1911   270.91913.279   281.2 1918.03
   287.1 1919.38   292.1 1919.71   311.9 1920.12   343.2  1919.7   382.7 1918.57
   406.6 1916.38   411.4 1916.72   421.2 1918.75   465.8 1931.26     506 1945.04
#Mann= 5 ,-1,0
       0      .1       0      90     .06       0     100      .1       0
   211.5    .045       0   270.9      .1       0
Bank Sta=211.5,270.9
XS Rating Curve= 0 ,0
Exp/Cntr(USF)=0,0
Exp/Cntr=0.3,0.1

Type RM Length L Ch R = 1 ,25007   ,323.4,306,285.8
XS GIS Cut Line= 5
2213761.31259051679931.9355031342213796.99068453679956.304117038
2214059.81749848680121.1907503192214163.08770501 680192.75385962
2214288.74005552 680196.85078326
#Sta/Elev= 30
       0 1943.05      26 1939.51    37.4  1935.1    54.9 1934.77    63.6 1933.88
    75.3 1931.55   202.8 1921.38   212.2 1918.96     229 1912.19   235.8  1910.3
   240.5 1909.91   264.2 1909.93   268.9 1910.32   276.21912.193   285.7 1914.67
   292.5  1915.6     302 1918.64   307.3    1919   379.6 1917.58   411.2 1916.27
   422.7  1914.4   428.5 1914.43   436.6 1916.51   458.8 1924.56   508.8 1937.61
   528.2 1944.58   548.2 1950.73   576.3 1957.61   588.3  1959.3   604.8 1960.04
#Mann= 5 ,-1,0
       0     .07       0   73.21     .06       0  183.21      .1       0
     229    .045       0   276.2      .1       0
Bank Sta=229,276.2
XS Rating Curve= 0 ,0
Exp/Cntr(USF)=0,0
Exp/Cntr=0.3,0.1

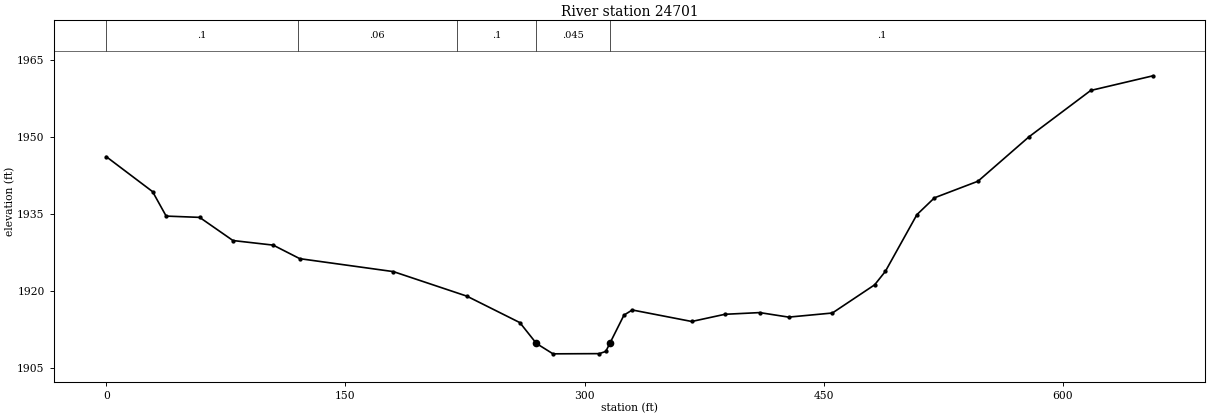
Type RM Length L Ch R = 1 ,24701   ,336,300,286.6
XS GIS Cut Line= 4
2213708.25639843680441.6862308962213931.97397972680371.828732858
2214089.62109034680328.9732076382214316.33081415680204.244288504
#Sta/Elev= 30
       0 1946.23    29.1 1939.41    37.6 1934.65    58.6  1934.4    79.5 1929.89
   104.7    1929   121.4 1926.36   180.1 1923.84   226.2 1919.06   259.4 1913.91
   269.81909.848   280.2 1907.83   309.2 1907.87   313.3  1908.3   315.81909.849
   324.7 1915.37   329.9 1916.37   367.2 1914.13     388 1915.53   409.8 1915.86
     428 1914.98   455.4 1915.78   481.9 1921.27   488.6 1923.88   508.4 1934.93
   519.4 1938.21   546.7 1941.44   578.7 1950.09   617.4 1959.11   656.5 1961.97
#Mann= 5 ,-1,0
       0      .1       0     120     .06       0     220      .1       0
   269.8    .045       0   315.8      .1       0
Bank Sta=269.8,315.8
XS Rating Curve= 0 ,0
Exp/Cntr(USF)=0,0
Exp/Cntr=0.3,0.1