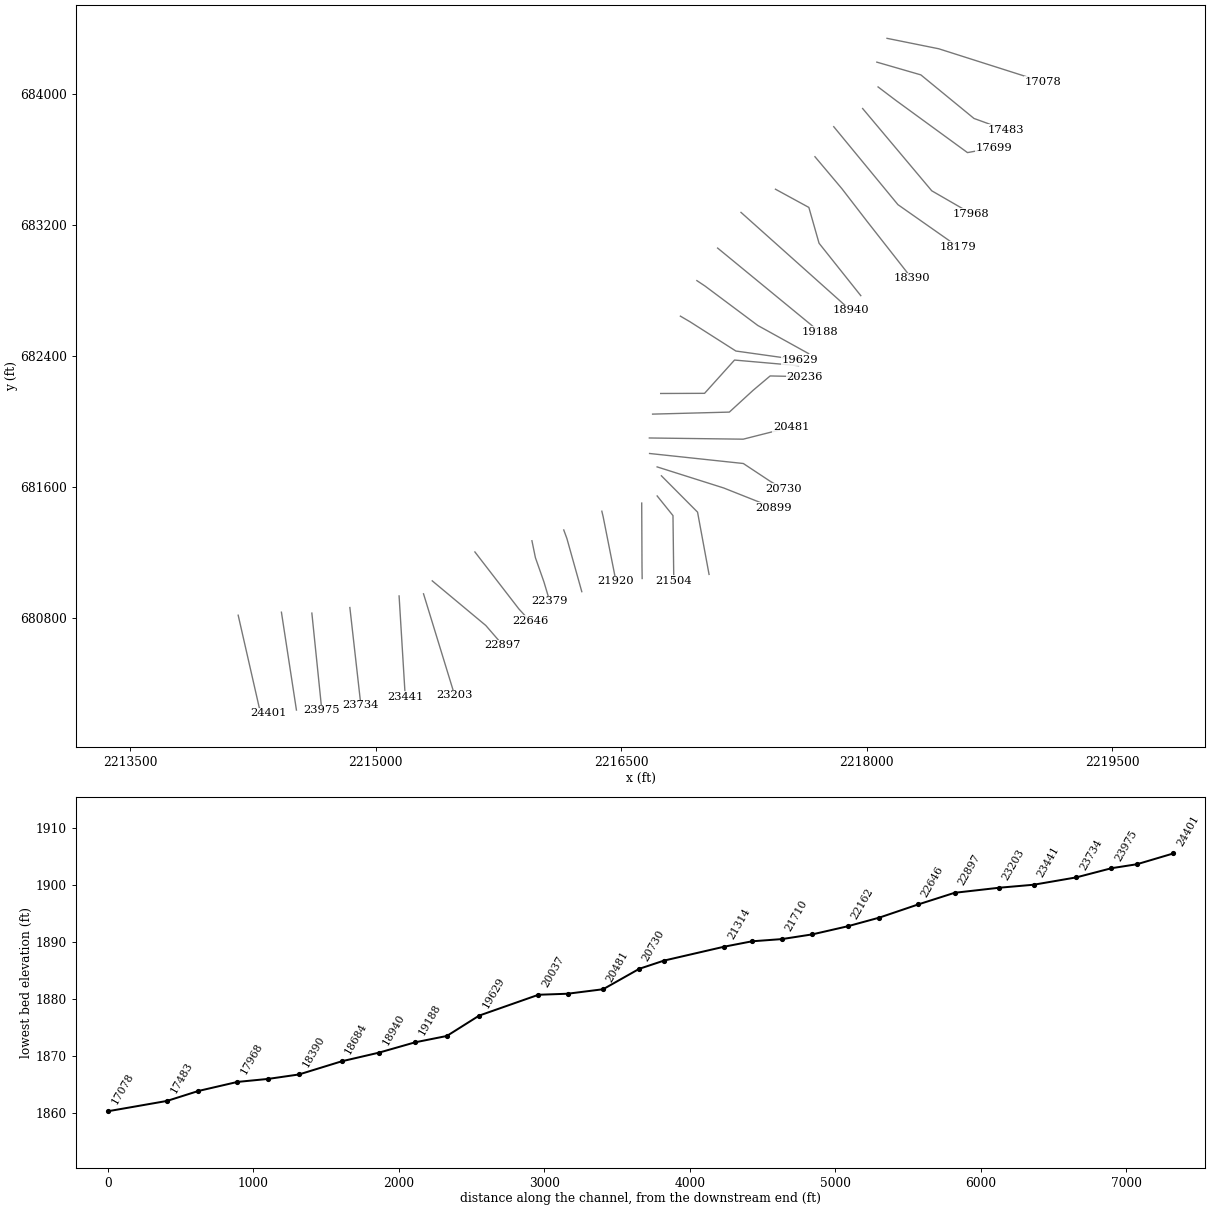
HEC-RAS study RFMIDDLERV.prj: RFMIDDLERV

--- RFMIDDLERV.g01 (geometry) --- (continued)

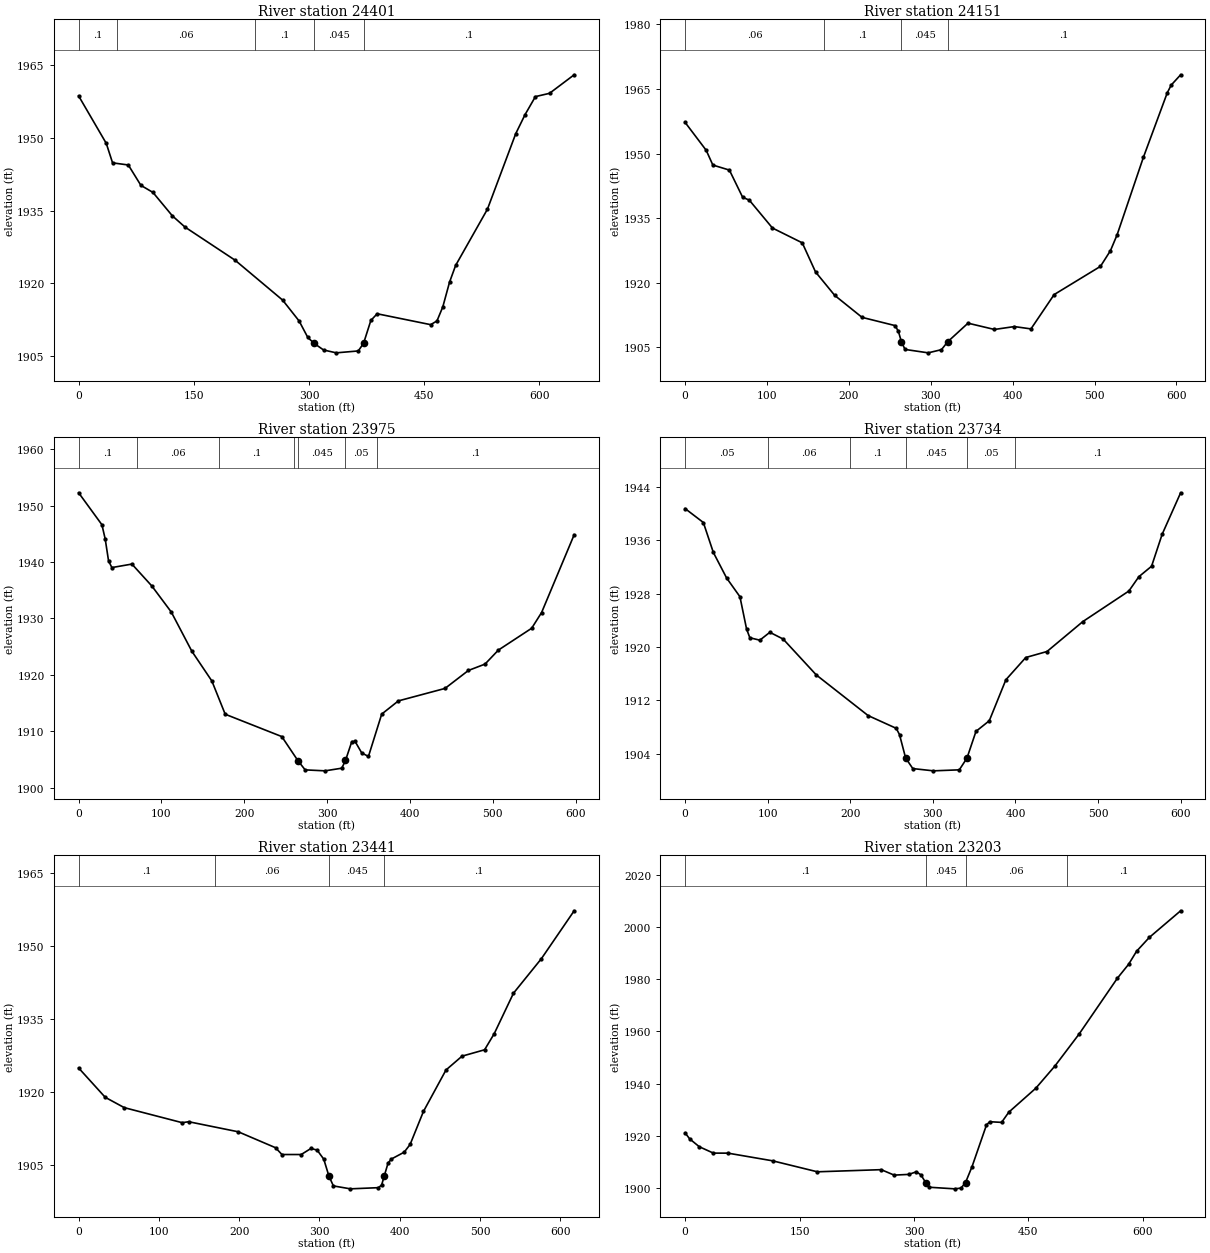
Type RM Length L Ch R = 1 ,24401   ,245.4,250.4,242.9
XS GIS Cut Line= 3
2214159.40107529 680816.248554472214288.59317172680249.384375088
2214343.37762971680216.231752031
#Sta/Elev= 30
       0 1958.67      36 1948.87    44.2 1944.85    64.7 1944.41    81.1  1940.2
    96.8 1938.74   122.1  1933.9   138.5 1931.59   203.7 1924.75   265.7  1916.5
   287.2 1912.18   298.5 1908.78   306.81907.555     319  1906.2   335.5 1905.61
   364.2    1906   371.11907.578   380.6  1912.3   388.8 1913.68   458.5 1911.43
   466.7  1912.2   474.3  1915.1   483.1 1920.22     491 1923.66   532.4 1935.27
   569.3 1950.88   581.4  1954.8   594.9 1958.53   613.3 1959.21   645.4 1963.04
#Mann= 5 ,-1,0
       0      .1       0      50     .06       0     230      .1       0
   306.8    .045       0   371.1      .1       0
Bank Sta=306.8,371.1
XS Rating Curve= 0 ,0
Exp/Cntr(USF)=0,0
Exp/Cntr=0.3,0.1

Type RM Length L Ch R = 1 ,24151   ,174.1,175.5,172.1
XS GIS Cut Line= 2
2214423.57827397680834.6621676842214515.30048441680236.454080397
#Sta/Elev= 30
       0 1957.24    25.8 1950.75    33.9 1947.33    54.1 1946.16    70.3 1939.84
    78.4 1939.18   106.7  1932.7   143.1 1929.26   159.3  1922.5   182.7 1917.06
   216.1 1911.95   256.4 1910.04   260.5 1908.71   264.1 1906.33   268.6  1904.5
   296.9 1903.71   313.1 1904.45   320.8  1906.3   345.5  1910.6   377.8 1909.14
   402.1 1909.81   422.4 1909.27   450.7 1917.24   507.3  1923.8   519.5 1927.45
   527.6 1931.12   559.7 1949.12   588.9 1964.13   593.7 1965.91   605.2  1968.3
#Mann= 4 ,-1,0
       0     .06       0     170      .1       0   264.1    .045       0
   320.8      .1       0
Bank Sta=264.1,320.8
XS Rating Curve= 0 ,0
Exp/Cntr(USF)=0,0
Exp/Cntr=0.3,0.1

Type RM Length L Ch R = 1 ,23975   ,240.2,241.5,241.3
XS GIS Cut Line= 2
2214609.50981375680829.1149451782214670.44970686680234.164224215
#Sta/Elev= 30
       0 1952.27    28.1 1946.61    32.1 1944.06    36.1 1940.22    40.1 1939.02
    64.3 1939.64    88.4 1935.75   111.8 1931.15   136.6 1924.21   160.8 1918.93
   176.9 1913.04   245.2 1909.08   264.61904.829   273.4 1903.18   297.5 1903.01
   317.6 1903.48   322.1 1904.85   329.7 1908.19   333.7 1908.21   341.7 1906.18
   349.8 1905.56   365.8 1913.06   385.9  1915.4   442.2 1917.61   470.4 1920.79
   490.5 1921.92   506.6  1924.4   546.8 1928.27   558.8 1931.06   598.1 1944.84
#Mann= 7 ,-1,0
       0      .1       0      70     .06       0     170      .1       0
     260     .05       0   264.6    .045       0   322.1     .05       0
     360      .1       0
Bank Sta=264.6,322.1
XS Rating Curve= 0 ,0
Exp/Cntr(USF)=0,0
Exp/Cntr=0.3,0.1

Type RM Length L Ch R = 1 ,23734   ,292.6,292.8,288.7
XS GIS Cut Line= 2
2214841.68661699680863.1247198112214908.81520649680266.891751524
#Sta/Elev= 30
       0 1940.74    22.1 1938.65    34.2 1934.16    50.3 1930.32    66.4 1927.52
    74.4 1922.69    78.4 1921.36    90.5    1921   102.6 1922.18   118.7 1921.17
   158.9 1915.78   221.6 1909.69   255.6 1907.78   259.6 1906.84     267 1903.33
   275.7 1901.74   300.7  1901.4     332 1901.55   341.31903.313   352.2 1907.32
   368.3 1908.91   388.4 1915.06   412.5  1918.4   438.2  1919.3   481.6 1923.79
   537.3 1928.37   549.4 1930.52   564.8 1932.09   577.6 1936.88     600 1943.11
#Mann= 6 ,-1,0
       0     .05       0     100     .06       0     200      .1       0
     267    .045       0   341.3     .05       0     400      .1       0
Bank Sta=267,341.3
XS Rating Curve= 0 ,0
Exp/Cntr(USF)=0,0
Exp/Cntr=0.3,0.1

Type RM Length L Ch R = 1 ,23441   ,227.6,237.5,241.3
XS GIS Cut Line= 2
2215142.40206086 680934.010337372215179.98960314680317.718251334
#Sta/Elev= 30
       0 1924.94    33.1 1918.92    56.9 1916.79   129.1  1913.7   137.1  1913.9
   198.9 1911.83   245.3 1908.56   253.3 1907.16   277.3 1907.16   289.4  1908.4
   297.1 1908.08   305.4 1906.21   311.8 1902.75   317.4 1900.71   338.6 1900.11
   373.5 1900.35   377.5 1900.89   380.71902.707   385.5 1905.39   389.6 1906.23
   405.6 1907.64     413 1909.23   429.6 1916.01   457.7 1924.53   477.7 1927.37
   505.8 1928.68   517.8 1931.99   541.8 1940.31   576.6 1947.41   617.4 1957.24
#Mann= 4 ,-1,0
       0      .1       0     170     .06       0   311.8    .045       0
   380.7      .1       0
Bank Sta=311.8,380.7
XS Rating Curve= 0 ,0
Exp/Cntr(USF)=0,0
Exp/Cntr=0.3,0.1

Type RM Length L Ch R = 1 ,23203   ,283.6,306.8,314.8
XS GIS Cut Line= 2
2215291.64280519680946.9527096542215482.13228994680325.932294495
#Sta/Elev= 30
       0 1921.07       6 1918.75    18.6 1915.74    37.1 1913.29    56.2 1913.28
   114.8 1910.33   173.4 1906.12   257.1 1906.94     274 1904.85   293.2 1905.12
   303.1 1906.12   309.2 1904.93   315.3 1902.01   319.8  1900.2   353.3 1899.58
   361.7 1899.86   367.61901.998   376.1 1908.06   395.1 1924.11   399.3 1925.34
   414.9 1925.09   424.4 1929.02   459.7 1938.18   484.7 1946.69   516.5 1958.99
   566.7 1980.43   581.4 1985.76   591.8 1990.75   608.5 1996.06   649.6  2006.3
#Mann= 4 ,-1,0
       0      .1       0   315.3    .045       0   367.6     .06       0
     500      .1       0
Bank Sta=315.3,367.6
XS Rating Curve= 0 ,0
Exp/Cntr(USF)=0,0
Exp/Cntr=0.3,0.1

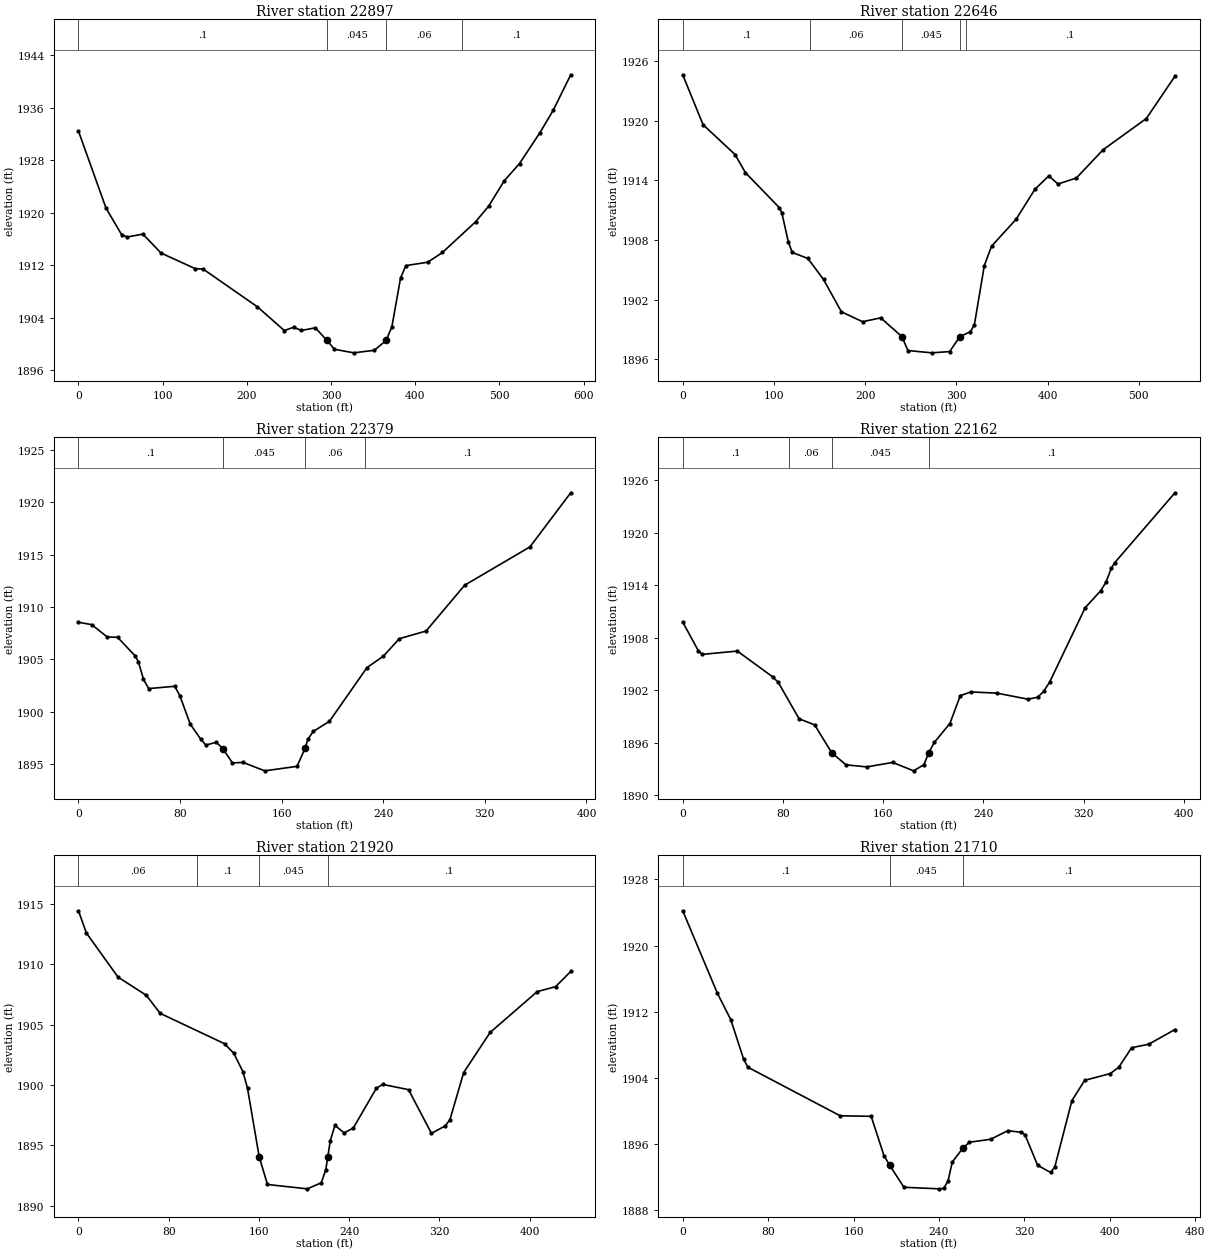
Type RM Length L Ch R = 1 ,22897   ,254.4,250.7,239.1
XS GIS Cut Line= 3
2215344.91129811681026.2103350282215671.81739658 680753.63421003
 2215775.9631141680633.447388849
#Sta/Elev= 30
       0 1932.47    32.8 1920.72    51.3 1916.69    57.8 1916.34    76.6 1916.78
      98  1913.9     139  1911.5   147.9 1911.47   212.6  1905.7   244.5 1902.09
   255.8 1902.59   264.7  1902.1   281.4  1902.5   295.2 1900.58   304.1 1899.23
   327.1 1898.69   351.4 1899.08   365.51900.576   372.3 1902.68   382.6  1910.1
   388.9 1911.98   414.9  1912.5   432.3 1913.98   471.6 1918.64   487.3 1921.06
   505.6 1924.88   523.9 1927.54     548 1932.21   563.9 1935.65   584.7 1941.06
#Mann= 4 ,-1,0
       0      .1       0   295.2    .045       0   365.5     .06       0
  455.64      .1       0
Bank Sta=295.2,365.5
XS Rating Curve= 0 ,0
Exp/Cntr(USF)=0,0
Exp/Cntr=0.3,0.1

Type RM Length L Ch R = 1 ,22646   ,275.3,266.6,258
XS GIS Cut Line= 3
2215605.48280608681202.8678332222215873.58647442680855.215028791
2215941.36975769680781.105305751
#Sta/Elev= 30
       0 1924.61    22.3 1919.59    57.3 1916.59    68.7 1914.77   105.8 1911.25
   108.6 1910.73   115.8 1907.77   120.1 1906.74   137.2 1906.13   154.3 1904.02
   173.9 1900.77   197.1 1899.77     217 1900.16   240.21898.274   246.8 1896.87
     273 1896.64   292.6 1896.77   303.71898.274   315.3 1898.76   319.7 1899.48
   330.5 1905.41   338.5 1907.37   365.3 1910.07     386 1913.09   401.2 1914.44
   411.3 1913.62   431.5 1914.23   460.6 1917.06   508.1 1920.21   539.5 1924.47
#Mann= 5 ,-1,0
       0      .1       0     140     .06       0   240.2    .045       0
   303.7     .07       0     310      .1       0
Bank Sta=240.2,303.7
XS Rating Curve= 0 ,0
Exp/Cntr(USF)=0,0
Exp/Cntr=0.3,0.1

Type RM Length L Ch R = 1 ,22379   ,218.4,217.4,215.9
XS GIS Cut Line= 4
2215953.87065776681271.3808328232215975.16878853681167.744188602
2216027.22635008681019.7054979442216063.07296741680900.095806646
#Sta/Elev= 30
       0 1908.53    10.4  1908.3    22.7 1907.12    30.8 1907.09    44.5 1905.33
    47.2 1904.75    51.2 1903.07    55.3 1902.19    75.8 1902.41    79.8 1901.52
      88  1898.8    96.2 1897.37   100.3 1896.79   108.5 1897.06   113.71896.455
   121.2 1895.09   129.7 1895.13   146.7 1894.33   172.1 1894.76   178.41896.472
   180.6 1897.33   184.8 1898.09   197.6 1899.06   227.2  1904.2     240 1905.28
   252.7 1906.96   273.7 1907.69   304.1 1912.07   355.5 1915.73   387.6  1920.9
#Mann= 4 ,-1,0
       0      .1       0   113.7    .045       0   178.4     .06       0
   225.8      .1       0
Bank Sta=113.7,178.4
XS Rating Curve= 0 ,0
Exp/Cntr(USF)=0,0
Exp/Cntr=0.3,0.1

Type RM Length L Ch R = 1 ,22162   ,242.4,242.4,239.6
XS GIS Cut Line= 3
2216148.27311418 681337.266184162216167.31937994681285.481987292
2216258.42011266680960.122227605
#Sta/Elev= 30
       0 1909.81    12.5 1906.53    15.6 1906.12    43.6  1906.5    72.1 1903.52
    76.3 1902.91    92.9 1898.76   105.3 1898.07   118.91894.885   130.3  1893.5
   146.9 1893.26   167.6 1893.77   184.3 1892.81   192.6 1893.52   196.4 1894.89
   200.9 1896.07   213.3 1898.22   221.6  1901.4     230 1901.83   250.8 1901.69
   275.6    1901   283.3 1901.22   288.1 1901.88     293 1902.97   321.3 1911.45
   333.8 1913.41     338 1914.39   342.1 1915.95   344.9  1916.6     393 1924.59
#Mann= 4 ,-1,0
       0      .1       0   85.18     .06       0   118.9    .045       0
   196.4      .1       0
Bank Sta=118.9,196.4
XS Rating Curve= 0 ,0
Exp/Cntr(USF)=0,0
Exp/Cntr=0.3,0.1

Type RM Length L Ch R = 1 ,21920   ,216,209.6,204.9
XS GIS Cut Line= 3
2216380.90534235 681451.955499452216389.03933634681417.792724682
2216467.12567867681024.107415461
#Sta/Elev= 30
       0 1914.44       7  1912.6    35.1 1908.94    60.2 1907.43    72.4 1905.94
   129.5 1903.42   137.7 1902.63   145.8 1901.11   149.9 1899.72   160.31894.024
   167.6 1891.75   202.9 1891.39   215.3 1891.89   219.3 1892.98     2211893.996
   223.3 1895.37   227.4 1896.65   235.6 1896.03   243.7 1896.43   264.1 1899.72
   269.7 1900.05   292.7 1899.61     313 1895.99   325.3 1896.61   329.4 1897.13
   341.6 1901.03     365 1904.35   406.8 1907.74   423.1 1908.15   436.5 1909.41
#Mann= 4 ,-1,0
       0     .06       0  105.12      .1       0   160.3    .045       0
     221      .1       0
Bank Sta=160.3,221
XS Rating Curve= 0 ,0
Exp/Cntr(USF)=0,0
Exp/Cntr=0.3,0.1

Type RM Length L Ch R = 1 ,21710   ,203.8,205.7,201.8
XS GIS Cut Line= 3
2216624.46687488681501.636079426 2216626.2744291 681108.49303647
 2216627.2575598 681040.52673125
#Sta/Elev= 30
       0 1924.21    32.5 1914.22      45 1911.04      57 1906.27      61 1905.28
   147.5  1899.4   176.5 1899.34   188.5 1894.59   193.71893.443   207.2 1890.75
   240.5 1890.56   244.5 1890.62   248.5 1891.51   252.5 1893.81   262.31895.461
   268.5  1896.2   288.5 1896.56   304.5  1897.6   316.5 1897.41   320.5 1897.13
   332.5  1893.4   344.5 1892.55   348.5  1893.2   364.5 1901.22   376.5 1903.69
   400.5 1904.51   408.5 1905.28   420.5 1907.64   436.5 1908.06   461.1 1909.84
#Mann= 3 ,-1,0
       0      .1       0   193.7    .045       0   262.3      .1       0
Bank Sta=193.7,262.3
XS Rating Curve= 0 ,0
Exp/Cntr(USF)=0,0
Exp/Cntr=0.3,0.1

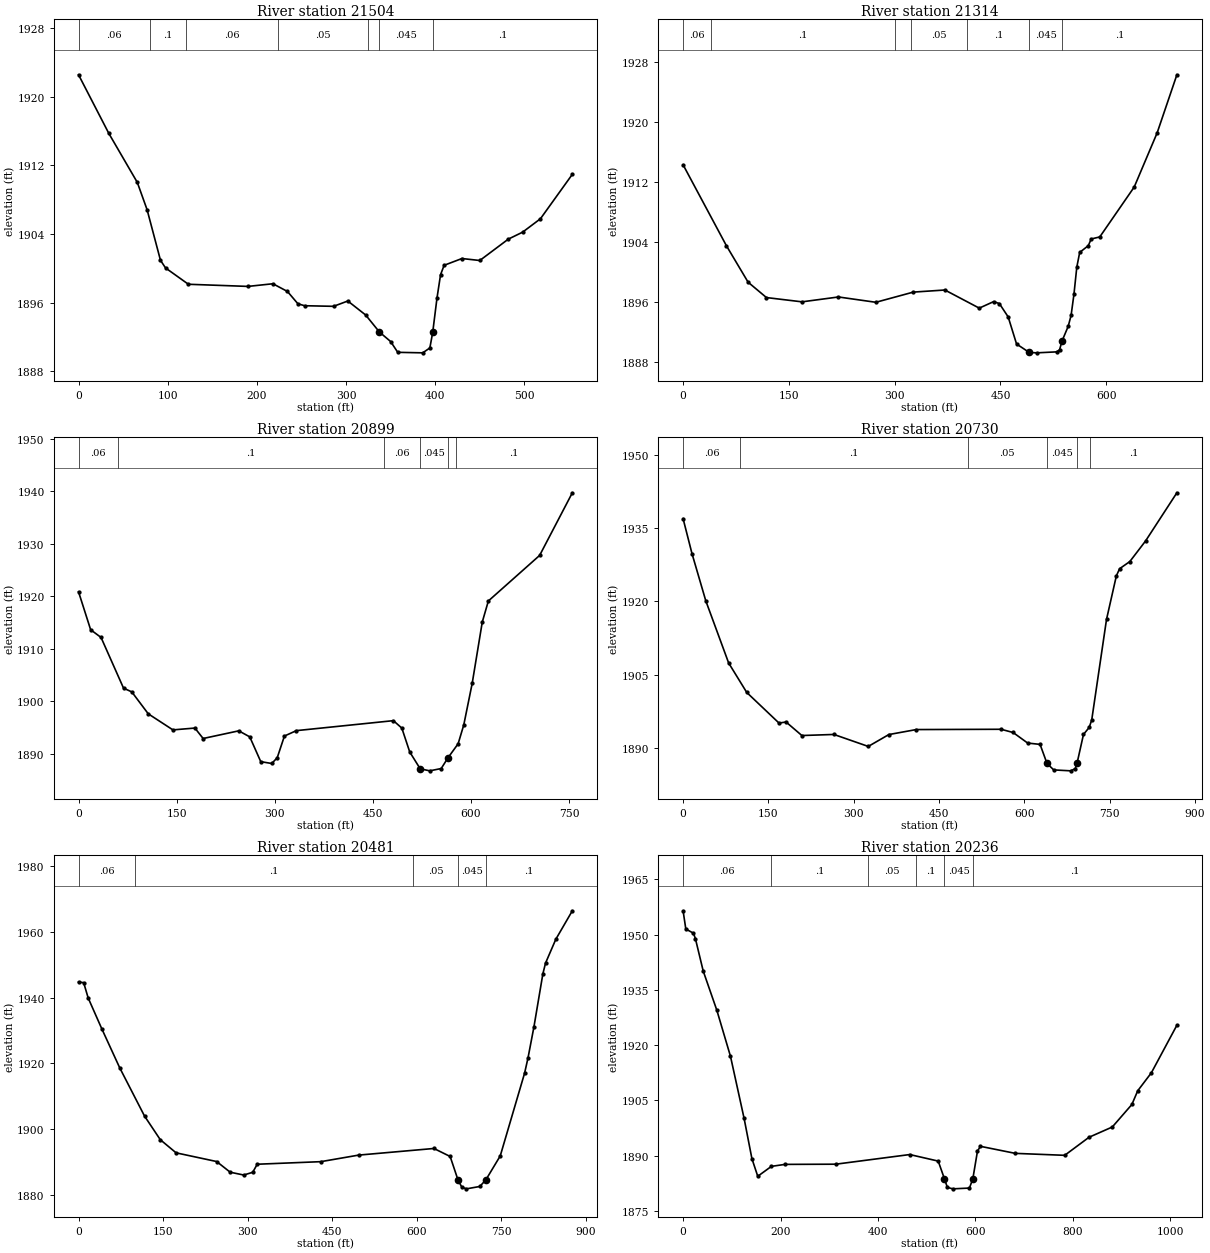
Type RM Length L Ch R = 1 ,21504   ,182.8,189.9,193.3
XS GIS Cut Line= 3
2216718.89344198681545.1446174872216815.46042068681425.057464884
2216820.48140463681025.387142799
#Sta/Elev= 30
       0 1922.57      34 1915.73    65.9 1910.03    76.9 1906.84    91.9 1900.95
    97.6 1900.06   123.2 1898.16     190 1897.91     218 1898.22   234.3 1897.32
     246 1895.89   253.5 1895.66     286 1895.59     302 1896.21     322 1894.58
   337.51892.589     350 1891.49     358 1890.23     386 1890.17     394 1890.74
   397.21892.553     402 1896.55     406 1899.27     410 1900.37     430 1901.16
     450 1900.93     482 1903.42     498 1904.23     518 1905.79   553.8 1910.97
#Mann= 7 ,-1,0
       0     .06       0      80      .1       0     120     .06       0
   224.1     .05       0   324.1      .1       0   337.5    .045       0
   397.2      .1       0
Bank Sta=337.5,397.2
XS Rating Curve= 0 ,0
Exp/Cntr(USF)=0,0
Exp/Cntr=0.3,0.1

Type RM Length L Ch R = 1 ,21314   ,392.7,415.1,437.6
XS GIS Cut Line= 3
2216744.82707979 681668.283239172216965.56511193681446.264062372
2217035.85888717681065.673479281
#Sta/Elev= 30
       0 1914.34    61.5 1903.52    92.2 1898.66   118.2 1896.61   168.6 1896.04
   220.3 1896.69   273.3 1895.98   326.4 1897.34   371.2 1897.62   419.9  1895.2
   440.3 1896.07   448.4 1895.81   460.9 1894.03   472.8 1890.41   490.81889.282
   501.3 1889.23   529.8 1889.36   533.8 1889.64   537.21890.795     546 1892.77
   550.1 1894.22   554.2 1897.08   558.2 1900.67   562.3 1902.64   574.5 1903.54
   578.6 1904.43   590.8 1904.71   639.6 1911.37   672.1  1918.6   700.1 1926.36
#Mann= 7 ,-1,0
       0     .06       0      40      .1       0     300     .06       0
  323.08     .05       0  403.08      .1       0   490.8    .045       0
   537.2      .1       0
Bank Sta=490.8,537.2
XS Rating Curve= 0 ,0
Exp/Cntr(USF)=0,0
Exp/Cntr=0.3,0.1

Type RM Length L Ch R = 1 ,20899   ,171.9,169.7,162.6
XS GIS Cut Line= 4
2216718.58517106681722.7423415562217125.38132435 681593.87991899
 2217365.0496247681498.7043788622217430.99188052681474.045768817
#Sta/Elev= 30
       0 1920.88    18.5 1913.66    34.4 1912.19    68.8 1902.53    81.4 1901.82
   106.6 1897.64   144.3 1894.58   177.9 1894.93   190.5 1892.94     245  1894.4
   261.8 1893.25   278.6 1888.53   295.4 1888.18   303.8 1889.28   314.8 1893.41
   333.1 1894.44   481.4 1896.34   494.3 1894.92   506.4 1890.37   522.41887.166
     537 1886.78   554.5 1887.22     565 1889.29   580.4 1891.94     589 1895.53
   601.9 1903.45   617.3 1915.13   626.6 1919.14     705 1927.82     755 1939.75
#Mann= 6 ,-1,0
       0     .06       0      60      .1       0  466.72     .06       0
   522.4    .045       0     565     .06       0  576.72      .1       0
Bank Sta=522.4,565
XS Rating Curve= 0 ,0
Exp/Cntr(USF)=0,0
Exp/Cntr=0.3,0.1

Type RM Length L Ch R = 1 ,20730   ,226.9,248.7,269.3
XS GIS Cut Line= 4
 2216672.5318504681804.7038919222217245.12346984 681743.50133613
2217411.05694728681633.6924172362217492.21437385681587.909046248
#Sta/Elev= 30
       0 1936.91    15.7 1929.74    39.9 1920.11    80.1 1907.39   111.9 1901.37
   168.6 1895.11     181 1895.33   208.8 1892.56   265.1 1892.78   325.5 1890.33
   361.7 1892.76   409.9 1893.78   558.9 1893.84   580.1 1893.18   605.7 1891.02
   627.5 1890.75   639.71886.853   651.5 1885.53   681.5 1885.34   689.4  1885.8
   692.51886.884   703.8 1892.78   713.8 1894.21   718.3 1895.73   744.3  1916.3
   761.6 1925.21   767.3 1926.67   785.3 1928.14   812.9 1932.34     868  1942.2
#Mann= 6 ,-1,0
       0     .06       0     100      .1       0     500     .05       0
   639.7    .045       0   692.5     .05       0  715.85      .1       0
Bank Sta=639.7,692.5
XS Rating Curve= 0 ,0
Exp/Cntr(USF)=0,0
Exp/Cntr=0.3,0.1

Type RM Length L Ch R = 1 ,20481   ,232.9,244.8,258.3
XS GIS Cut Line= 3
2216671.03769086681899.5121633372217244.53049783681892.198581522
2217538.35103984681966.583528867
#Sta/Elev= 30
       0 1944.77     9.1 1944.58    17.1 1939.92    41.1 1930.59    73.1 1918.63
   117.1 1903.94   145.1 1896.73   173.2 1892.72   245.2 1890.07   269.2 1886.82
   293.2 1885.96   309.2 1886.79   317.2 1889.25     430 1890.03   497.2 1892.03
   630.9 1894.05   659.7 1891.61   673.61884.468   680.5 1882.23   688.7 1881.75
   712.3 1882.47   723.11884.491   748.6 1891.78   791.9 1917.04     798 1921.73
   808.4 1931.09   824.3 1947.28     829 1950.54   847.3 1957.82   876.6 1966.49
#Mann= 5 ,-1,0
       0     .06       0     100      .1       0  593.54     .05       0
   673.6    .045       0   723.1      .1       0
Bank Sta=673.6,723.1
XS Rating Curve= 0 ,0
Exp/Cntr(USF)=0,0
Exp/Cntr=0.3,0.1

Type RM Length L Ch R = 1 ,20236   ,196,199.4,201.7
XS GIS Cut Line= 5
2216690.90586554682045.3475207112217159.82961334 682057.68553228
2217304.38198015 682190.33358653 2217409.0430259682278.682458139
2217620.55753273682274.100586865
#Sta/Elev= 30
       0 1956.45     5.6  1951.5    21.3 1950.36    25.3 1948.88    41.3  1940.1
    69.3 1929.44    97.3 1916.94   125.3 1900.06   141.3 1889.16   153.3 1884.37
   181.3 1887.06   209.3  1887.6   313.4 1887.65   465.4 1890.27   523.8 1888.49
   536.51883.712   542.6 1881.34   553.9 1880.96   587.9 1881.17   594.9  1883.7
   604.4 1891.21   610.5  1892.5   682.1 1890.59   783.5 1890.06   833.4 1894.96
   881.2 1897.75   921.4 1903.86   933.4 1907.58   961.4 1912.46  1013.8 1925.37
#Mann= 6 ,-1,0
       0     .06       0     180      .1       0     380     .05       0
  479.09      .1       0   536.5    .045       0   594.9      .1       0
Bank Sta=536.5,594.9
XS Rating Curve= 0 ,0
Exp/Cntr(USF)=0,0
Exp/Cntr=0.3,0.1

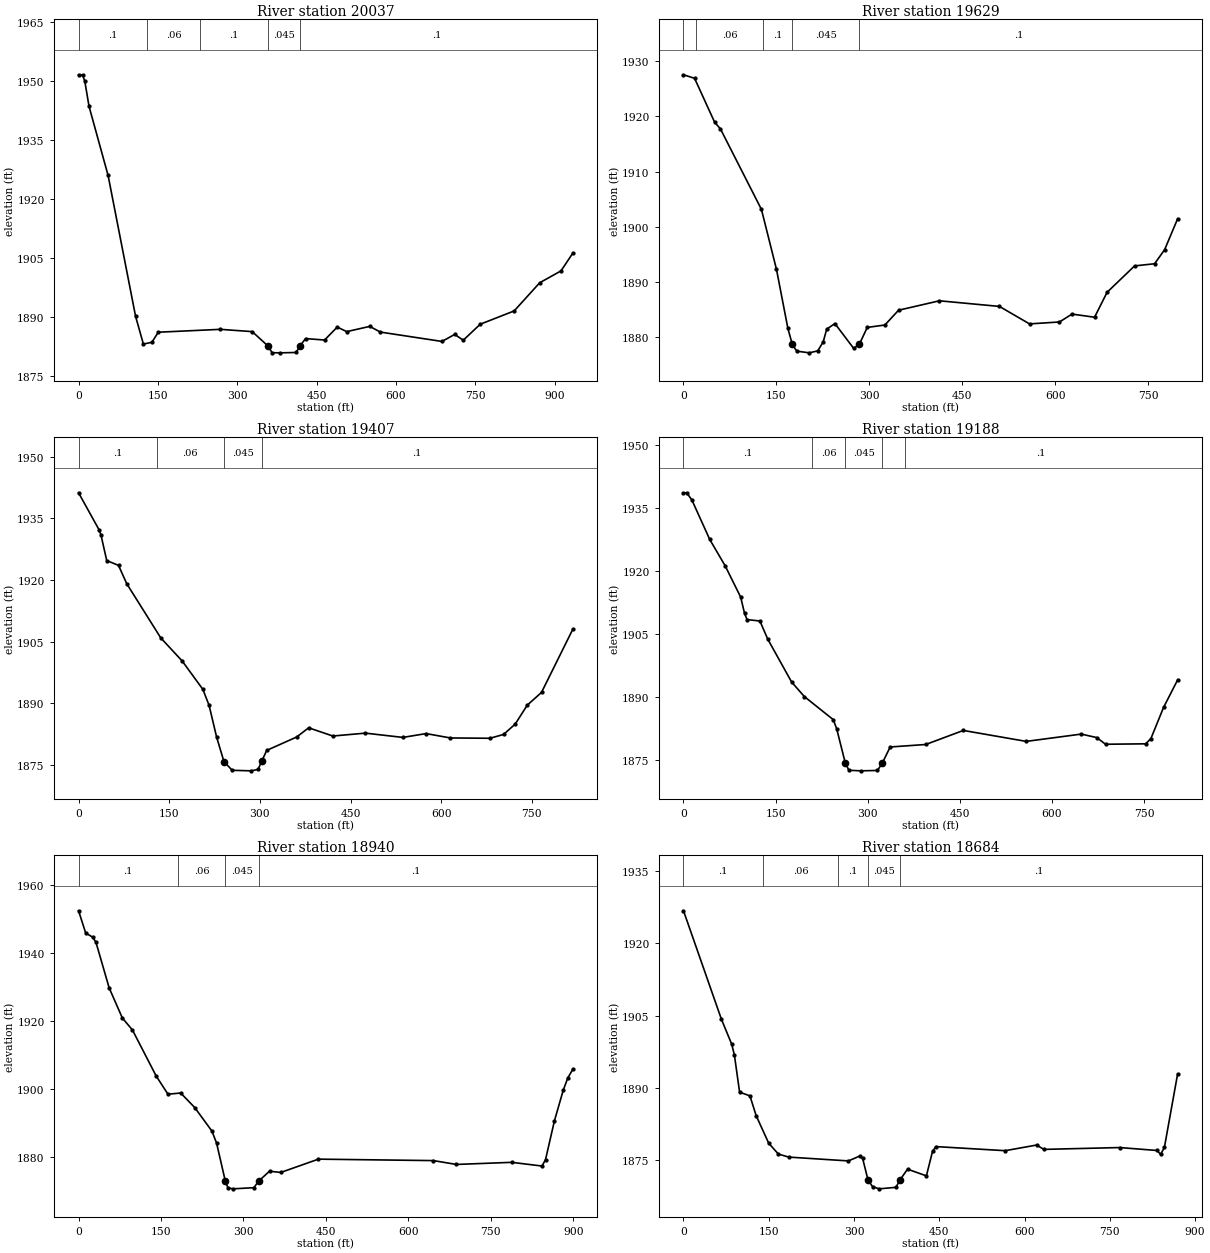
Type RM Length L Ch R = 1 ,20037   ,439.6,407.8,315.7
XS GIS Cut Line= 4
2216740.37979425682171.4615086142217008.41469105682172.430083909
2217191.42955588682375.7799337142217582.33265496682341.515753629
#Sta/Elev= 30
       0 1951.54     7.8 1951.41    11.8  1949.9    19.8  1943.5    55.8 1925.93
   107.8 1890.05   122.5 1883.02   138.6 1883.46   150.6 1886.03     268 1886.76
   328.2 1886.18   357.51882.592   365.9 1880.81   381.3 1880.78   411.2 1880.87
   418.91882.616   429.1 1884.41     465 1884.04   488.9 1887.33   506.9 1886.18
   550.4 1887.51   570.5 1886.06   686.9 1883.68     711 1885.47   727.1 1883.99
   759.2 1888.06   823.4 1891.45   871.6 1898.61   911.8 1901.63     934  1906.1
#Mann= 5 ,-1,0
       0      .1       0     130     .06       0     230      .1       0
   357.5    .045       0   418.9      .1       0
Bank Sta=357.5,418.9
XS Rating Curve= 0 ,0
Exp/Cntr(USF)=0,0
Exp/Cntr=0.3,0.1

Type RM Length L Ch R = 1 ,19629   ,223.6,222.2,217.3
XS GIS Cut Line= 4
2216860.77346847682644.1924627642216919.57442727682609.701444857
2217199.74533144682430.9544163872217592.98720384682375.813026159
#Sta/Elev= 30
       0 1927.56    17.9 1926.92    50.3 1918.94    59.6 1917.75   125.8 1903.14
   150.1 1892.26   168.5 1881.55   175.61878.658   182.8 1877.43     203 1877.12
   216.7 1877.48   225.5 1879.11   231.2 1881.42   244.4 1882.43   274.6 1877.94
   283.8 1878.66   296.6 1881.73   325.1 1882.17   347.1 1884.85   413.1 1886.56
     510 1885.54   558.5 1882.37   606.9 1882.72   627.1 1884.15   663.5 1883.58
   683.7  1888.1   728.1 1892.89   760.4 1893.28   776.6 1895.84   797.6 1901.44
#Mann= 5 ,-1,0
       0      .1       0      20     .06       0  128.17      .1       0
   175.6    .045       0   283.8      .1       0
Bank Sta=175.6,283.8
XS Rating Curve= 0 ,0
Exp/Cntr(USF)=0,0
Exp/Cntr=0.3,0.1

Type RM Length L Ch R = 1 ,19407   ,220,218.9,217.2
XS GIS Cut Line= 4
2216961.39209421682861.3484020072217010.56261118682828.617468771
 2217333.6796664682587.1299853922217644.25342964682415.118975351
#Sta/Elev= 30
       0 1941.25    33.9 1932.24      37 1931.02    46.6 1924.74    66.1 1923.57
    79.8 1919.08     136 1905.91   171.3 1900.31   205.6 1893.39   215.9 1889.51
   228.4 1881.75   240.5  1875.8   254.2 1873.67   285.3 1873.54     297 1873.87
   302.81875.827   311.3 1878.52   360.7 1881.77   380.7 1884.02   420.6 1882.02
   474.6 1882.72   536.4 1881.68     575 1882.61   615.1 1881.55   680.5 1881.47
   703.1  1882.4   722.4 1884.93   742.3 1889.53   765.9 1892.64   817.5 1907.97
#Mann= 4 ,-1,0
       0      .1       0  129.07     .06       0   240.5    .045       0
   302.8      .1       0
Bank Sta=240.5,302.8
XS Rating Curve= 0 ,0
Exp/Cntr(USF)=0,0
Exp/Cntr=0.3,0.1

Type RM Length L Ch R = 1 ,19188   ,249.7,247.8,247.1
XS GIS Cut Line= 2
2217088.17505482683060.2829721782217709.78892084682549.531309331
#Sta/Elev= 30
       0 1938.65     5.2 1938.71    13.6 1937.01    42.7 1927.59    67.9 1921.28
    93.1 1913.83    99.4 1909.95   103.5 1908.48   124.4 1908.14   137.2 1903.81
     176  1893.6   196.7 1890.13   243.8 1884.63   249.5  1882.4   263.41874.282
   269.3 1872.56   288.4 1872.42   315.8 1872.51   323.81874.296   336.5 1878.11
   394.4  1878.7   455.6 1882.05     558 1879.44   647.6 1881.18   672.8 1880.35
   687.1 1878.76   752.5 1878.86     761 1880.12   781.7 1887.58   804.5  1894.1
#Mann= 5 ,-1,0
       0      .1       0     210     .06       0   263.4    .045       0
   323.8     .06       0     360      .1       0
Bank Sta=263.4,323.8
XS Rating Curve= 0 ,0
Exp/Cntr(USF)=0,0
Exp/Cntr=0.3,0.1

Type RM Length L Ch R = 1 ,18940   ,270.8,256.1,237.5
XS GIS Cut Line= 2
2217230.95148214683278.3102726112217901.01298231682679.228423856
#Sta/Elev= 30
       0 1952.55      13 1945.98    25.7 1944.77    31.7 1943.24    55.7  1929.8
    79.7 1920.94      98 1917.42   141.1 1903.88   162.6  1898.5   185.8 1898.85
   211.3 1894.56   242.5 1887.65     251 1884.12     2671872.834   271.8 1870.89
   280.7 1870.61   318.9 1870.95   327.51872.877   347.3 1875.81   367.8 1875.44
   436.3 1879.36   645.5 1878.93   687.2  1877.8   787.9 1878.42     843 1877.33
   849.4 1879.25   865.5 1890.62   881.6 1899.69   889.9 1903.29   898.8 1905.79
#Mann= 4 ,-1,0
       0      .1       0     180     .06       0     267    .045       0
   327.5      .1       0
Bank Sta=267,327.5
XS Rating Curve= 0 ,0
Exp/Cntr(USF)=0,0
Exp/Cntr=0.3,0.1

Type RM Length L Ch R = 1 ,18684   ,282.6,293.6,303.2
XS GIS Cut Line= 4
2217441.55578749683420.0008235612217645.55896829683308.685786615
2217707.81916922683089.7708865782217962.71142317682769.500751256
#Sta/Elev= 30
       0 1926.74    66.8 1904.22      85 1899.03    89.6 1896.79    98.7 1889.13
   116.9 1888.37   127.8 1884.27   149.9 1878.55     167 1876.29   185.3 1875.67
   290.1 1874.88   310.9 1875.93   315.1 1875.41   324.41871.026   332.5 1869.55
   344.2 1869.09   373.6  1869.4   381.41871.019   394.1 1873.17   427.3 1871.78
   438.1 1876.86     444 1877.85     566    1877   621.2 1878.17     634 1877.27
   767.5 1877.65   833.1 1877.04   839.3 1876.23     846 1877.67   869.3 1892.94
#Mann= 5 ,-1,0
       0      .1       0     140     .06       0   272.4      .1       0
   324.4    .045       0   381.4      .1       0
Bank Sta=324.4,381.4
XS Rating Curve= 0 ,0
Exp/Cntr(USF)=0,0
Exp/Cntr=0.3,0.1

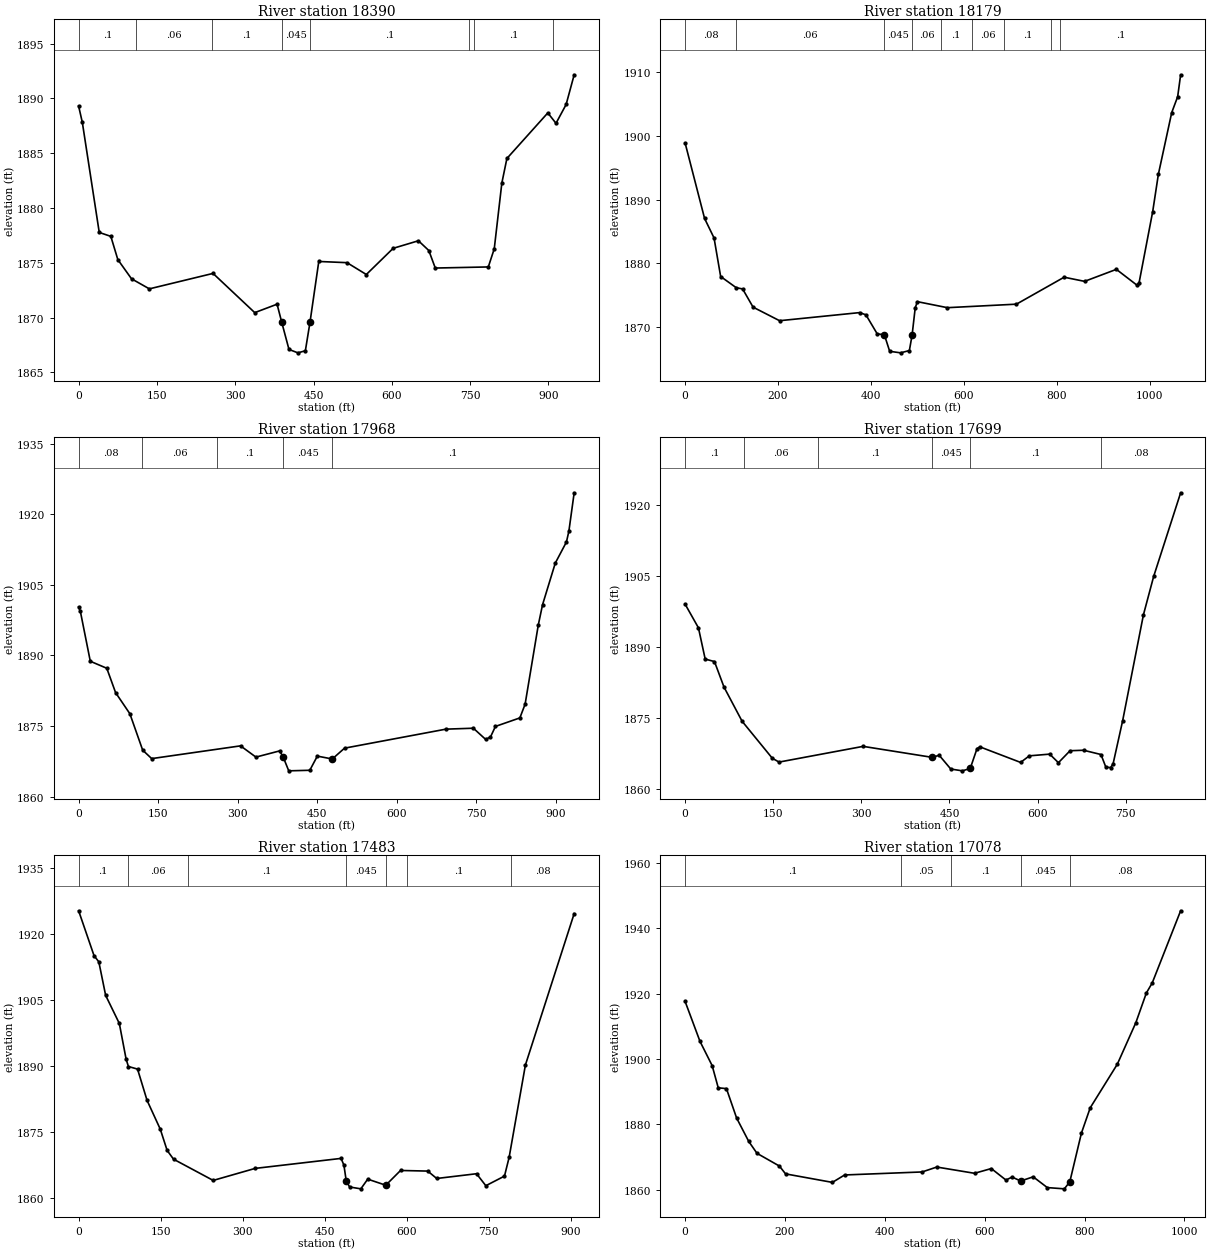
Type RM Length L Ch R = 1 ,18390   ,209.2,211.3,210.1
XS GIS Cut Line= 4
2217682.73444224683618.6303898112217846.91902076683423.796492632
2218001.56532629  683222.95713482218273.69837752682875.707733665
#Sta/Elev= 30
       0  1889.3     7.1 1887.81    39.5 1877.77    61.7 1877.41    75.1 1875.29
   101.3 1873.54   135.5 1872.62   257.5 1874.03   337.4 1870.45   380.2 1871.22
   389.21869.556     403 1867.09   420.1 1866.78   434.4 1866.97   443.21869.554
   460.1 1875.12   514.2 1875.01   551.2 1873.93   602.6 1876.32     651 1877.01
   670.9 1876.12   683.3 1874.52   784.9 1874.62   796.3 1876.28   810.8 1882.27
   820.5 1884.52   898.9 1888.68   914.6 1887.73     934 1889.45   949.4 1892.16
#Mann= 8 ,-1,0
       0      .1       0     110     .06       0  254.79      .1       0
   389.2    .045       0   443.2      .1       0  748.27     .06       0
  758.27      .1       0  908.27     .06       0
Bank Sta=389.2,443.2
XS Rating Curve= 0 ,0
Exp/Cntr(USF)=0,0
Exp/Cntr=0.3,0.1

Type RM Length L Ch R = 1 ,18179   ,211.6,211.3,212.2
XS GIS Cut Line= 3
 2217797.5206227 683802.14765723 2218189.6169722683325.673287971
2218557.38527877683067.699575282
#Sta/Elev= 30
       0 1898.86    41.9 1887.04    62.3 1883.98    76.5 1877.95     110  1876.2
   123.8    1876   146.3 1873.15   203.3 1871.03   375.6  1872.3   389.1 1871.95
   413.4 1868.97   428.8 1868.83   440.2 1866.24   463.7    1866   482.6 1866.36
   488.51868.799   495.2 1873.06   499.9 1874.01   564.4 1873.07     713 1873.62
   815.6 1877.84   859.6 1877.19     928 1879.07     972 1876.61   976.9 1876.98
  1006.2 1888.12  1018.4 1893.96  1047.1 1903.61  1059.9  1906.1  1066.3 1909.53
#Mann= 9 ,-1,0
       0     .08       0     110     .06       0   428.8    .045       0
   488.5     .06       0     550      .1       0  617.06     .06       0
  687.06      .1       0  787.06     .06       0  807.06      .1       0
Bank Sta=428.8,488.5
XS Rating Curve= 0 ,0
Exp/Cntr(USF)=0,0
Exp/Cntr=0.3,0.1

Type RM Length L Ch R = 1 ,17968   ,258.2,268.7,276.9
XS GIS Cut Line= 3
2217974.04439696683913.1829014232218396.25057388683410.318059594
2218636.84652333683271.375364342
#Sta/Elev= 30
       0 1900.28     3.3 1899.34      22 1888.76    53.1 1887.27    69.7 1882.09
    96.6 1877.61   120.8 1869.86   137.8 1868.07   305.3 1870.78   334.3 1868.39
   379.1 1869.71   385.81868.376   396.2 1865.47   435.9 1865.59   450.1  1868.6
   478.31867.988   501.4 1870.29   692.5 1874.33   744.3 1874.53   767.4 1872.16
   776.6 1872.66   785.9 1874.91     832 1876.72   841.9 1879.64   866.8  1896.5
   874.8 1900.79   898.8 1909.63   919.8 1914.11   924.4 1916.39   934.4 1924.57
#Mann= 5 ,-1,0
       0     .08       0     120     .06       0     260      .1       0
   385.8    .045       0   478.3      .1       0
Bank Sta=385.8,478.3
XS Rating Curve= 0 ,0
Exp/Cntr(USF)=0,0
Exp/Cntr=0.3,0.1

Type RM Length L Ch R = 1 ,17699   ,209.4,215.7,204.1
XS GIS Cut Line= 4
2218068.29539764684045.165105787 2218177.2602047683962.665229342
2218614.47367127 683643.744727732218777.29877995683673.803683818
#Sta/Elev= 30
       0  1899.1    22.7  1894.1    34.2 1887.49      50 1886.97    66.2 1881.58
      97 1874.36   148.4 1866.54   159.9 1865.73     303 1869.05   420.91866.723
   432.4 1867.18   452.2 1864.26   471.9 1863.88   485.31864.382   496.8 1868.56
   501.7 1868.95     571 1865.66   585.9 1867.05   620.5 1867.41   635.4  1865.6
   655.2 1868.13   678.2 1868.23   707.8 1867.33   716.2 1864.63   724.3 1864.58
   728.4 1865.34   744.7 1874.47   780.1 1896.86   797.5 1904.96   843.4 1922.63
#Mann= 6 ,-1,0
       0      .1       0     100     .06       0  226.67      .1       0
   420.9    .045       0   485.3      .1       0  707.84     .08       0
Bank Sta=420.9,485.3
XS Rating Curve= 0 ,0
Exp/Cntr(USF)=0,0
Exp/Cntr=0.3,0.1

Type RM Length L Ch R = 1 ,17483   ,338.9,405.6,385.4
XS GIS Cut Line= 4
2218060.75832845684196.7266341562218329.66948236684118.835772933
2218654.21706907683852.5085785812218847.97947209683782.151580555
#Sta/Elev= 30
       0 1925.25    28.2 1915.05    36.9 1913.67    49.4 1906.04    74.4 1899.67
    86.8 1891.57      91  1889.9   107.7 1889.31   125.1 1882.21   149.3 1875.66
   161.8 1870.85   173.5 1868.86     246 1864.04   322.7 1866.77   479.8 1869.04
     485 1867.49   489.21863.941   495.4 1862.55   515.9 1862.13   528.5 1864.33
   561.51862.951   588.5  1866.3   638.2 1866.16   654.6 1864.48   727.4 1865.56
   744.4 1862.84   778.5 1865.02     787 1869.28   816.8 1890.26   905.9 1924.61
#Mann= 7 ,-1,0
       0      .1       0      90     .06       0     200      .1       0
   489.2    .045       0   561.5     .05       0  599.96      .1       0
   789.8     .08       0
Bank Sta=489.2,561.5
XS Rating Curve= 0 ,0
Exp/Cntr(USF)=0,0
Exp/Cntr=0.3,0.1

Type RM Length L Ch R = 1 ,17078   ,376.6,428.2,431.2
XS GIS Cut Line= 3
2218122.99867234684342.2064462332218439.07123427 684278.39510873
2219077.54203231684075.076252653
#Sta/Elev= 30
       0  1917.6    29.8 1905.39    54.2 1897.97    66.4 1891.19    82.8 1890.95
   103.2 1881.95   127.5  1874.8     144 1871.17   188.9 1867.28   201.2 1864.89
     295 1862.29   319.5 1864.56   474.7 1865.48   504.1 1866.98   579.7 1865.07
   613.3 1866.52   642.6 1863.01   654.9 1863.92   672.11862.716   697.2 1863.99
   725.5  1860.7   759.6 1860.32   770.51862.466   793.8 1877.36   811.4 1885.08
   865.6 1898.38   902.9 1911.14   923.9 1920.19   935.6 1923.24   992.5 1945.29
#Mann= 5 ,-1,0
       0      .1       0  432.45     .05       0  532.45      .1       0
   672.1    .045       0   770.5     .08       0
Bank Sta=672.1,770.5
XS Rating Curve= 0 ,0
Exp/Cntr(USF)=0,0
Exp/Cntr=0.3,0.1