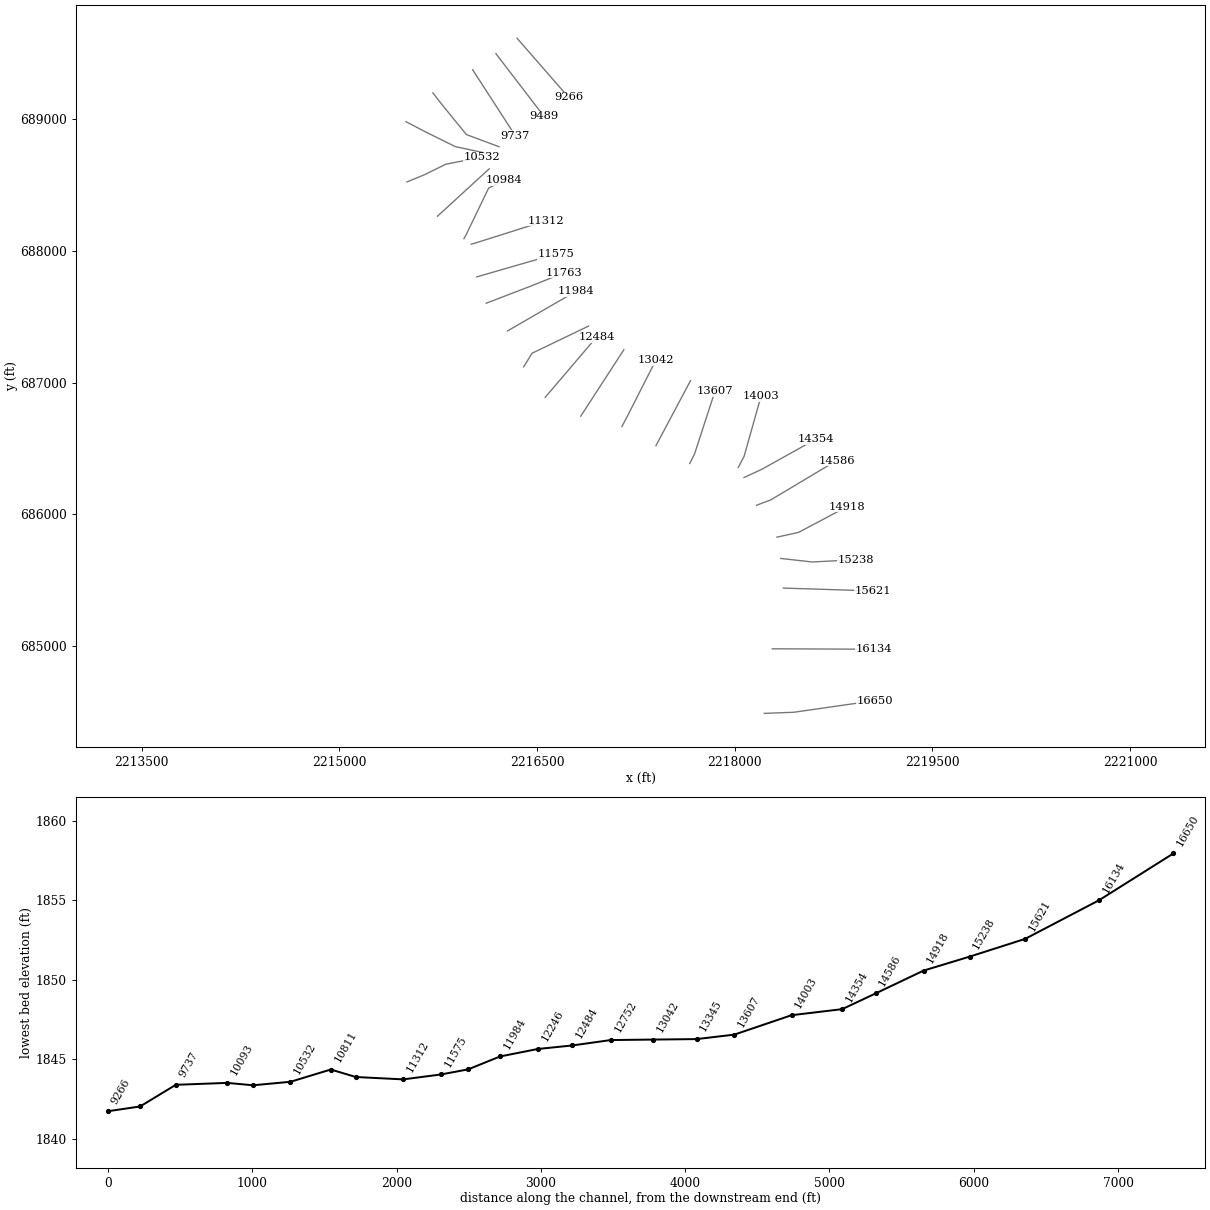
HEC-RAS study RFMIDDLERV.prj: RFMIDDLERV

--- RFMIDDLERV.g01 (geometry) --- (continued)

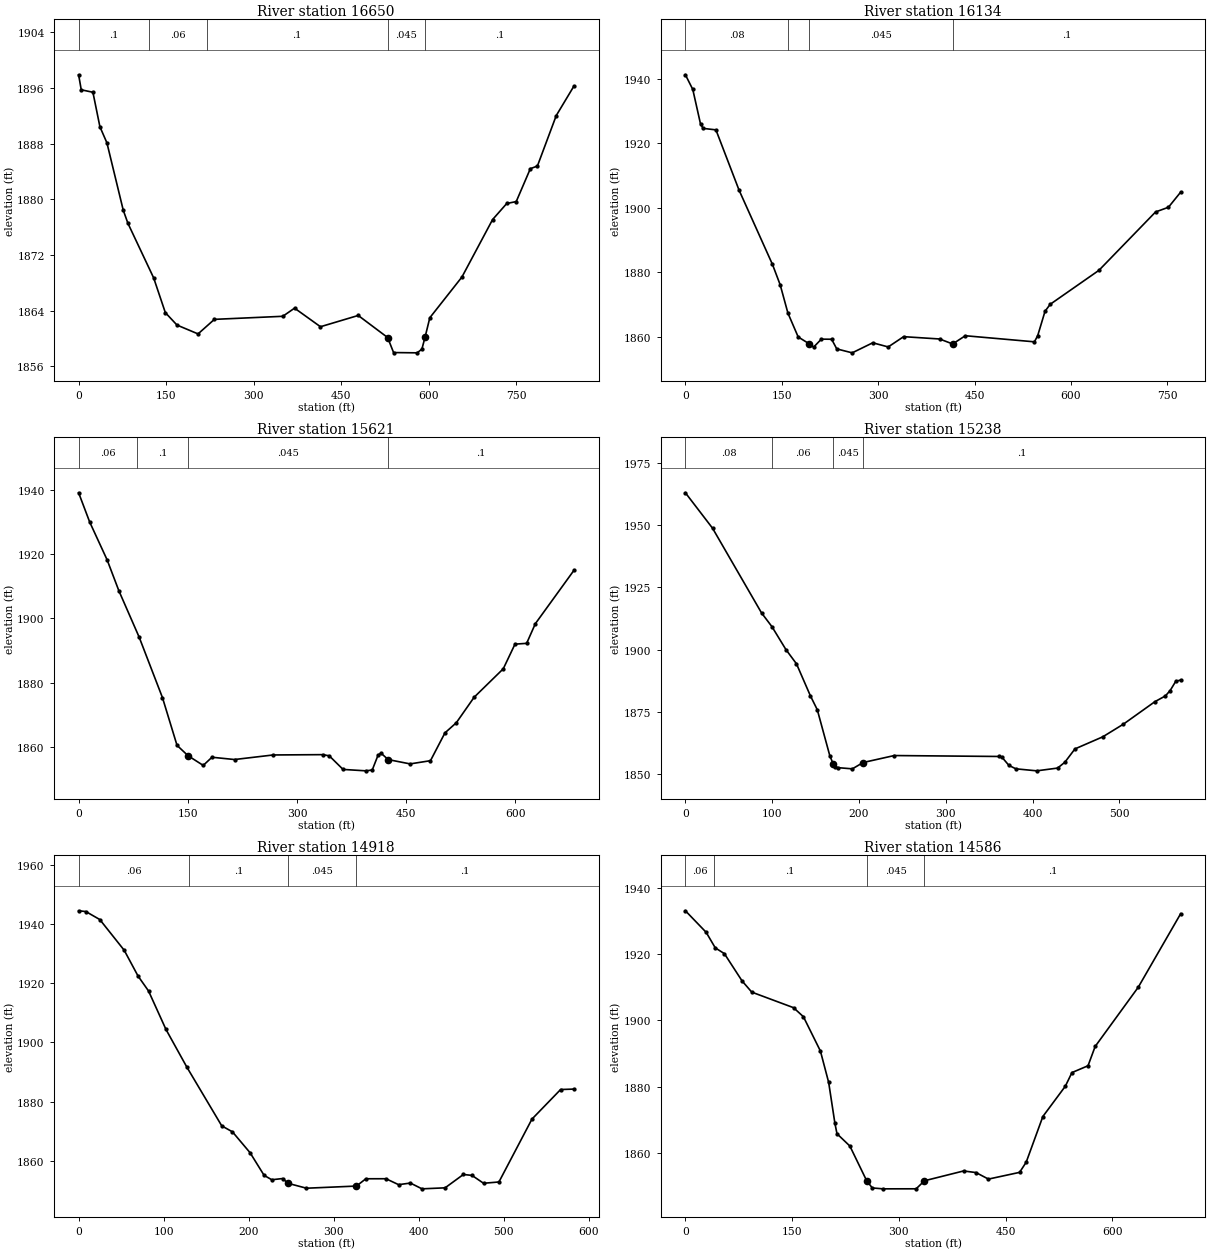
Type RM Length L Ch R = 1 ,16650   ,528.5,515.3,444.9
XS GIS Cut Line= 3
2218223.70005903684489.6210953022218446.17536678684497.918545452
2219066.04992799684586.690704835
#Sta/Elev= 30
       0 1897.89     4.5 1895.73    24.5 1895.38    36.5 1890.42    48.5 1888.11
    76.5 1878.43    84.5 1876.55   128.6 1868.71   148.6 1863.72   168.6 1861.93
   204.7 1860.66   232.7 1862.75   349.9 1863.19   370.1 1864.36   414.5 1861.69
   479.2 1863.31   529.61860.141   539.8 1857.98   580.2 1857.94   588.3 1858.47
   593.7 1860.17   601.9 1862.98     657 1868.84   709.5 1877.09   733.8  1879.4
     750 1879.67   774.2  1884.4   786.3 1884.78   818.6 1892.03   848.8 1896.25
#Mann= 5 ,-1,0
       0      .1       0     120     .06       0     220      .1       0
   529.6    .045       0   593.7      .1       0
Bank Sta=529.6,593.7
XS Rating Curve= 0 ,0
Exp/Cntr(USF)=0,0
Exp/Cntr=0.3,0.1

Type RM Length L Ch R = 1 ,16134   ,459.8,513,463.1
XS GIS Cut Line= 2
2218284.65391848684979.9302523182219055.15525815684976.800929773
#Sta/Elev= 30
       0 1941.32    11.5 1936.77    23.5 1926.08    27.5 1924.68    47.5 1924.22
    83.5  1905.5   135.5 1882.43   147.5  1876.1   159.5 1867.34   175.5 1859.92
     1931857.762   199.5 1856.77   211.5 1859.25   227.5 1859.22   235.5 1856.22
   259.5    1855   291.5 1858.12   315.5 1856.83   339.5 1860.02   395.5  1859.3
   415.81857.758   435.5 1860.31     543 1858.42   548.1 1860.33   559.5  1867.9
   567.5 1870.06   643.4 1880.62   731.5 1898.74   751.5 1900.19   770.5 1904.88
#Mann= 4 ,-1,0
       0     .08       0     160     .06       0     193    .045       0
   415.8      .1       0
Bank Sta=193,415.8
XS Rating Curve= 0 ,0
Exp/Cntr(USF)=0,0
Exp/Cntr=0.3,0.1

Type RM Length L Ch R = 1 ,15621   ,214.9,383.2,402.6
XS GIS Cut Line= 2
2218369.01909674 685440.983247072219049.03947976685419.524077718
#Sta/Elev= 30
       0 1939.11    15.2 1930.01    39.2 1918.21    55.2 1908.67    83.2 1894.16
   115.2 1875.35   135.2  1860.5   150.41857.269   171.2 1854.26   183.2  1856.8
   214.2 1856.09   267.3 1857.51   335.3 1857.61   344.3 1857.25   363.3 1853.01
   394.7 1852.57   403.4 1852.83   411.4 1857.46   415.4 1858.08   425.31856.073
   455.4 1854.73   483.4 1855.73   503.3 1864.39   518.9 1867.54   543.4 1875.48
   583.4 1884.33   599.5    1892   615.5 1892.25   627.5 1898.38   680.4 1914.94
#Mann= 4 ,-1,0
       0     .06       0      80      .1       0   150.4    .045       0
   425.3      .1       0
Bank Sta=150.4,425.3
XS Rating Curve= 0 ,0
Exp/Cntr(USF)=0,0
Exp/Cntr=0.3,0.1

Type RM Length L Ch R = 1 ,15238   ,280.6,320.3,336.4
XS GIS Cut Line= 3
2218349.02117306685666.0181259972218587.72375944685639.196405292
2218917.77357691685656.337796474
#Sta/Elev= 30
       0 1962.91    31.3  1948.7    87.7 1914.78    99.8 1909.21   115.8 1900.09
     128 1894.36   144.1 1881.49     152 1875.94   166.4 1857.54   170.1  1854.4
   172.2 1853.13   176.3 1852.72   192.4 1852.26   204.81854.793   240.7 1857.59
   360.8 1857.22   364.8 1856.92   372.8 1853.64   380.8 1852.27   404.9 1851.46
   428.9 1852.57   437.2 1854.88   448.9 1860.25     481  1865.1   504.8 1870.19
   541.1  1879.2   553.1 1881.48   558.6 1883.64   565.1 1887.37   570.7 1887.83
#Mann= 4 ,-1,0
       0     .08       0     100     .06       0   170.1    .045       0
   204.8      .1       0
Bank Sta=170.1,204.8
XS Rating Curve= 0 ,0
Exp/Cntr(USF)=0,0
Exp/Cntr=0.3,0.1

Type RM Length L Ch R = 1 ,14918   ,326.5,331.3,331.9
XS GIS Cut Line= 3
2218319.86768274685827.850986601 2218483.6191188685863.898055654
2218849.97140735686058.002757809
#Sta/Elev= 30
       0 1944.46     8.5  1944.2    24.9  1941.5    53.6 1931.13    69.9 1922.41
    82.2 1917.39   102.7  1904.4   127.3 1891.65   168.3 1871.84   180.9 1869.82
   201.6 1862.77   218.1 1855.13   227.1 1853.65     240 1854.06   246.11852.452
   267.9 1850.79   326.7 1851.52   337.7 1853.98   361.4 1853.99   376.2 1851.99
   390.1 1852.53   403.7 1850.58   430.9 1850.92   452.4 1855.43   462.5 1855.12
   476.1 1852.46   494.2  1852.9     533 1874.12   566.7 1884.11   582.3 1884.26
#Mann= 4 ,-1,0
       0     .06       0     130      .1       0   246.1    .045       0
   326.7      .1       0
Bank Sta=246.1,326.7
XS Rating Curve= 0 ,0
Exp/Cntr(USF)=0,0
Exp/Cntr=0.3,0.1

Type RM Length L Ch R = 1 ,14586   ,232.5,232.4,230.8
XS GIS Cut Line= 3
2218164.82687348686069.8696560242218271.92098381686110.046910186
2218771.27787281 686408.56002342
#Sta/Elev= 30
       0 1933.03    29.2 1926.53      42 1921.84    54.8  1920.1    79.7 1911.86
    93.3 1908.49     152  1903.8   165.9 1901.07   189.8 1890.72   201.4 1881.26
   210.2 1868.88   213.1 1865.77   231.2 1862.06   254.81851.608   262.7 1849.42
   277.8 1849.15   324.4 1849.16     3361851.581     391 1854.54   408.5 1854.06
     426 1852.09   469.8 1854.12   479.1  1857.2   502.5 1870.97   534.1 1880.11
   543.4 1884.22     566 1886.28     576 1892.09   636.6 1909.97   696.2 1932.14
#Mann= 4 ,-1,0
       0     .06       0      40      .1       0   254.8    .045       0
     336      .1       0
Bank Sta=254.8,336
XS Rating Curve= 0 ,0
Exp/Cntr(USF)=0,0
Exp/Cntr=0.3,0.1

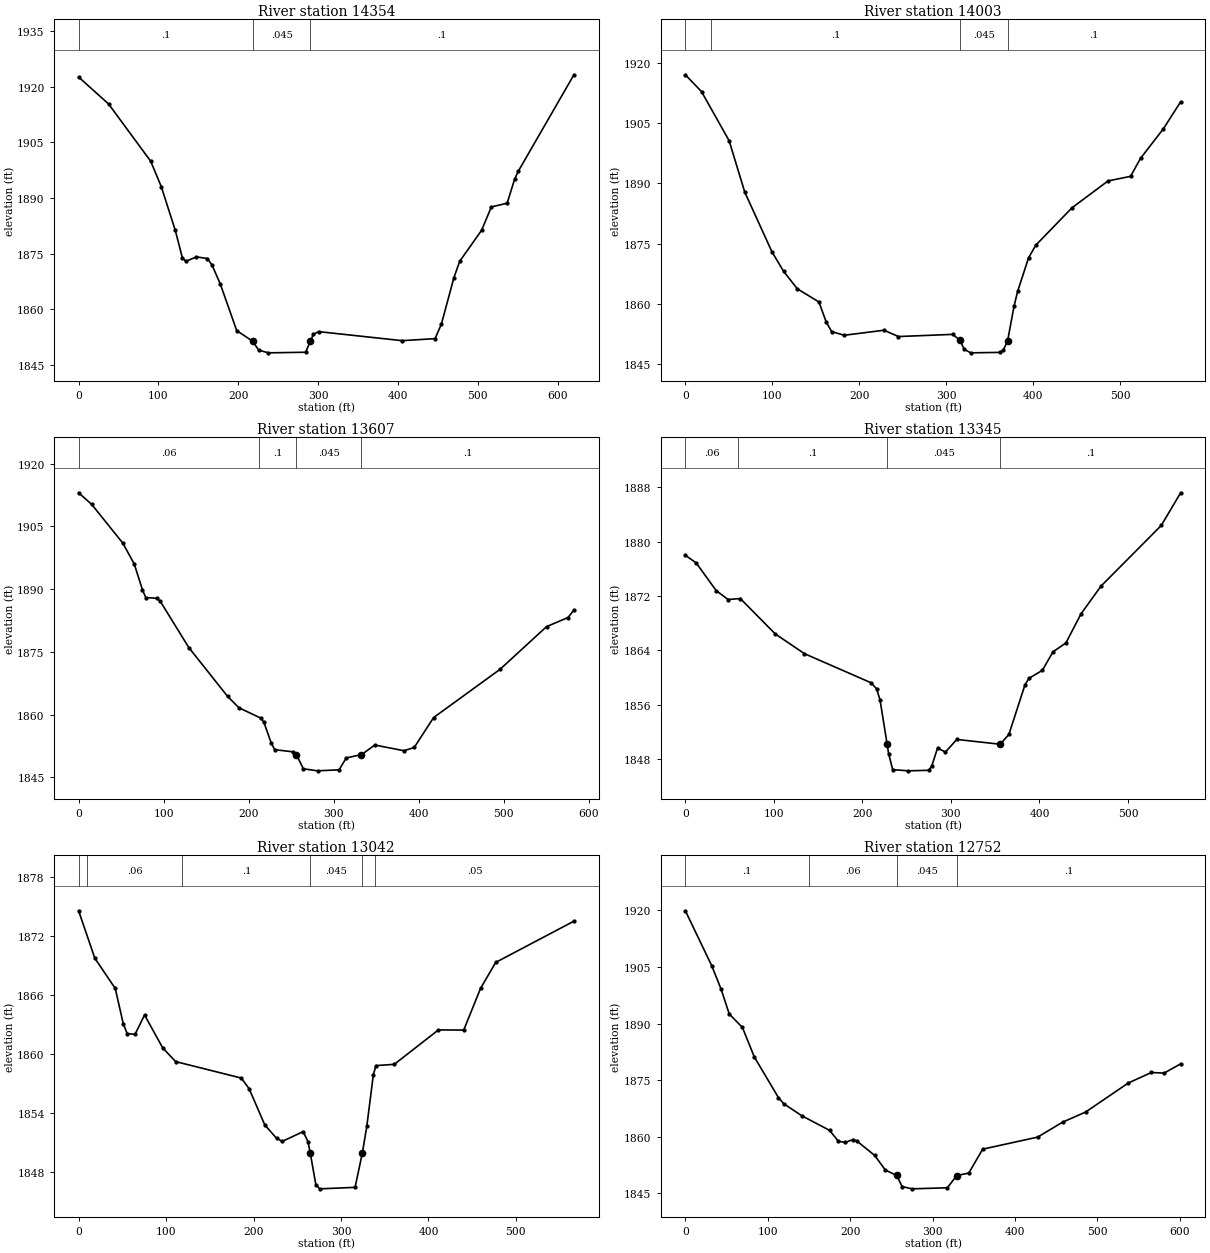
Type RM Length L Ch R = 1 ,14354   ,326.7,350.9,367.8
XS GIS Cut Line= 3
2218070.14405912686280.8159604822218201.53867639 686341.21057689
 2218617.2198103686572.755780174
#Sta/Elev= 30
       0 1922.68    37.5 1915.42    90.3 1899.93   103.5 1893.09   121.1 1881.24
   129.9 1873.87   134.3 1872.88   147.6 1874.09   161.4 1873.64   167.1 1871.88
   177.4  1866.8     198 1854.18     2181851.288   225.5 1848.91   237.7 1848.16
   284.3 1848.32   290.31851.284   294.1 1853.17   300.7 1853.89   405.3 1851.45
   446.5    1852   454.4 1855.93     470  1868.4   477.3 1872.89   504.8 1881.29
     517 1887.59   536.8  1888.6     546 1895.02   550.6 1897.19   620.4  1923.3
#Mann= 3 ,-1,0
       0      .1       0     218    .045       0   290.3      .1       0
Bank Sta=218,290.3
XS Rating Curve= 0 ,0
Exp/Cntr(USF)=0,0
Exp/Cntr=0.3,0.1

Type RM Length L Ch R = 1 ,14003   ,398.4,396.6,385.6
XS GIS Cut Line= 3
2218026.09752077686356.6921237682218070.49001294 686441.17427486
 2218198.8040471  686897.5259268
#Sta/Elev= 30
       0 1917.05    18.6 1912.85    50.3 1900.64    68.3 1887.82    99.6 1872.93
     113 1868.08   128.7 1863.74   153.6 1860.45   161.9  1855.5   168.2 1853.07
   182.7 1852.16   228.4 1853.41     245 1851.84   307.4 1852.38   315.81850.909
   320.6 1848.67   328.1 1847.78   361.4 1847.89   365.5 1848.38   370.61850.845
     378 1859.49   382.1  1863.1   394.6 1871.44   402.9 1874.59   444.5  1883.9
     486  1890.6   511.9 1891.75   523.4 1896.25   549.7 1903.61   569.5 1910.32
#Mann= 4 ,-1,0
       0     .06       0      30      .1       0   315.8    .045       0
   370.6      .1       0
Bank Sta=315.8,370.6
XS Rating Curve= 0 ,0
Exp/Cntr(USF)=0,0
Exp/Cntr=0.3,0.1

Type RM Length L Ch R = 1 ,13607   ,265.4,261.4,252.2
XS GIS Cut Line= 3
2217657.88031694686386.6612154882217694.65838044686459.680245562
2217849.47518822686935.794545704
#Sta/Elev= 30
       0 1913.03    15.5 1910.23    52.1 1900.96    65.5 1895.96    75.1  1889.8
      79 1887.98    91.7 1887.81      96 1887.09   129.6 1876.02   175.2 1864.35
   188.5 1861.64   214.3 1859.15   217.9 1858.14   226.3 1853.31   230.5 1851.62
   251.6 1851.12   256.11850.439   264.2 1847.05     281 1846.56   306.3 1846.81
   314.7 1849.65   332.61850.433   348.3 1852.73   382.5 1851.37   394.6 1852.14
   417.4 1859.29   495.5 1870.82   550.2 1881.03   575.5 1883.21   582.4 1885.02
#Mann= 4 ,-1,0
       0     .06       0  211.76      .1       0   256.1    .045       0
   332.6      .1       0
Bank Sta=256.1,332.6
XS Rating Curve= 0 ,0
Exp/Cntr(USF)=0,0
Exp/Cntr=0.3,0.1

Type RM Length L Ch R = 1 ,13345   ,303.2,303.5,302
XS GIS Cut Line= 2
2217401.73870642686522.3393433412217664.01823659687016.561663533
#Sta/Elev= 30
       0 1878.01    12.3 1876.88    34.9  1872.8    48.3  1871.5    62.1 1871.64
   101.5 1866.44   134.5 1863.53     210 1859.23     216 1858.35   219.9 1856.73
   227.91850.231   229.6 1848.82   234.2 1846.46   251.8 1846.28   274.9 1846.36
   278.3 1846.96   284.9 1849.64   293.8 1849.04   306.6  1850.9   355.71850.196
   365.5 1851.65   383.6 1858.92   388.1 1859.89   403.3 1861.08   415.3  1863.8
   429.9 1865.11     447  1869.4   469.6 1873.48   537.6  1882.4   559.5 1887.21
#Mann= 4 ,-1,0
       0     .06       0      60      .1       0   227.9    .045       0
   355.7      .1       0
Bank Sta=227.9,355.7
XS Rating Curve= 0 ,0
Exp/Cntr(USF)=0,0
Exp/Cntr=0.3,0.1

Type RM Length L Ch R = 1 ,13042   ,301.3,290.2,290.4
XS GIS Cut Line= 3
2217143.61863933686668.0159184512217198.66991342686773.238328255
2217401.22076609687172.340162332
#Sta/Elev= 30
       0 1874.59    18.5 1869.76    41.9 1866.67      51 1863.09    55.5 1862.08
    64.5    1862    75.4 1863.97    96.1 1860.62   110.9 1859.22     186 1857.54
   194.9 1856.46   212.9 1852.76   226.3  1851.4   232.9 1851.09   256.7 1852.08
   262.2 1851.07   264.81849.928   271.2 1846.69   275.7 1846.25   316.1  1846.4
   324.51849.953   329.5 1852.62     337  1857.9     340 1858.81   360.9 1858.94
   411.4 1862.45   440.3 1862.43   459.6 1866.69   476.9 1869.33   566.3 1873.53
#Mann= 6 ,-1,0
       0      .1       0      10     .06       0  118.75      .1       0
   264.8    .045       0   324.5      .1       0  338.75     .05       0
Bank Sta=264.8,324.5
XS Rating Curve= 0 ,0
Exp/Cntr(USF)=0,0
Exp/Cntr=0.3,0.1

Type RM Length L Ch R = 1 ,12752   ,268.3,267.8,259.4
XS GIS Cut Line= 2
2216831.19859133686746.3329075592217158.13398695687250.864272178
#Sta/Elev= 30
       0 1919.88      32 1905.34    43.3 1899.16    53.3 1892.53    69.3 1888.97
    83.7 1881.15     113 1870.39   119.5 1868.75   141.7 1865.54     175 1861.72
   185.7 1858.84     194 1858.51   203.6 1859.28   208.3 1858.87   229.8 1855.07
   242.8 1851.19   256.51849.764   263.1 1846.83   275.1 1846.22     318  1846.5
   329.5 1849.75     344 1850.39   360.9 1856.73   427.6 1859.92   457.8 1863.87
   485.8 1866.56   537.8 1874.28   565.8 1877.04   581.2 1876.88   601.2 1879.33
#Mann= 4 ,-1,0
       0      .1       0     150     .06       0   256.5    .045       0
   329.5      .1       0
Bank Sta=256.5,329.5
XS Rating Curve= 0 ,0
Exp/Cntr(USF)=0,0
Exp/Cntr=0.3,0.1

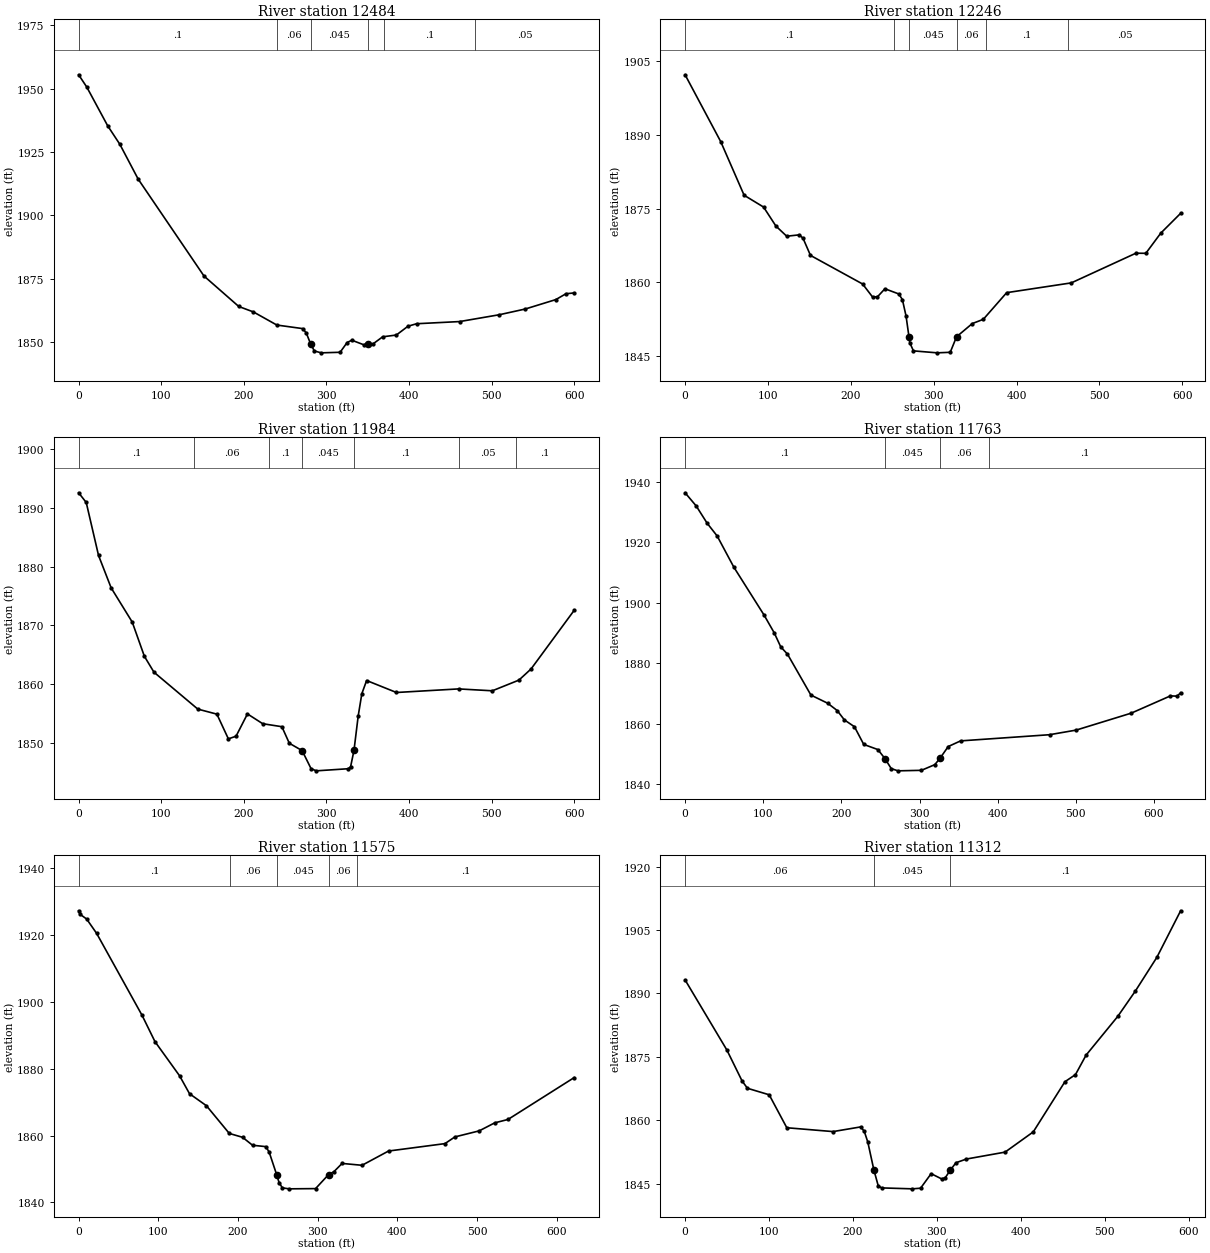
Type RM Length L Ch R = 1 ,12484   ,247.6,238,222.1
XS GIS Cut Line= 2
2216561.41505586686889.6164248342216950.56896102687346.299288647
#Sta/Elev= 30
       0 1955.43     9.9 1950.57    35.1 1935.37    49.9 1928.04    72.1 1914.32
   151.8 1876.14   193.9 1864.14   211.6    1862     240 1856.83   271.2 1855.43
   275.6 1853.74   280.91849.383   285.4 1846.62   293.7 1845.88   316.6  1846.1
   325.1 1849.95   330.8 1850.85     345 1849.09   350.41849.353   356.8 1849.49
   368.1 1852.19   384.7  1852.9   398.8 1856.37   409.3 1857.35   461.3  1858.2
   509.2 1860.88   540.8 1863.15   577.8 1866.86   590.1 1869.17     600 1869.48
#Mann= 6 ,-1,0
       0      .1       0     240     .06       0   280.9    .045       0
   350.4     .06       0     370      .1       0     480     .05       0
Bank Sta=280.9,350.4
XS Rating Curve= 0 ,0
Exp/Cntr(USF)=0,0
Exp/Cntr=0.3,0.1

Type RM Length L Ch R = 1 ,12246   ,260.1,262,265.1
XS GIS Cut Line= 3
2216397.75369901687120.6517236952216462.28925197687224.848642325
2216890.75902645687430.559177608
#Sta/Elev= 30
       0 1902.26      43 1888.65    71.2 1877.74    94.7 1875.33   109.6 1871.46
   122.6  1869.4     138 1869.68   142.4 1868.94   151.3 1865.49   214.2 1859.67
   226.2 1857.02   232.1 1857.07   241.1  1858.7   257.8 1857.65   262.2 1856.49
   266.6 1853.15   270.11848.959   271.1 1847.71   275.5 1846.06   304.1 1845.66
   319.9 1845.77   327.51848.922   346.5 1851.62   359.8 1852.48     388 1857.91
     466  1859.9   543.9 1865.94   555.9 1865.92   573.9 1870.02   597.9 1874.06
#Mann= 6 ,-1,0
       0      .1       0  252.56     .06       0   270.1    .045       0
   327.5     .06       0  362.56      .1       0  462.56     .05       0
Bank Sta=270.1,327.5
XS Rating Curve= 0 ,0
Exp/Cntr(USF)=0,0
Exp/Cntr=0.3,0.1

Type RM Length L Ch R = 1 ,11984   ,230.6,221.1,217.7
XS GIS Cut Line= 2
 2216275.3176194687393.3999933252216794.37195858687694.369415317
#Sta/Elev= 30
       0 1892.57     9.2 1890.92    24.1 1881.89    39.4 1876.36    64.9 1870.54
    79.6 1864.71    91.2    1862   144.3 1855.71   167.4 1854.85   181.3 1850.64
   190.6 1851.09   204.4 1854.89   222.9 1853.22   246.1 1852.71   255.1 1849.89
   270.61848.637   281.4 1845.57   287.7 1845.19   326.5 1845.55   329.3 1845.89
   333.41848.667   338.5 1854.54   342.9 1858.33   348.7 1860.58   384.8 1858.54
     460 1859.15   500.9 1858.83   533.1 1860.65   547.8 1862.55     600 1872.54
#Mann= 7 ,-1,0
       0      .1       0     140     .06       0     230      .1       0
   270.6    .045       0   333.4      .1       0     460     .05       0
     530      .1       0
Bank Sta=270.6,333.4
XS Rating Curve= 0 ,0
Exp/Cntr(USF)=0,0
Exp/Cntr=0.3,0.1

Type RM Length L Ch R = 1 ,11763   ,191.3,187.7,186
XS GIS Cut Line= 3
2216113.88081154687604.0951074552216448.42209448687732.561679589
2216704.30136904687835.268257417
#Sta/Elev= 30
       0 1936.29    14.2 1931.94    28.2 1926.23      41 1922.02    62.4 1911.69
     101 1895.89   114.1 1889.97   122.4 1885.35     131 1882.96     161 1869.42
   182.4 1866.73   194.6 1864.32   203.8 1861.22   216.7 1858.96   228.6 1853.11
   246.7 1851.41   255.7 1848.44   263.8 1845.12   272.4 1844.38   302.4 1844.55
   319.5 1846.42     3261848.464   336.7 1852.41   352.5 1854.28   466.3 1856.32
   500.3 1857.84   570.9 1863.45     621 1869.15   629.6 1869.07   634.1 1870.19
#Mann= 4 ,-1,0
       0      .1       0   255.7    .045       0     326     .06       0
  388.36      .1       0
Bank Sta=255.7,326
XS Rating Curve= 0 ,0
Exp/Cntr(USF)=0,0
Exp/Cntr=0.3,0.1

Type RM Length L Ch R = 1 ,11575   ,256.6,262.5,262.4
XS GIS Cut Line= 2
2216042.48273306687804.2185929592216640.02264907687976.917513556
#Sta/Elev= 30
       0 1927.32     1.8 1926.28    10.1 1924.84    22.6 1920.55    79.7 1895.98
    95.8 1888.15   126.7 1877.91   139.2 1872.54   160.4 1868.95   189.1 1860.65
   205.8 1859.49   218.3 1857.11   234.9  1856.7   239.1  1855.1   248.61848.281
   251.6 1845.92   255.7 1844.36   264.1 1844.06   297.4 1844.13   313.71848.322
   320.4 1849.19   330.7 1851.67   355.7 1851.11     389 1855.38   459.8  1857.6
   472.3 1859.61   502.8 1861.42   522.3 1863.82   538.9 1864.83     622 1877.37
#Mann= 5 ,-1,0
       0      .1       0     190     .06       0   248.6    .045       0
   313.7     .06       0     350      .1       0
Bank Sta=248.6,313.7
XS Rating Curve= 0 ,0
Exp/Cntr(USF)=0,0
Exp/Cntr=0.3,0.1

Type RM Length L Ch R = 1 ,11312   ,304.7,328.7,357.1
XS GIS Cut Line= 4
2216000.48470706 688052.027117842216041.22297344688064.237863082
2216497.63041409688208.842200713 2216562.8657402688231.870591605
#Sta/Elev= 30
       0 1893.19    49.8  1876.6    67.9 1869.28    74.3 1867.55   100.2 1866.01
   121.2 1858.21   176.3  1857.3   209.3 1858.41   213.5 1857.36   217.7 1854.84
   224.9 1848.27   230.2 1844.42   234.4 1843.97   270.8 1843.75   280.6  1843.9
   293.2 1847.34   305.8 1846.09     310 1846.37   316.1  1848.2   322.8 1849.93
   335.1  1850.8   381.3 1852.44   414.9 1857.23   452.6  1869.1   465.2 1870.79
   477.8 1875.39   515.6 1884.57   536.7 1890.61   562.2 1898.55   590.5 1909.56
#Mann= 3 ,-1,0
       0     .06       0   224.9    .045       0   316.1      .1       0
Bank Sta=224.9,316.1
XS Rating Curve= 0 ,0
Exp/Cntr(USF)=0,0
Exp/Cntr=0.3,0.1

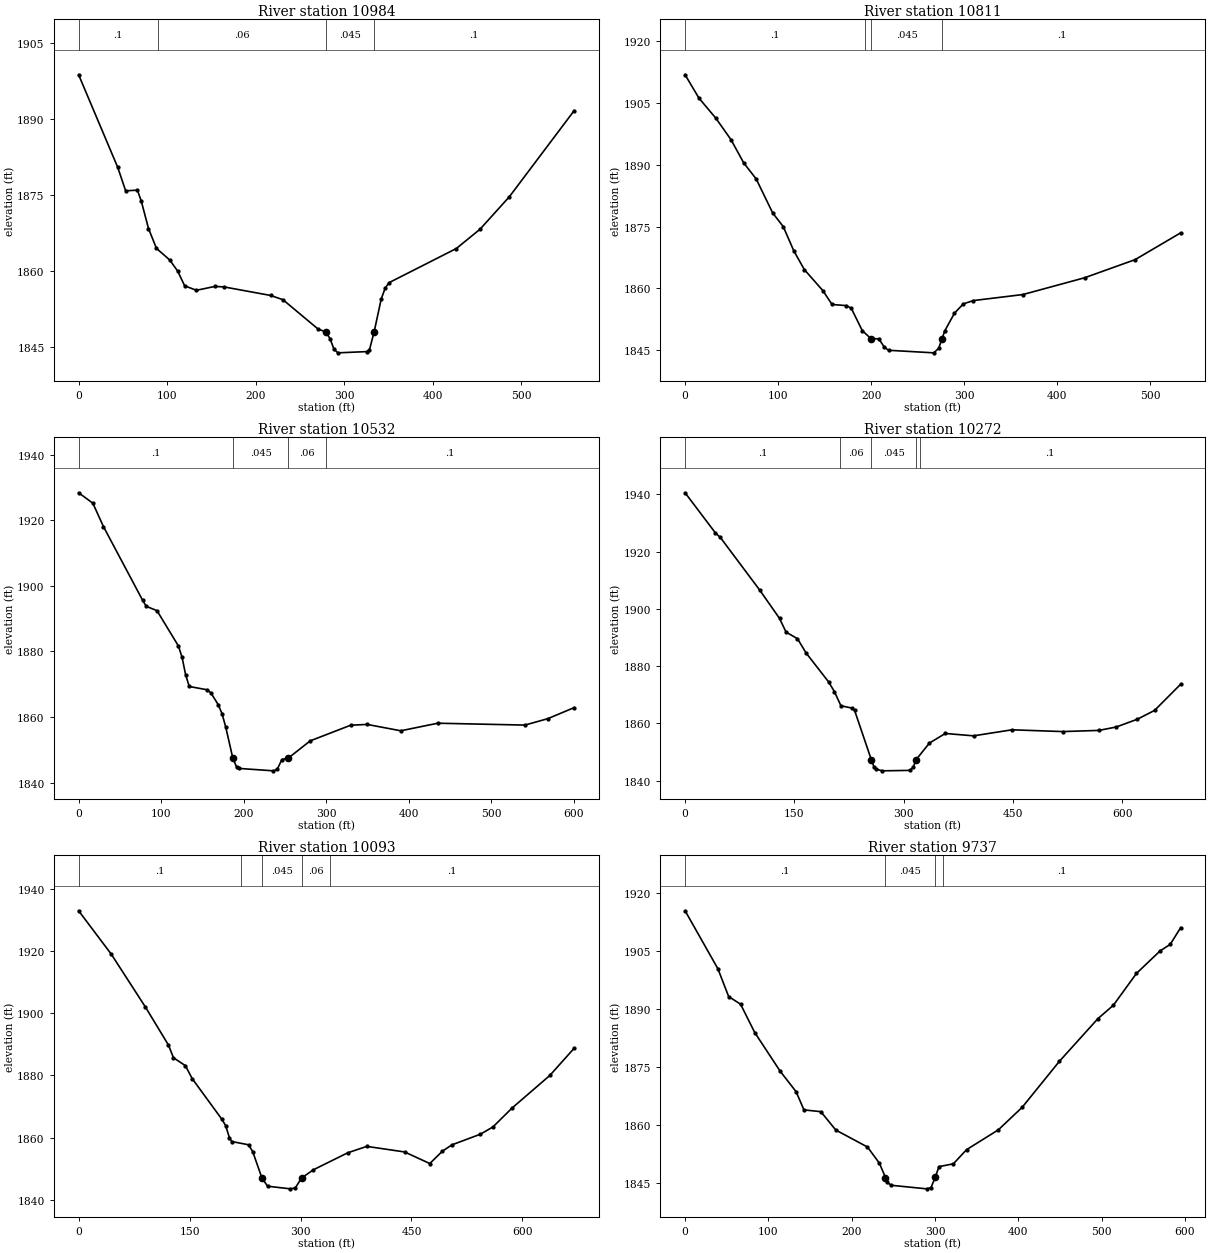
Type RM Length L Ch R = 1 ,10984   ,188.3,173,156.1
XS GIS Cut Line= 4
2215944.82778939688094.3326925462215959.31643537688119.681609522
2216132.03828311688478.1798632532216249.52930744688539.435867392
#Sta/Elev= 30
       0 1898.68    44.2 1880.42    53.1 1875.82    66.4 1875.95    70.8 1873.76
    78.9 1868.39    87.9 1864.48   102.9 1862.19   111.9 1859.99   119.7 1857.11
     133 1856.22   153.8 1856.98   164.1 1856.89   216.7 1855.21   230.7 1854.37
   270.6 1848.56   279.11848.036   283.9 1846.69   288.4  1844.6   292.8  1843.9
   326.1 1844.15   328.3 1844.41   333.71848.041   341.7  1854.5   346.1 1856.63
   350.5 1857.72   426.5 1864.45   453.2 1868.24   486.4 1874.65   559.6 1891.62
#Mann= 4 ,-1,0
       0      .1       0    89.2     .06       0   279.1    .045       0
   333.7      .1       0
Bank Sta=279.1,333.7
XS Rating Curve= 0 ,0
Exp/Cntr(USF)=0,0
Exp/Cntr=0.3,0.1

Type RM Length L Ch R = 1 ,10811   ,289.3,279.3,271.5
XS GIS Cut Line= 3
2215743.67299514688264.6485953052215782.77996137688300.162773082
2216136.25723114688624.518335963
#Sta/Elev= 30
       0 1911.91    14.9 1906.24    33.1 1901.35    49.3 1896.16      63 1890.51
    76.4 1886.61    94.2 1878.32   105.5 1875.03   116.8 1869.16   128.1 1864.61
     148  1859.5   157.9 1856.12   173.4 1855.84   178.6  1855.2   190.4 1849.78
   199.91847.789   208.2 1847.79   214.1 1845.75   218.7 1844.99   267.3 1844.37
   272.5 1845.46   276.21847.806   279.1 1849.71   289.5    1854     299 1856.26
   309.9 1857.07   363.1 1858.53   429.3  1862.6   483.6    1867   532.6 1873.51
#Mann= 4 ,-1,0
       0      .1       0  192.83     .06       0   199.9    .045       0
   276.2      .1       0
Bank Sta=199.9,276.2
XS Rating Curve= 0 ,0
Exp/Cntr(USF)=0,0
Exp/Cntr=0.3,0.1

Type RM Length L Ch R = 1 ,10532   ,289,259.6,229.6
XS GIS Cut Line= 5
2215512.28650058688525.0452652882215616.60226219688567.743311082
2215650.34558396 688582.534848612215808.32863457688659.982802948
2216078.50975117688712.236153211
#Sta/Elev= 30
       0 1928.38    17.2 1925.21    30.1 1918.07    77.7 1895.54      82 1893.77
      95 1892.43     121 1881.66   125.4 1878.21   129.7 1872.89   134.1 1869.32
   156.1  1868.3   160.5  1867.3   169.4  1863.7   173.9 1860.96   178.3 1856.96
   186.91847.476   191.7 1844.63   194.8 1844.33   236.2  1843.6   240.7 1844.04
   246.4 1847.04   254.31847.515   280.8 1852.75   329.8 1857.51   349.8 1857.75
   390.5 1855.81   435.3 1858.12     541 1857.55   568.8 1859.51   600.7 1862.88
#Mann= 4 ,-1,0
       0      .1       0   186.9    .045       0   254.3     .06       0
  299.56      .1       0
Bank Sta=186.9,254.3
XS Rating Curve= 0 ,0
Exp/Cntr(USF)=0,0
Exp/Cntr=0.3,0.1

Type RM Length L Ch R = 1 ,10272   ,193,178.8,168.2
XS GIS Cut Line= 4
2215505.30969773688982.488445989 2215657.9104502688902.746476063
 2215878.8337438688793.4006034712216134.56401112688738.270221115
#Sta/Elev= 30
       0 1940.55    41.6 1926.53    48.4 1924.93   102.5 1906.52   129.6 1896.66
   138.6 1891.86   154.3 1889.55   166.1 1884.57     197 1874.46   204.9  1871.1
   213.9 1866.13   228.8 1865.32   232.7 1864.48   255.6 1847.31   259.5 1844.63
   261.6 1844.05   270.6 1843.38   308.6 1843.54   313.1 1844.61   317.2 1847.31
   335.4 1853.08   357.2 1856.44     396 1855.61   448.7 1857.72   518.3  1857.1
   568.1 1857.51   591.9  1858.7   620.6 1861.39   644.5 1864.49   680.3 1873.64
#Mann= 5 ,-1,0
       0      .1       0  212.18     .06       0   255.6    .045       0
   317.2     .06       0  322.18      .1       0
Bank Sta=255.6,317.2
XS Rating Curve= 0 ,0
Exp/Cntr(USF)=0,0
Exp/Cntr=0.3,0.1

Type RM Length L Ch R = 1 ,10093   ,341.9,356.2,346.3
XS GIS Cut Line= 4
  2215709.331411689201.0027883132215770.36448967689121.845190011
2215963.17027318688884.854747782 2216210.9933561688792.409180534
#Sta/Elev= 30
       0    1933      44 1919.08    90.3 1902.03   121.4 1889.82   128.2 1885.71
   144.4 1883.16   153.5 1879.01   193.6 1865.94   198.8 1863.87   203.9 1859.96
   206.9 1858.76   229.7 1857.71   235.4 1855.48   247.81847.045   255.5 1844.37
   286.4 1843.53     293 1843.84   301.41847.003   317.4 1849.66   363.8 1855.12
   389.6 1857.19   440.7  1855.4   474.8 1851.67   491.9 1855.66   504.7 1857.68
   543.2 1861.11   560.2 1863.45   585.8 1869.48   637.1 1880.02     670 1888.77
#Mann= 5 ,-1,0
       0      .1       0  219.95     .06       0   247.8    .045       0
   301.4     .06       0  339.95      .1       0
Bank Sta=247.8,301.4
XS Rating Curve= 0 ,0
Exp/Cntr(USF)=0,0
Exp/Cntr=0.3,0.1

Type RM Length L Ch R = 1 ,9737    ,237.6,247.6,246.8
XS GIS Cut Line= 2
2216010.81893265689377.1275922342216333.60355966688877.351897024
#Sta/Elev= 30
       0  1915.5    39.4 1900.46    52.3 1893.26    66.6 1891.28    83.6 1883.94
   114.2  1873.9   133.3 1868.59   142.7 1863.88     163 1863.42   180.9 1858.66
     219 1854.25   233.3 1850.06   240.61846.342   242.8 1845.07   247.5 1844.33
     290 1843.41   295.2 1843.71   300.31846.352   304.8 1849.16   322.1  1849.9
     338 1853.57   376.1  1858.7   404.7 1864.54   449.4 1876.47   495.7 1887.54
   514.2    1891     542 1899.27   570.2 1905.07   582.5 1906.79     595 1911.12
#Mann= 4 ,-1,0
       0      .1       0   240.6    .045       0   300.3     .06       0
     310      .1       0
Bank Sta=240.6,300.3
XS Rating Curve= 0 ,0
Exp/Cntr(USF)=0,0
Exp/Cntr=0.3,0.1

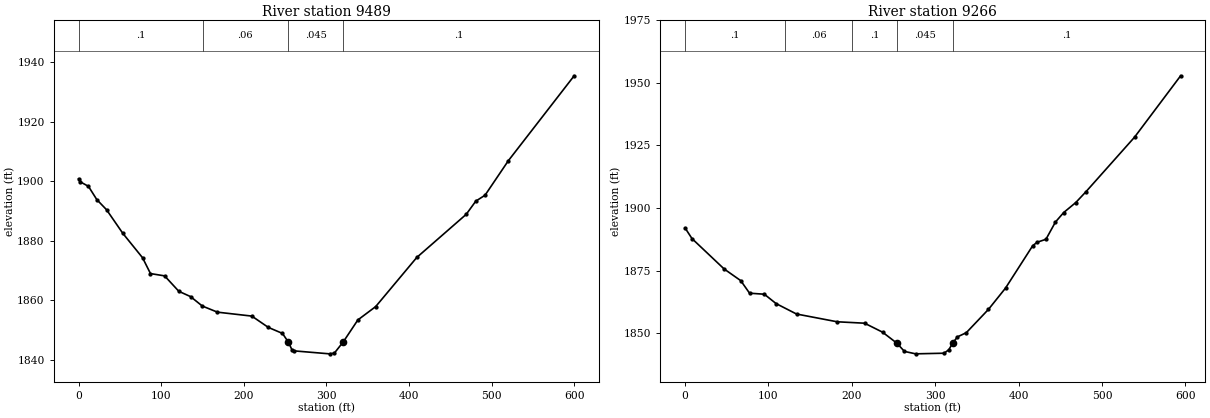
Type RM Length L Ch R = 1 ,9489    ,215.9,223.1,222.3
XS GIS Cut Line= 2
2216187.59503537  689498.6041971 2216552.6505321689022.437751086
#Sta/Elev= 30
       0 1900.83     1.8 1899.87    11.9 1898.31      22 1893.87    33.8 1890.46
    53.5 1882.53    77.4 1874.33      87 1869.01   104.1 1868.24   121.3 1863.06
   135.5 1861.28   149.8  1858.1   168.1 1856.05   209.7 1854.73   229.7 1850.93
   246.8 1848.91   253.7 1846.09   258.2 1843.48   261.1 1843.04   303.8 1842.05
   309.6 1842.28   320.51846.096   338.1 1853.44   359.7 1857.93   409.4 1874.42
   469.3 1888.92   480.9 1893.35   492.1 1895.34   520.3 1906.93     600 1935.46
#Mann= 4 ,-1,0
       0      .1       0     150     .06       0   253.7    .045       0
   320.5      .1       0
Bank Sta=253.7,320.5
XS Rating Curve= 0 ,0
Exp/Cntr(USF)=0,0
Exp/Cntr=0.3,0.1

Type RM Length L Ch R = 1 ,9266    ,251.3,272.9,272.2
XS GIS Cut Line= 2
2216348.38712023689615.4279557642216738.79157676689167.424543311
#Sta/Elev= 30
       0 1892.03     8.3 1887.78    46.8 1875.66    66.7    1871    77.3 1865.98
      95 1865.57   109.1 1861.83   133.6 1857.66   182.3 1854.56   215.2 1853.99
   236.8  1850.4   254.11845.965     263 1842.72   276.4 1841.75   310.5    1842
   316.3 1843.41   320.71845.973   326.6 1848.54   337.2  1850.2   363.8 1859.53
   384.2 1868.01   416.8 1884.94   422.1 1886.33   432.7 1887.52   444.1 1894.42
     454 1898.21   468.5 1902.21   480.7 1906.53   538.9  1928.3   594.2 1952.84
#Mann= 5 ,-1,0
       0      .1       0     120     .06       0     200      .1       0
   254.1    .045       0   320.7      .1       0
Bank Sta=254.1,320.7
XS Rating Curve= 0 ,0
Exp/Cntr(USF)=0,0
Exp/Cntr=0.3,0.1