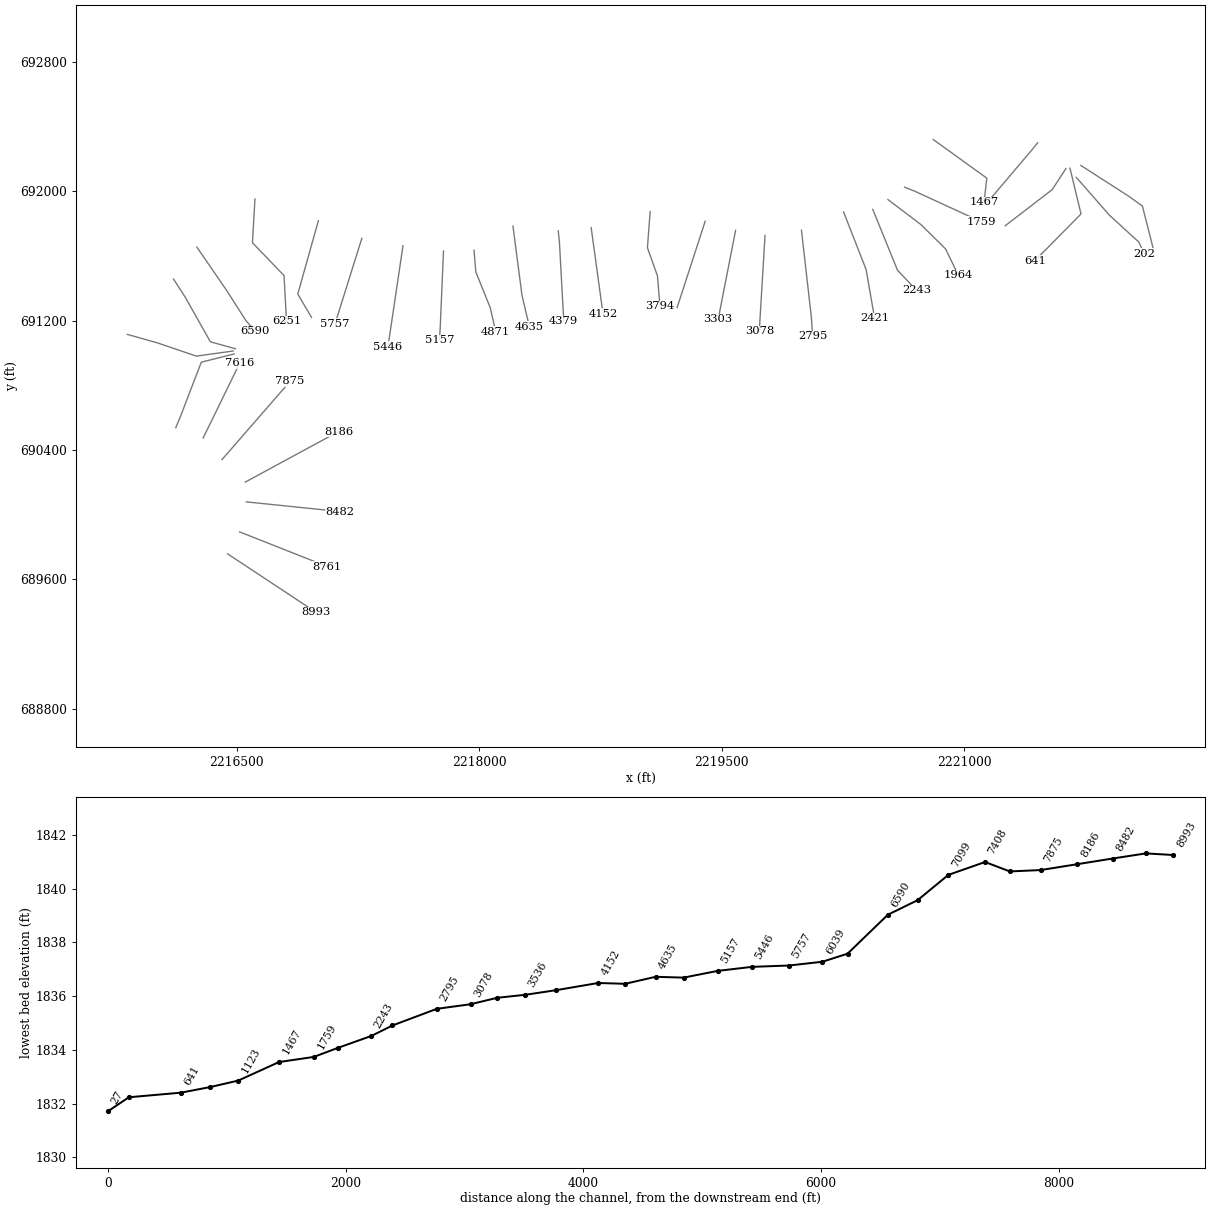
HEC-RAS study RFMIDDLERV.prj: RFMIDDLERV

--- RFMIDDLERV.g01 (geometry) --- (continued)

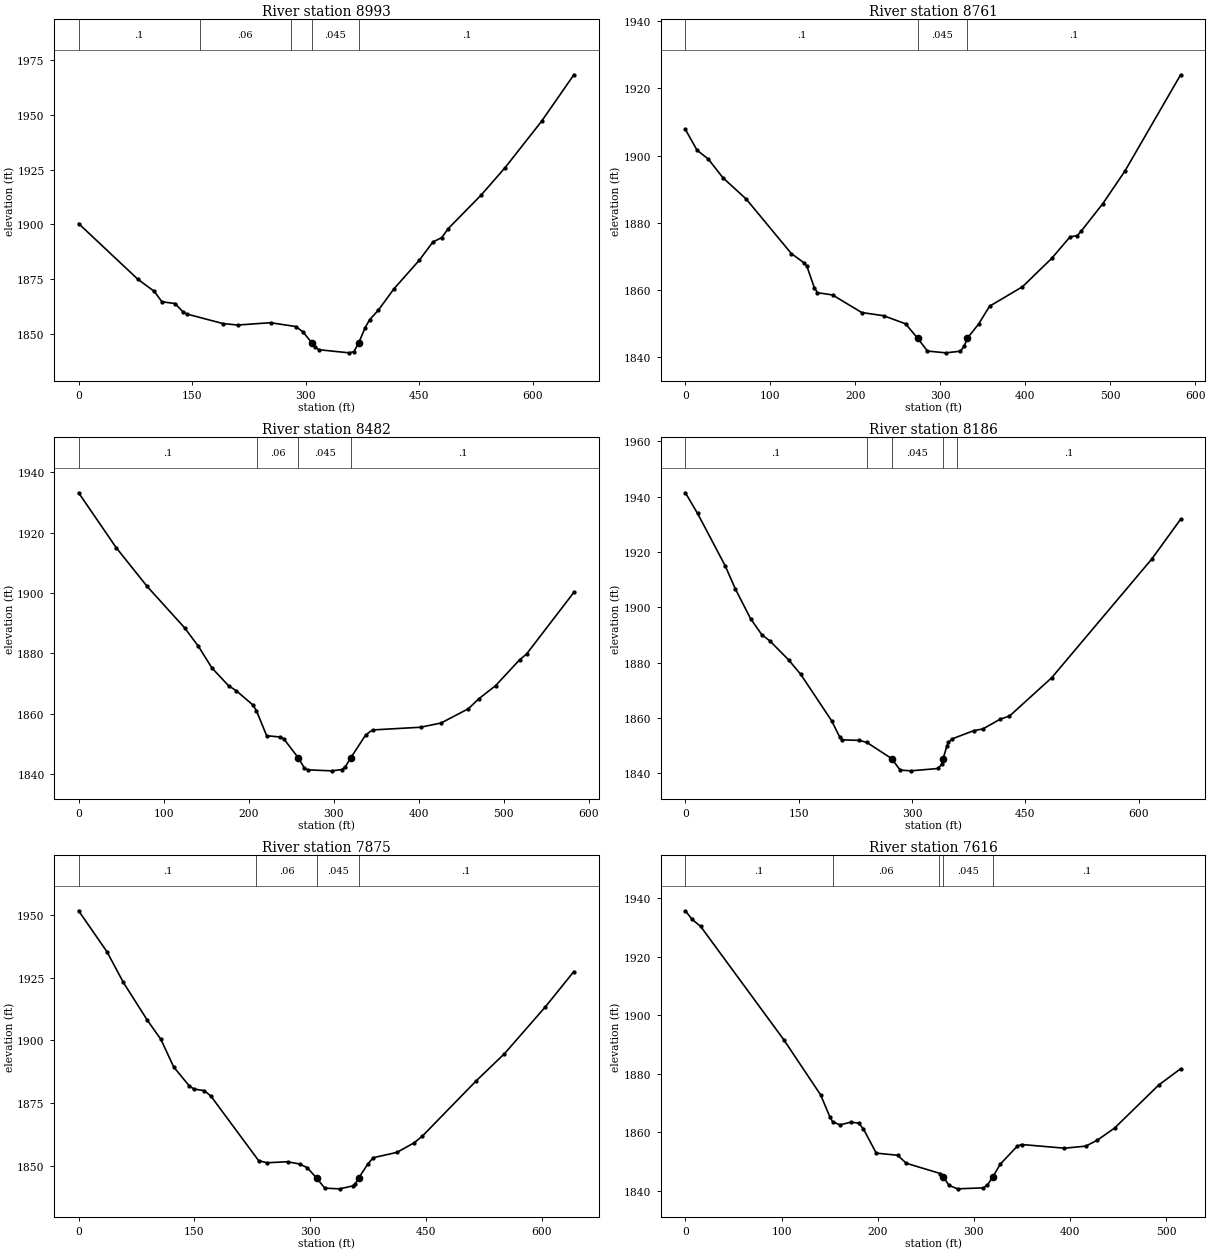
Type RM Length L Ch R = 1 ,8993    ,220,232.2,233.4
XS GIS Cut Line= 2
2216444.80216323689758.1855948892216990.46664601689397.601262283
#Sta/Elev= 30
       0 1900.36    78.2 1874.91    99.9 1869.36     110  1864.6   127.3  1863.8
   138.3 1859.81   143.1 1858.98   190.8 1854.62   210.2 1853.97   253.4 1855.03
   286.9 1853.27   296.5 1850.76     3081845.811     312 1843.86   317.8 1842.65
   357.3 1841.25   363.6 1841.81     3701845.897   378.4 1852.77   384.2 1856.35
   395.8 1860.75   416.4 1870.52   449.9 1883.61   467.9 1891.96   479.5 1893.94
   488.1 1898.05   531.5 1913.38   563.2 1925.95   611.3 1947.12     654 1968.41
#Mann= 5 ,-1,0
       0      .1       0     160     .06       0     280      .1       0
     308    .045       0     370      .1       0
Bank Sta=308,370
XS Rating Curve= 0 ,0
Exp/Cntr(USF)=0,0
Exp/Cntr=0.3,0.1

Type RM Length L Ch R = 1 ,8761    ,271.6,279.5,286.3
XS GIS Cut Line= 2
2216519.10260419689893.9332737872217061.30119289689679.666527303
#Sta/Elev= 30
       0 1907.75    13.7 1901.59      27 1898.93    44.2 1893.38    71.7 1887.02
   124.7 1870.84   140.1 1868.01   143.1 1867.02   151.7 1860.74   155.5  1859.2
   173.2 1858.53   207.6  1853.3   233.4 1852.35   259.2 1849.94   273.31845.682
     285 1841.84   306.5 1841.31   323.7 1841.79   328.2 1843.29   331.91845.646
   345.2 1849.88   358.1 1855.18   396.8 1860.96   431.3 1869.42   452.8 1875.81
   461.4 1876.19   465.7 1877.43   491.5 1885.72   517.3 1895.32     583 1924.01
#Mann= 3 ,-1,0
       0      .1       0   273.3    .045       0   331.9      .1       0
Bank Sta=273.3,331.9
XS Rating Curve= 0 ,0
Exp/Cntr(USF)=0,0
Exp/Cntr=0.3,0.1

Type RM Length L Ch R = 1 ,8482    ,282,295.9,321
XS GIS Cut Line= 2
2216560.25863047 690079.675275082217139.52448371690020.073323848
#Sta/Elev= 30
       0 1933.17    44.1 1915.03    80.3 1902.26   124.6 1888.47   140.7 1882.41
   156.7  1875.2   176.4 1869.27   185.4 1867.64     205  1862.9     209 1861.08
   221.1 1852.75   237.2 1852.31   241.2 1851.72   258.11845.507   265.3 1842.13
   269.3 1841.45   297.5 1841.12   309.5 1841.54   313.6 1842.49   320.21845.519
   337.6 1853.04   345.7 1854.66     402 1855.55   426.2 1856.96   458.3 1861.68
   470.4 1864.94   490.2  1869.3   518.6  1877.9   526.7 1879.79   582.3  1900.2
#Mann= 4 ,-1,0
       0      .1       0     210     .06       0   258.1    .045       0
   320.2      .1       0
Bank Sta=258.1,320.2
XS Rating Curve= 0 ,0
Exp/Cntr(USF)=0,0
Exp/Cntr=0.3,0.1

Type RM Length L Ch R = 1 ,8186    ,303.6,311,325.3
XS GIS Cut Line= 2
2216554.05657801690201.9978561152217130.23799819690514.337018082
#Sta/Elev= 30
       0 1941.44    16.1 1933.98    52.5 1915.14    66.1 1906.69    86.5 1895.81
   101.3 1890.08   111.6 1887.94   136.5 1881.06   152.6 1875.82   193.5 1859.02
   204.5 1852.99   207.5 1852.11   229.9 1851.92   239.9 1851.22   272.81845.371
   284.2  1841.2   298.2 1840.91   334.6 1841.76   339.1 1843.33   341.11845.343
   346.2 1849.98   348.2 1851.18   352.8 1852.44   381.6 1855.44   393.7 1856.06
     417 1859.65   428.8 1860.68   484.7 1874.55   617.6 1917.62   655.4 1931.88
#Mann= 5 ,-1,0
       0      .1       0     240     .06       0   272.8    .045       0
   341.1     .06       0     360      .1       0
Bank Sta=272.8,341.1
XS Rating Curve= 0 ,0
Exp/Cntr(USF)=0,0
Exp/Cntr=0.3,0.1

Type RM Length L Ch R = 1 ,7875    ,250.2,258.9,263
XS GIS Cut Line= 2
2216410.18352678690341.4215397852216831.24591206690825.095973487
#Sta/Elev= 30
       0 1951.77    36.8 1935.36    57.9 1923.16    89.1    1908   106.6 1900.36
   123.2 1889.33   143.1 1881.89   149.2 1880.56   162.8 1879.92   171.4  1877.7
     233 1851.99   243.6 1851.11   270.6 1851.51   286.1 1850.61   296.1 1849.14
   308.11845.032   318.8 1840.96   338.1 1840.69     355 1841.86   358.5 1842.77
   362.71845.054   374.6 1850.65   381.5 1853.12   412.3 1855.27   434.6  1859.1
   445.2 1861.77   514.4  1883.7   551.3 1894.63   604.3 1913.35   641.3  1927.5
#Mann= 4 ,-1,0
       0      .1       0     230     .06       0   308.1    .045       0
   362.7      .1       0
Bank Sta=308.1,362.7
XS Rating Curve= 0 ,0
Exp/Cntr(USF)=0,0
Exp/Cntr=0.3,0.1

Type RM Length L Ch R = 1 ,7616    ,204.9,208,209.6
XS GIS Cut Line= 3
 2216293.2341443690474.9692542062216334.80789137690559.020525454
2216519.44157907690937.775387942
#Sta/Elev= 30
       0 1935.72     6.9  1932.8    15.9 1930.36   102.4  1891.6   140.7 1872.75
   150.3 1865.23   153.2 1863.57   160.8 1862.51   171.8 1863.42   180.2 1863.13
   185.2  1861.1   198.5 1852.85   220.8 1852.13   229.7 1849.39   265.3 1845.86
   268.41844.712   274.2 1841.81   283.1 1840.64   309.8 1840.98   314.2 1841.98
   319.71844.707   327.6 1849.12   345.4 1855.29   349.8  1855.8   394.3 1854.54
   416.4 1855.24   428.5 1857.29   446.4 1861.42   492.2 1876.11   515.1  1881.7
#Mann= 5 ,-1,0
       0      .1       0  153.77     .06       0  263.77      .1       0
   268.4    .045       0   319.7      .1       0
Bank Sta=268.4,319.7
XS Rating Curve= 0 ,0
Exp/Cntr(USF)=0,0
Exp/Cntr=0.3,0.1

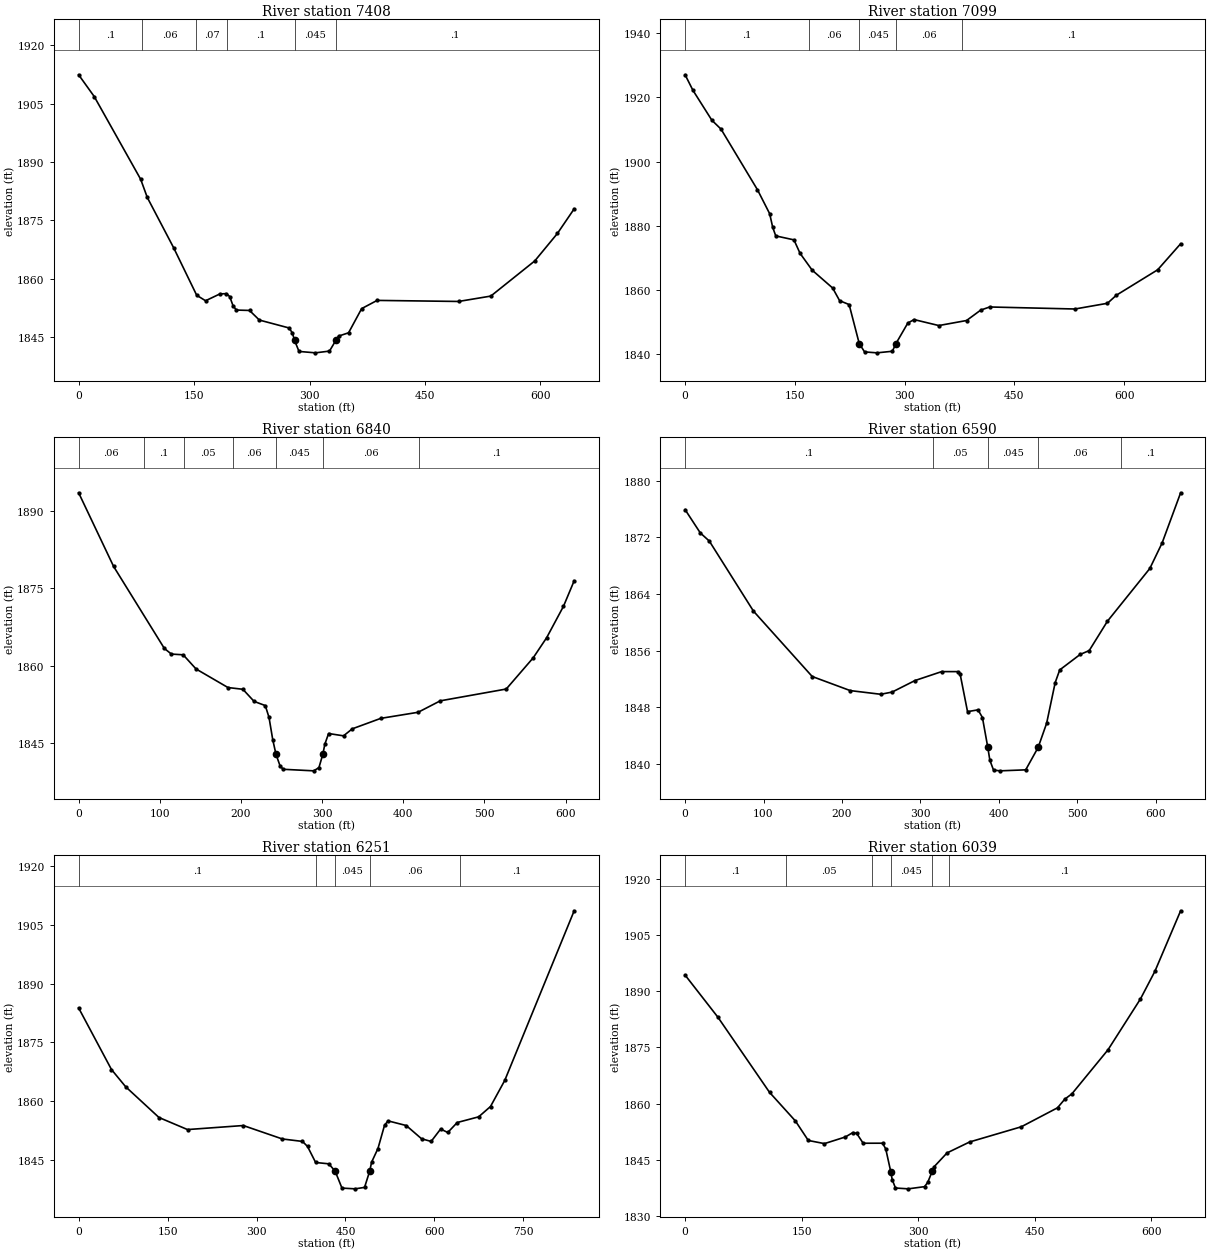
Type RM Length L Ch R = 1 ,7408    ,346.9,309.2,269.4
XS GIS Cut Line= 4
2216124.34697836 690538.727623072216152.46448845 690606.00880794
2216282.00587425690943.4189290782216485.13870728690994.326342813
#Sta/Elev= 30
       0 1912.42    20.3 1906.82    80.6 1885.58    89.2  1880.9   123.4    1868
   153.4 1855.78   164.9 1854.37   183.5 1856.12     192  1856.2   196.3 1855.44
   200.6 1853.09   204.9 1851.98     222 1851.88   234.8 1849.41   273.4 1847.38
   277.7 1846.09   280.51844.206   286.3 1841.35   307.7 1840.99   325.9 1841.44
   334.21844.201   337.7 1845.29   350.7 1846.14   367.7 1852.35   387.8 1854.46
   493.6 1854.19   535.5 1855.57   592.6  1864.6     622 1871.65   643.8 1877.98
#Mann= 6 ,-1,0
       0      .1       0   82.92     .06       0  152.92     .07       0
  192.92      .1       0   280.5    .045       0   334.2      .1       0
Bank Sta=280.5,334.2
XS Rating Curve= 0 ,0
Exp/Cntr(USF)=0,0
Exp/Cntr=0.3,0.1

Type RM Length L Ch R = 1 ,7099    ,279.6,258.3,241.1
XS GIS Cut Line= 4
2215824.92482047691115.1490195412216006.66780297691064.062130339
2216251.59139984690980.9146362012216479.21014055691012.757175215
#Sta/Elev= 30
       0 1927.03    10.7  1922.2    36.6 1912.88    49.1 1910.12    98.9 1891.26
   115.6  1883.8   119.7  1879.6   123.9  1876.9   148.8 1875.66   157.1 1871.48
   173.7 1866.23   201.7 1860.67   211.2 1856.74   224.2 1855.53     2381843.408
   245.3  1840.8   262.2 1840.51   283.3    1841   288.2  1843.4   304.4 1849.77
   312.9 1850.86   346.8    1849   384.7 1850.57     404  1853.8   416.2 1854.78
   532.8 1854.15   577.3 1855.93   589.4 1858.43   645.9 1866.35   677.3 1874.45
#Mann= 5 ,-1,0
       0      .1       0     170     .06       0     238    .045       0
   288.2     .06       0  378.79      .1       0
Bank Sta=238,288.2
XS Rating Curve= 0 ,0
Exp/Cntr(USF)=0,0
Exp/Cntr=0.3,0.1

Type RM Length L Ch R = 1 ,6840    ,250.8,250.2,255.7
XS GIS Cut Line= 4
2216110.21298245691457.3145138482216180.89044329691348.382575264
2216338.21460692691069.4390227352216492.87474815691026.534793725
#Sta/Elev= 30
       0 1893.51    43.1 1879.22   105.6 1863.32   114.3 1862.22   128.8 1862.08
   144.7 1859.33     184 1855.73   202.4 1855.39   216.2 1853.04     230 1852.23
   234.6 1849.93   239.2  1845.6   243.21842.763   248.3 1840.49   252.1 1839.87
   289.7 1839.57   296.1  1840.2   300.91842.785   303.4 1844.75     308 1846.81
   326.4 1846.36   337.2 1847.72   372.3 1849.75   418.3 1850.93   445.6 1853.15
   526.9 1855.44   560.1 1861.49   576.7  1865.4   597.4 1871.48   610.6 1876.44
#Mann= 7 ,-1,0
       0     .06       0      80      .1       0  129.85     .05       0
  189.85     .06       0   243.2    .045       0   300.9     .06       0
  419.85      .1       0
Bank Sta=243.2,300.9
XS Rating Curve= 0 ,0
Exp/Cntr(USF)=0,0
Exp/Cntr=0.3,0.1

Type RM Length L Ch R = 1 ,6590    ,333.9,339.4,346.3
XS GIS Cut Line= 4
2216254.73969657691654.7184611782216433.89415863691394.256353899
2216557.74509595 691201.227415552216613.58662025691135.133889287
#Sta/Elev= 30
       0 1875.91    19.4 1872.62    30.9 1871.47    87.2 1861.58   162.1 1852.35
   210.6 1850.36   249.5 1849.84     264 1850.15   293.2 1851.78   327.2 1853.04
   347.5 1853.04   350.7 1852.73   360.2 1847.39   373.6 1847.64   379.2 1846.56
     3861842.375   388.7 1840.52   393.4 1839.13   401.8 1839.03   434.4 1839.17
   450.31842.345   461.1 1845.75     472 1851.49   477.8 1853.28   503.8 1855.46
   515.4 1856.01   538.6 1860.15   592.7  1867.6   608.4 1871.21     632 1878.29
#Mann= 5 ,-1,0
       0      .1       0  316.13     .05       0     386    .045       0
   450.3     .06       0  555.47      .1       0
Bank Sta=386,450.3
XS Rating Curve= 0 ,0
Exp/Cntr(USF)=0,0
Exp/Cntr=0.3,0.1

Type RM Length L Ch R = 1 ,6251    ,238.7,211.7,178.8
XS GIS Cut Line= 4
2216613.81461367691952.4919214992216598.30189258691682.110153975
2216793.56237935691479.039247735   2216808.78258691196.279586939
#Sta/Elev= 30
       0 1883.78    55.4 1868.05    79.4 1863.64   135.5  1855.8   183.6 1852.72
   277.7 1853.75   343.5 1850.32   377.5 1849.69     386 1848.41   399.7 1844.31
   421.9 1843.97   432.61842.095   444.1 1837.77   466.3 1837.58   482.2 1837.95
   490.91842.131   494.1  1844.4   504.8 1847.88   515.9 1853.82   521.8 1854.94
   552.5 1853.75   578.4 1850.36   594.5 1849.69   610.5 1852.86   622.5 1851.97
   638.5 1854.52   674.6 1855.97   694.6 1858.61   718.6 1865.26   835.7  1908.6
#Mann= 5 ,-1,0
       0      .1       0  400.83     .06       0   432.6    .045       0
   490.9     .06       0  642.54      .1       0
Bank Sta=432.6,490.9
XS Rating Curve= 0 ,0
Exp/Cntr(USF)=0,0
Exp/Cntr=0.3,0.1

Type RM Length L Ch R = 1 ,6039    ,281.7,282.3,280.3
XS GIS Cut Line= 3
2217005.84372216691817.8642892452216878.53210572691364.555164024
2216963.33673142691220.621349182
#Sta/Elev= 30
       0 1894.28    42.3 1883.03   108.7 1863.01     142 1855.38   158.6 1850.18
   179.4 1849.34   206.3 1851.11     216 1852.29   220.9 1852.06   229.2 1849.44
   254.2 1849.45   258.3 1847.92   264.7  1841.9   266.6 1839.75   270.8  1837.5
   287.2 1837.28   308.2 1837.86   312.3 1838.99   318.11841.938   320.6 1843.18
   337.2 1846.86   366.3 1849.78   432.8 1853.83   479.4 1858.89   488.7 1861.18
     498 1862.63   544.4 1874.36   586.2 1887.93   604.8  1895.3   637.9 1911.43
#Mann= 6 ,-1,0
       0      .1       0     130     .05       0     240     .07       0
   264.7    .045       0   318.1     .07       0     340      .1       0
Bank Sta=264.7,318.1
XS Rating Curve= 0 ,0
Exp/Cntr(USF)=0,0
Exp/Cntr=0.3,0.1

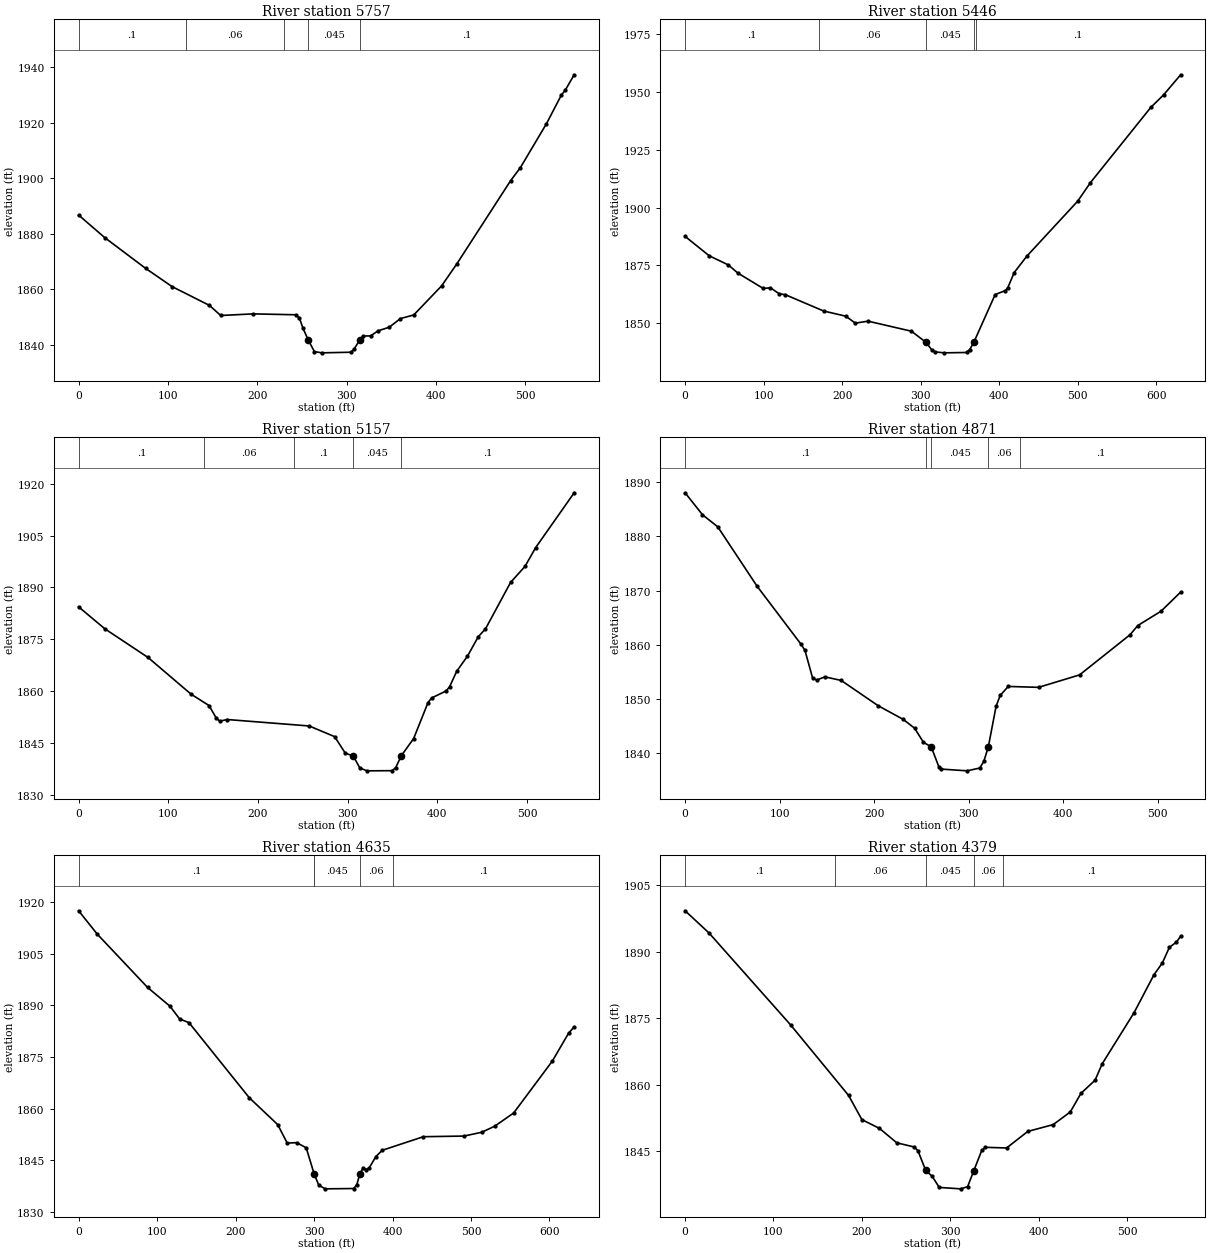
Type RM Length L Ch R = 1 ,5757    ,305.2,311.1,314.9
XS GIS Cut Line= 2
2217274.64358792691708.9912866172217108.69002816 691179.59910737
#Sta/Elev= 30
       0  1886.8    29.1  1878.7    75.1 1867.56   104.6 1861.02   146.5 1854.23
   159.1  1850.6   195.5 1851.18   242.9 1850.86   247.1 1849.72   251.3 1845.92
   257.1 1841.76   263.9  1837.6   272.3 1837.14     305 1837.36   308.2 1838.37
   314.6 1841.76   318.4 1843.22   326.8 1843.23   335.2 1845.07   347.7 1846.36
   360.3 1849.49   375.2  1850.8   406.4 1861.28   423.4  1869.2   483.7 1899.23
   494.5 1903.85   523.8 1919.74   540.6 1930.13   544.8 1931.79   554.8 1937.36
#Mann= 5 ,-1,0
       0      .1       0     120     .06       0     230      .1       0
   257.1    .045       0   314.6      .1       0
Bank Sta=257.1,314.6
XS Rating Curve= 0 ,0
Exp/Cntr(USF)=0,0
Exp/Cntr=0.3,0.1

Type RM Length L Ch R = 1 ,5446    ,285,288.4,290.9
XS GIS Cut Line= 2
2217529.17248648691663.5514310512217436.27672235691039.640064474
#Sta/Elev= 30
       0 1887.53    30.7 1879.14      55 1875.18    67.1 1871.66    99.5 1864.97
   108.6 1865.27   119.7  1862.7   127.8 1862.25   176.3 1855.22   204.6 1852.96
   216.7 1849.95   232.9 1850.81   288.1 1846.46   306.91841.585   313.8 1838.43
   317.8 1837.53   329.5 1837.09   358.3 1837.24   362.3  1838.5   367.51841.629
   394.7 1862.34   407.8 1864.07   410.9 1865.39   418.9 1871.86   435.1    1879
   499.8 1902.82     516 1910.84   592.8  1943.4     609 1948.81   630.8 1957.55
#Mann= 5 ,-1,0
       0      .1       0     170     .06       0   306.9    .045       0
   367.5     .06       0     370      .1       0
Bank Sta=306.9,367.5
XS Rating Curve= 0 ,0
Exp/Cntr(USF)=0,0
Exp/Cntr=0.3,0.1

Type RM Length L Ch R = 1 ,5157    ,272.8,286.1,296.2
XS GIS Cut Line= 3
2217779.60863825691630.4160584292217759.17322716691153.823556417
2217754.49209119691078.426819808
#Sta/Elev= 30
       0 1884.37    29.3 1878.01    77.4 1869.73   125.4 1859.11   145.4 1855.83
   153.4 1852.23   157.4 1851.28   165.4 1851.79   257.1 1849.92   285.5 1846.83
   297.5 1841.99   306.11841.308   313.5  1837.8   321.5 1836.94   349.6 1836.99
   353.6 1837.88   359.91841.332   373.6 1846.29   389.6 1856.67   393.6 1858.02
   409.6 1860.01   413.6 1861.21   421.6 1865.74   433.6  1870.1   445.6 1875.72
   453.7    1878   481.7 1891.45   497.7 1896.05   509.7 1901.53   552.6 1917.37
#Mann= 5 ,-1,0
       0      .1       0     140     .06       0     240      .1       0
   306.1    .045       0   359.9      .1       0
Bank Sta=306.1,359.9
XS Rating Curve= 0 ,0
Exp/Cntr(USF)=0,0
Exp/Cntr=0.3,0.1

Type RM Length L Ch R = 1 ,4871    ,245.6,236,232
XS GIS Cut Line= 4
2217968.40116691691635.5615100412217979.54414366 691501.43956783
2218068.91765789691279.5120774392218102.15018878691132.975699718
#Sta/Elev= 30
       0 1888.05    18.4 1883.99    34.5 1881.77    76.1  1870.8   122.8 1860.03
   126.8 1858.92   134.9 1853.81   139.2 1853.46   147.8 1854.05   165.1 1853.39
   203.9 1848.75   230.6  1846.2   242.7 1844.57   252.1 1841.96   260.31841.123
   268.5 1837.38   270.5 1837.02   298.2 1836.69   311.7 1837.21     316 1838.47
   320.71841.118   328.9  1848.6   333.2 1850.61   341.8 1852.28   373.8 1852.11
   417.2 1854.41   470.6 1861.83   478.8 1863.53   503.4 1866.18   524.1  1869.7
#Mann= 5 ,-1,0
       0      .1       0  254.58     .06       0   260.3    .045       0
   320.7     .06       0  354.58      .1       0
Bank Sta=260.3,320.7
XS Rating Curve= 0 ,0
Exp/Cntr(USF)=0,0
Exp/Cntr=0.3,0.1

Type RM Length L Ch R = 1 ,4635    ,260.1,256.5,255.6
XS GIS Cut Line= 3
2218209.15935957691784.7107805692218265.17081127691355.398668778
2218310.84317009691162.198321632
#Sta/Elev= 30
       0 1917.43    23.7 1910.66    87.9 1895.17   116.5 1889.71   128.6 1886.06
   140.7 1884.94   217.4 1863.18   253.7 1855.36   265.8 1850.01   277.9 1850.12
     290 1848.64   300.31840.922   306.1 1837.77   314.2 1836.72   350.5 1836.81
   354.5 1837.91   358.2 1840.93   362.6  1842.8   366.6 1842.27   370.6 1842.91
   378.7 1846.05   386.8  1847.9   439.3 1851.85   491.1 1852.04   513.8 1853.15
   530.4 1854.92   554.4 1858.74   603.8 1873.85   624.3 1881.86   631.5 1883.76
#Mann= 5 ,-1,0
       0      .1       0     300     .06       0   300.3    .045       0
   358.2     .06       0     400      .1       0
Bank Sta=300.3,358.2
XS Rating Curve= 0 ,0
Exp/Cntr(USF)=0,0
Exp/Cntr=0.3,0.1

Type RM Length L Ch R = 1 ,4379    ,225.4,227,230.9
XS GIS Cut Line= 3
2218488.89290723691755.9895812842218496.36293495691687.134106156
2218523.33234635691196.519103607
#Sta/Elev= 30
       0 1899.26      27 1894.26   119.3  1873.5   184.9 1857.57     200 1852.09
   219.9 1850.11   239.5 1846.85   259.5  1845.9   263.5 1845.03   272.2 1840.61
   279.5  1839.3   287.5 1836.78   311.6 1836.46   319.6 1836.94   326.71840.595
   335.6 1845.15   339.6 1845.84   363.7 1845.69   387.7 1849.43   416.5 1850.97
   435.8 1853.83   447.8 1858.02   463.8 1860.99   471.8 1864.68   507.9 1876.24
   530.4  1884.8   539.9 1887.47   547.9 1891.02   555.9 1892.18   560.6 1893.52
#Mann= 5 ,-1,0
       0      .1       0  169.26     .06       0   272.2    .045       0
   326.7     .06       0  359.26      .1       0
Bank Sta=272.2,326.7
XS Rating Curve= 0 ,0
Exp/Cntr(USF)=0,0
Exp/Cntr=0.3,0.1

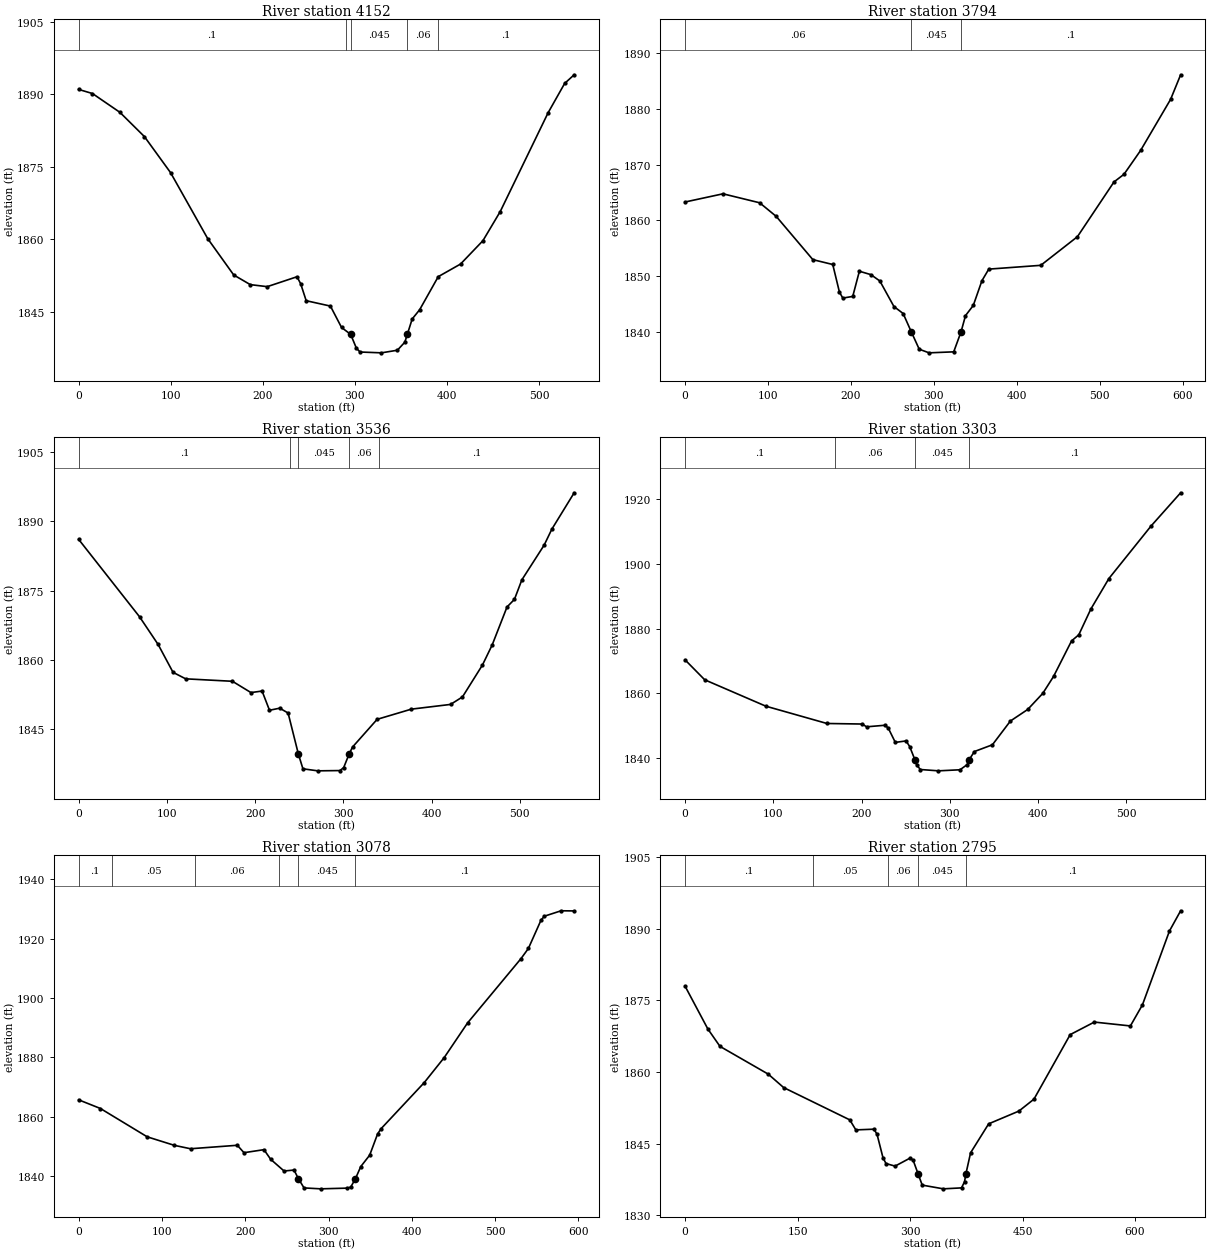
Type RM Length L Ch R = 1 ,4152    ,352.4,357.3,364.8
XS GIS Cut Line= 2
2218692.61404826 691776.058585432218765.78490811 691242.95648449
#Sta/Elev= 30
       0 1891.02      15 1890.17    44.8 1886.28    71.5 1881.24    99.8  1873.8
   140.2 1860.12   168.4 1852.61   186.4 1850.61   204.8 1850.19   237.1 1852.24
   241.1  1850.8   247.1 1847.28   273.4 1846.17   285.5 1841.74   295.41840.314
   301.7 1837.41   305.7 1836.66   328.8 1836.49   346.1 1837.03   354.2 1838.69
   356.91840.301   362.2  1843.5   370.3 1845.41   390.5 1852.26   414.7 1854.87
     439  1859.7   457.8 1865.73   509.8 1886.19   527.8 1892.27   538.1 1894.05
#Mann= 5 ,-1,0
       0      .1       0     290     .06       0   295.4    .045       0
   356.9     .06       0     390      .1       0
Bank Sta=295.4,356.9
XS Rating Curve= 0 ,0
Exp/Cntr(USF)=0,0
Exp/Cntr=0.3,0.1

Type RM Length L Ch R = 1 ,3794    ,278.6,258.1,240.4
XS GIS Cut Line= 4
2219057.54864647691874.7973054742219040.62351354691651.313009292
2219102.59036082691477.2470441012219118.20909938691289.061942697
#Sta/Elev= 30
       0  1863.3    45.7 1864.77    89.9 1863.16   109.9 1860.72   154.1 1852.95
   178.1 1852.08   186.1 1847.15   190.2 1846.05   202.2 1846.35   210.2 1850.87
   224.1 1850.26   234.9 1849.12   251.9 1844.53     263 1843.28   272.71840.036
   282.4 1836.87   294.3 1836.22     324  1836.4   332.91840.018   338.2  1842.9
   347.6 1844.73     358 1849.16   366.3 1851.25     429 1851.93   473.2 1857.07
   517.3  1866.9   529.4 1868.28   549.4 1872.55   585.6 1881.73   597.7 1886.14
#Mann= 3 ,-1,0
       0     .06       0   272.7    .045       0   332.9      .1       0
Bank Sta=272.7,332.9
XS Rating Curve= 0 ,0
Exp/Cntr(USF)=0,0
Exp/Cntr=0.3,0.1

Type RM Length L Ch R = 1 ,3536    ,228.4,233.1,236
XS GIS Cut Line= 2
2219397.69129321691814.8969960022219224.02027474691280.780223579
#Sta/Elev= 30
       0 1886.07    69.1 1869.32    90.1 1863.35     107 1857.33   121.3 1855.93
   174.3  1855.4   195.3 1852.96   207.9 1853.29   216.3 1849.14   227.9 1849.59
   237.4 1848.54     2491839.704   254.2 1836.49     271 1836.05   296.2 1836.11
   300.4 1836.76   306.71839.754   310.5 1841.21   338.3 1847.18   377.1 1849.38
   421.5  1850.4     435 1852.02   457.7 1858.93   468.7 1863.26   485.5 1871.46
   493.9  1873.1   502.3 1877.31   527.6 1884.83   536.3 1888.27   561.6 1896.13
#Mann= 5 ,-1,0
       0      .1       0     240     .06       0     249    .045       0
   306.7     .06       0     340      .1       0
Bank Sta=249,306.7
XS Rating Curve= 0 ,0
Exp/Cntr(USF)=0,0
Exp/Cntr=0.3,0.1

Type RM Length L Ch R = 1 ,3303    ,219.7,225.2,228.9
XS GIS Cut Line= 2
2219585.88734599691758.9278125312219478.08180223 691207.90975483
#Sta/Elev= 30
       0 1870.31    22.2 1864.15    91.5 1855.97   160.7 1850.61   200.7 1850.44
   205.6 1849.58     226 1850.05     230  1849.3   238.2 1844.75   250.4 1845.21
   254.5 1843.46   260.31839.439   262.6 1837.64   266.7 1836.35   287.1 1835.94
   311.5 1836.27   319.7 1837.88     3221839.448   327.8 1841.92   348.2 1844.01
   368.6 1851.37   388.2 1854.95   405.3 1859.94   417.5 1865.18   437.9 1876.19
   446.1 1878.09   459.7 1886.03   480.2 1895.51   527.9 1911.76   561.5 1922.08
#Mann= 4 ,-1,0
       0      .1       0     170     .06       0   260.3    .045       0
     322      .1       0
Bank Sta=260.3,322
XS Rating Curve= 0 ,0
Exp/Cntr(USF)=0,0
Exp/Cntr=0.3,0.1

Type RM Length L Ch R = 1 ,3078    ,276.9,283.1,288.1
XS GIS Cut Line= 2
2219767.77962029691727.2862667312219732.09136854691133.494958648
#Sta/Elev= 30
       0  1865.7    26.2 1862.77    82.3 1853.23     115 1850.35   134.3 1849.21
   190.5 1850.38   198.5 1847.88   222.5  1848.9   230.5 1845.67   246.6 1841.71
   258.6 1842.03   263.71839.184   270.6 1836.01   290.6  1835.7   322.7 1835.94
   326.7 1836.31   332.31839.109   338.7  1843.2   349.4 1847.04   358.8 1854.12
   362.8 1855.88   414.9  1871.5   438.9 1879.94   466.9  1891.6   531.1 1913.29
   539.9 1916.69   555.1 1926.24   559.1 1927.57   579.2  1929.4   594.9 1929.35
#Mann= 6 ,-1,0
       0      .1       0      40     .05       0     140     .06       0
     240      .1       0   263.7    .045       0   332.3      .1       0
Bank Sta=263.7,332.3
XS Rating Curve= 0 ,0
Exp/Cntr(USF)=0,0
Exp/Cntr=0.3,0.1

Type RM Length L Ch R = 1 ,2795    ,365.1,374.1,381.7
XS GIS Cut Line= 3
2219993.00207948691759.394016465 2220054.8104365691216.270210043
2220062.41345612691102.323650374
#Sta/Elev= 30
       0 1877.98    30.4 1869.01    46.5 1865.38   110.9 1859.56   131.4 1856.75
   219.6 1849.98   227.7 1847.88   251.8 1848.03   255.9 1846.99   263.9 1842.04
   267.9 1840.83     280 1840.29   300.1 1841.98   304.2 1841.48   310.61838.713
   316.2 1836.31   344.4 1835.53   368.6 1835.73   372.6 1837.01   374.51838.716
   380.7 1843.08   404.8 1849.15   445.1 1851.82   465.2 1854.32   513.5 1867.84
   545.7 1870.47   593.8 1869.66   609.9 1874.09   645.9 1889.56   660.8 1893.79
#Mann= 5 ,-1,0
       0      .1       0     170     .05       0     270     .06       0
   310.6    .045       0   374.5      .1       0
Bank Sta=310.6,374.5
XS Rating Curve= 0 ,0
Exp/Cntr(USF)=0,0
Exp/Cntr=0.3,0.1

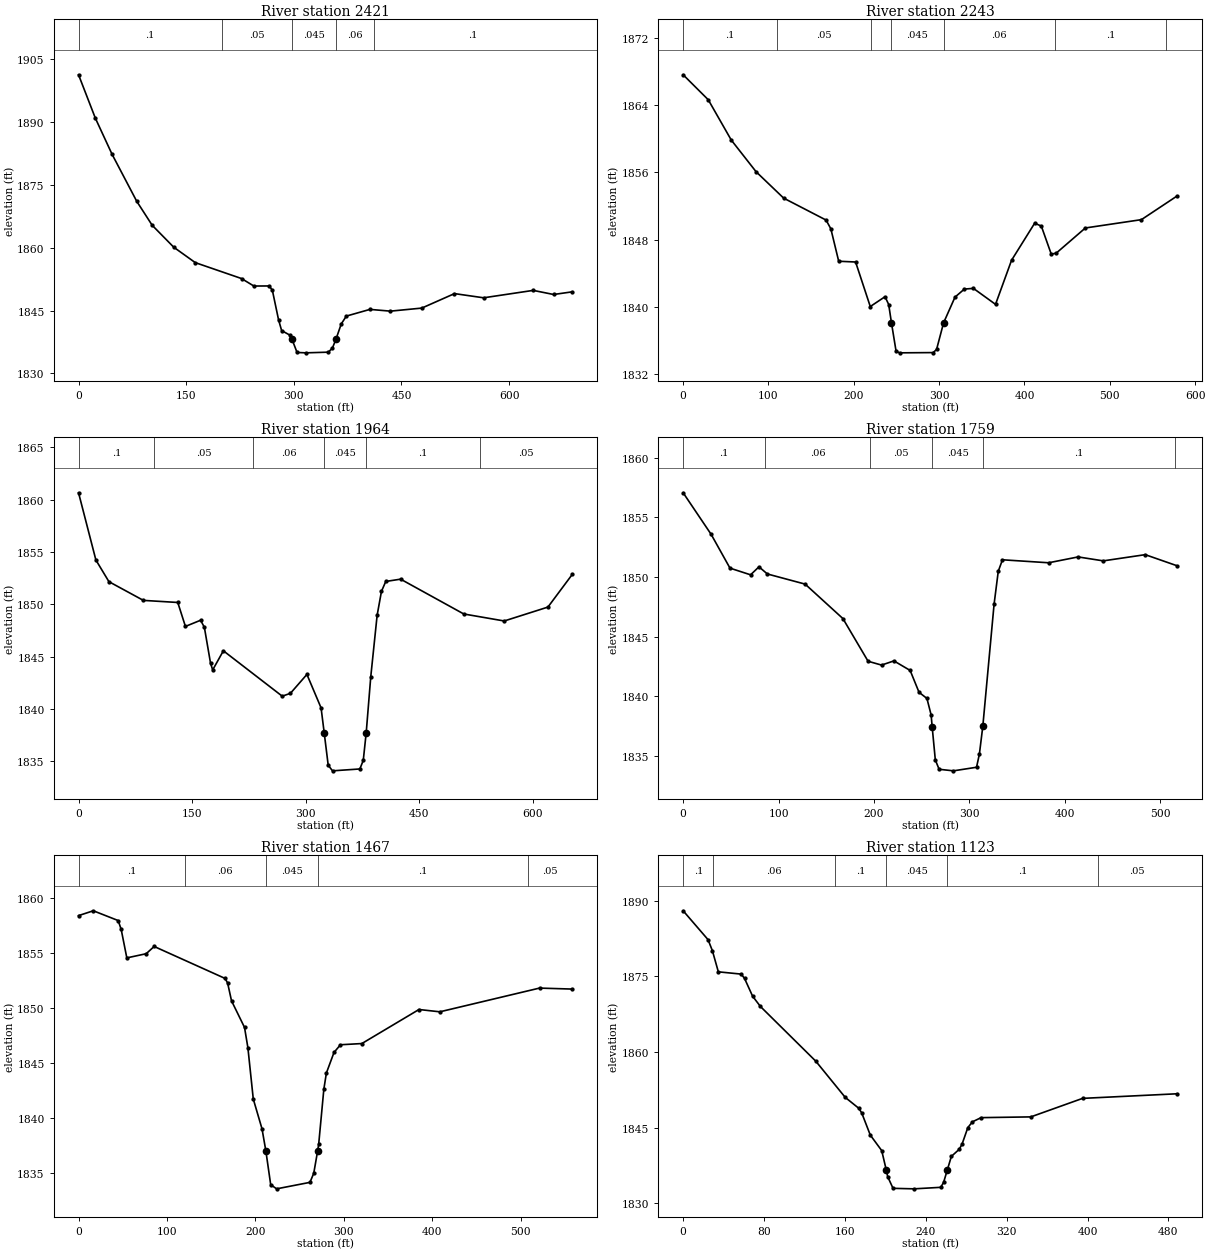
Type RM Length L Ch R = 1 ,2421    ,177,177.6,177.8
XS GIS Cut Line= 3
2220253.35344156691872.7138928022220392.42671011691517.264908236
2220445.33361786691215.379776995
#Sta/Elev= 30
       0 1901.34    23.4 1890.98    46.7 1882.35    81.1 1871.11   102.6 1865.39
   132.7 1860.14   162.7 1856.46   227.1 1852.66   244.3 1850.87   265.8 1850.89
   270.1 1849.85   278.7 1842.82     283 1840.23   295.1 1839.08   297.31838.217
   304.5    1835   316.7 1834.91   348.1 1835.07   353.8 1836.06   358.81838.197
   366.1 1841.82   373.2 1843.69   406.1 1845.29   434.6 1844.87   478.3  1845.6
   523.9 1849.06   564.5 1848.06   633.6 1849.83     662 1848.85   688.2 1849.49
#Mann= 5 ,-1,0
       0      .1       0     200     .05       0   297.3    .045       0
   358.8     .06       0  411.69      .1       0
Bank Sta=297.3,358.8
XS Rating Curve= 0 ,0
Exp/Cntr(USF)=0,0
Exp/Cntr=0.3,0.1

Type RM Length L Ch R = 1 ,2243    ,270.3,279.6,292.2
XS GIS Cut Line= 3
2220433.94736949691888.3955771942220586.67913263691512.252990299
2220705.66796402691386.934592721
#Sta/Elev= 30
       0 1867.61    29.4 1864.64    56.4 1859.84    85.5 1856.07   117.8 1852.93
   167.5 1850.32   173.1 1849.28   182.3 1845.42   202.1 1845.33   219.3 1840.03
   236.6  1841.2   240.9 1840.27   244.11838.116   249.6 1834.68   253.9 1834.52
     293 1834.55     297 1834.92   305.21838.084   318.6 1841.15   329.6 1842.11
   340.2 1842.19   366.1 1840.29   384.9 1845.54     412 1849.95   419.8  1849.6
   431.4 1846.27   437.2 1846.38   471.4 1849.38   537.1 1850.37   578.8 1853.18
#Mann= 7 ,-1,0
       0      .1       0     110     .05       0     220     .06       0
   244.1    .045       0   305.2     .06       0  435.97      .1       0
  565.97     .06       0
Bank Sta=244.1,305.2
XS Rating Curve= 0 ,0
Exp/Cntr(USF)=0,0
Exp/Cntr=0.3,0.1

Type RM Length L Ch R = 1 ,1964    ,196.3,204.8,215.3
XS GIS Cut Line= 4
2220527.70409219691948.8343862242220731.20105645691794.789813125
2220883.88407542691644.1378016482220963.47007174691480.107702249
#Sta/Elev= 30
       0 1860.67    22.9 1854.24    40.1 1852.17    85.6 1850.38     131 1850.18
   141.1 1847.89   161.1 1848.48   166.1 1847.81   174.3 1844.36   177.1 1843.73
   191.2 1845.56   268.9 1841.22   279.7 1841.49   301.5  1843.3   320.2  1840.1
   324.41837.677   329.6 1834.62   335.3 1834.08   371.4 1834.26   375.9 1835.08
   379.8 1837.74   385.8 1843.08   394.2 1848.95   399.9 1851.24   405.6 1852.19
   425.2 1852.41   508.6 1849.08     562 1848.41   619.7 1849.74     652 1852.88
#Mann= 6 ,-1,0
       0      .1       0     100     .05       0     230     .06       0
   324.4    .045       0   379.8      .1       0  529.72     .05       0
Bank Sta=324.4,379.8
XS Rating Curve= 0 ,0
Exp/Cntr(USF)=0,0
Exp/Cntr=0.3,0.1

Type RM Length L Ch R = 1 ,1759    ,298.5,292.4,287.1
XS GIS Cut Line= 3
2220630.51365953692025.4793164992220692.05505391692001.285965501
   2221102.47861691812.597733219
#Sta/Elev= 30
       0 1857.06    29.3 1853.58    49.1 1850.74    70.7 1850.18    79.5 1850.85
    88.3 1850.25   127.9  1849.4   167.5 1846.51   193.9 1842.93     208 1842.61
     221 1842.96     238 1842.16   247.3 1840.33   255.6 1839.81     260 1838.43
   261.11837.421   264.4 1834.65   268.4 1833.87   283.4 1833.74   307.6 1834.04
   310.6 1835.14   314.21837.486     326 1847.71   330.4 1850.48   334.8 1851.44
   383.2 1851.19   414.1 1851.68   440.5 1851.35   484.5 1851.87   517.8 1850.94
#Mann= 6 ,-1,0
       0      .1       0   86.13     .06       0  196.13     .05       0
   261.1    .045       0   314.2      .1       0  516.13     .05       0
Bank Sta=261.1,314.2
XS Rating Curve= 0 ,0
Exp/Cntr(USF)=0,0
Exp/Cntr=0.3,0.1

Type RM Length L Ch R = 1 ,1467    ,394.9,343.2,299.6
XS GIS Cut Line= 3
2220807.85399406692320.1588779092221139.14438025692081.426484775
2221122.06093888691932.206569671
#Sta/Elev= 30
       0 1858.43    16.7 1858.87    44.8 1857.98    48.2 1857.18    54.6 1854.58
    76.5 1854.96    85.5 1855.62   165.7 1852.71   168.6 1852.29     173 1850.67
   187.7 1848.25   191.5 1846.41   197.6 1841.73   207.5 1839.01   211.91836.967
   217.3 1833.93     224 1833.55   261.7 1834.14     266 1834.97   270.31836.959
   271.6 1837.63   277.4 1842.62   280.3  1844.1   288.9 1845.97   296.2 1846.67
   320.4 1846.78     385 1849.88   408.6 1849.67   521.3 1851.83   558.5 1851.74
#Mann= 5 ,-1,0
       0      .1       0     120     .06       0   211.9    .045       0
   270.3      .1       0  508.35     .05       0
Bank Sta=211.9,270.3
XS Rating Curve= 0 ,0
Exp/Cntr(USF)=0,0
Exp/Cntr=0.3,0.1

Type RM Length L Ch R = 1 ,1123    ,242.6,235.3,230.2
XS GIS Cut Line= 3
2221453.61636589692300.420893575 2221422.4952625692261.400915385
2221138.77306611 691926.90885596
#Sta/Elev= 30
       0 1887.97    24.6 1882.25    28.9 1880.07    34.8 1875.87    57.4 1875.42
    60.7 1874.57    68.7 1871.04    76.4 1869.01   131.2 1858.16   160.3 1850.99
   173.7 1848.83   176.6 1847.92   185.1 1843.52   196.4 1840.44     2011836.528
   202.3 1835.28   207.6 1832.96   228.5 1832.86   254.8 1833.16   257.6 1834.13
   261.21836.534   265.3 1839.29   273.1  1840.7   275.9 1841.73   281.6    1845
   286.2 1846.15   294.7 1846.97   343.9 1847.12   395.1 1850.79   488.5  1851.7
#Mann= 6 ,-1,0
       0      .1       0      30     .06       0  149.91      .1       0
     201    .045       0   261.2      .1       0  409.91     .05       0
Bank Sta=201,261.2
XS Rating Curve= 0 ,0
Exp/Cntr(USF)=0,0
Exp/Cntr=0.3,0.1

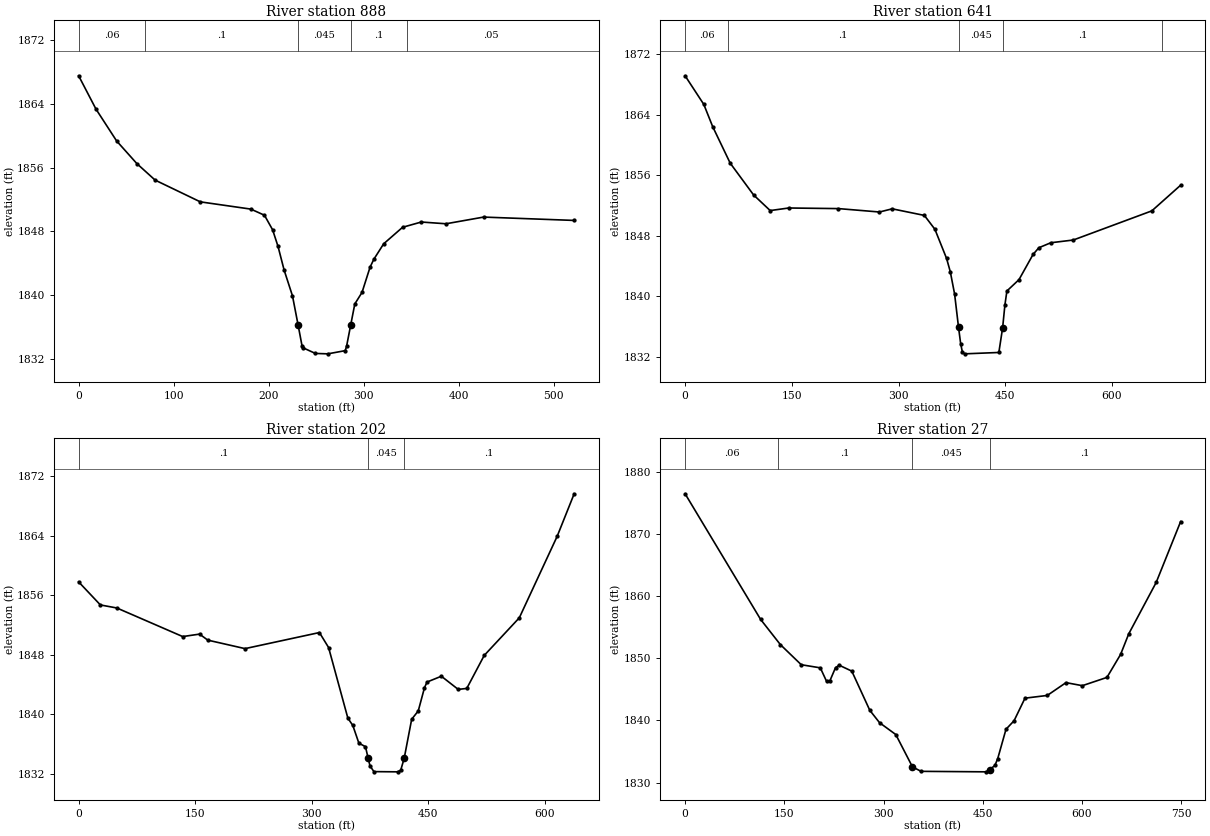
Type RM Length L Ch R = 1 ,888     ,243.1,247.4,250.9
XS GIS Cut Line= 3
2221628.25632471692140.5110034732221543.44145199692010.364043602
2221253.12948882691787.141485869
#Sta/Elev= 30
       0 1867.51    18.3 1863.32      40 1859.33    61.3 1856.49    80.5 1854.42
   128.1 1851.69   181.3 1850.78   195.6 1850.01   204.2 1848.18   209.9 1846.09
   216.3 1843.13   225.1 1839.89   231.11836.183   235.2 1833.59     236 1833.39
   249.2 1832.67   262.3 1832.62   280.6 1833.02     282 1833.55   286.31836.189
   290.7 1838.88   298.3 1840.33   306.8 1843.51   310.8  1844.5   321.1 1846.43
     341  1848.5   360.7 1849.16   386.7 1848.94   426.3 1849.78   521.6 1849.36
#Mann= 5 ,-1,0
       0     .06       0      70      .1       0   231.1    .045       0
   286.3      .1       0  345.34     .05       0
Bank Sta=231.1,286.3
XS Rating Curve= 0 ,0
Exp/Cntr(USF)=0,0
Exp/Cntr=0.3,0.1

Type RM Length L Ch R = 1 ,641     ,383.1,438,473.7
XS GIS Cut Line= 3
2221653.41786078692142.762812215 2221721.6597124691860.046569797
2221436.73997754 691571.28478267
#Sta/Elev= 30
       0 1869.13    26.3 1865.35    38.7 1862.43    63.4 1857.59    96.3 1853.39
   119.6 1851.33   145.7 1851.67   215.6 1851.59   273.2 1851.14   291.1 1851.56
   336.3 1850.69   351.1 1848.86   367.5 1845.01   372.7 1843.27   378.8 1840.31
   384.31835.926   387.3 1833.77   389.8 1832.61   392.9 1832.41     441 1832.59
   446.3 1835.85   449.5 1838.86   452.3 1840.71   469.3 1842.21   489.1 1845.54
   497.2 1846.42     514 1847.08   545.6 1847.44     656 1851.29   696.5 1854.68
#Mann= 5 ,-1,0
       0     .06       0      60      .1       0   384.3    .045       0
   446.3      .1       0  670.84     .05       0
Bank Sta=384.3,446.3
XS Rating Curve= 0 ,0
Exp/Cntr(USF)=0,0
Exp/Cntr=0.3,0.1

Type RM Length L Ch R = 1 ,202     ,176.9,175.3,177.6
XS GIS Cut Line= 4
  2221692.331544 692086.216152262221896.48683108691853.106040503
2222078.46510207691686.5634264352222113.39843087691613.447156845
#Sta/Elev= 30
       0 1857.77      28 1854.67    49.2 1854.26   133.9 1850.42   155.6 1850.75
   166.2 1849.94   214.1  1848.8   309.8 1850.96   321.6 1848.95   346.4 1839.46
   352.8 1838.47   360.6 1836.09   369.1 1835.62   372.41834.105   374.9 1833.04
   379.9 1832.27   410.5 1832.24   414.4 1832.45   418.91834.066   428.5  1839.3
     437 1840.43     445 1843.55   448.3 1844.31   466.7 1845.09   488.4 1843.32
   499.4 1843.45   521.9 1847.89     567 1852.94   615.7 1863.89   637.6 1869.61
#Mann= 3 ,-1,0
       0      .1       0   372.4    .045       0   418.9      .1       0
Bank Sta=372.4,418.9
XS Rating Curve= 0 ,0
Exp/Cntr(USF)=0,0
Exp/Cntr=0.3,0.1

Type RM Length L Ch R = 1 ,27      ,,,
XS GIS Cut Line= 4
2221720.18026095692160.1076743292222016.61536748691969.662653529
2222101.10527901691908.732428871 2222173.4091456691625.203783458
#Sta/Elev= 30
       0 1876.45   114.1 1856.25     144 1852.19   175.6 1848.95   204.4 1848.45
   213.9 1846.27   218.7 1846.32   227.4 1848.48     233 1848.87     252 1847.92
   279.2 1841.62     294 1839.62   318.5 1837.72   343.7 1832.52   356.7  1831.8
   455.4 1831.72   460.2 1832.07   468.3 1832.74   472.6 1833.85   485.1 1838.57
   497.3 1839.94   513.8 1843.57   547.5 1844.01   575.8 1846.07   600.5 1845.58
   637.7 1846.91   658.3  1850.6   670.7 1853.93   712.1 1862.18   749.1 1871.98
#Mann= 4 ,-1,0
       0     .06       0     140      .1       0   343.7    .045       0
   460.2      .1       0
Bank Sta=343.7,460.2
XS Rating Curve= 0 ,0
Exp/Cntr(USF)=0,0
Exp/Cntr=0.3,0.1
LCMann Table=0

Chan Stop Cuts=-1
Use User Specified Reach Order=0
Composite Channel Slope=5